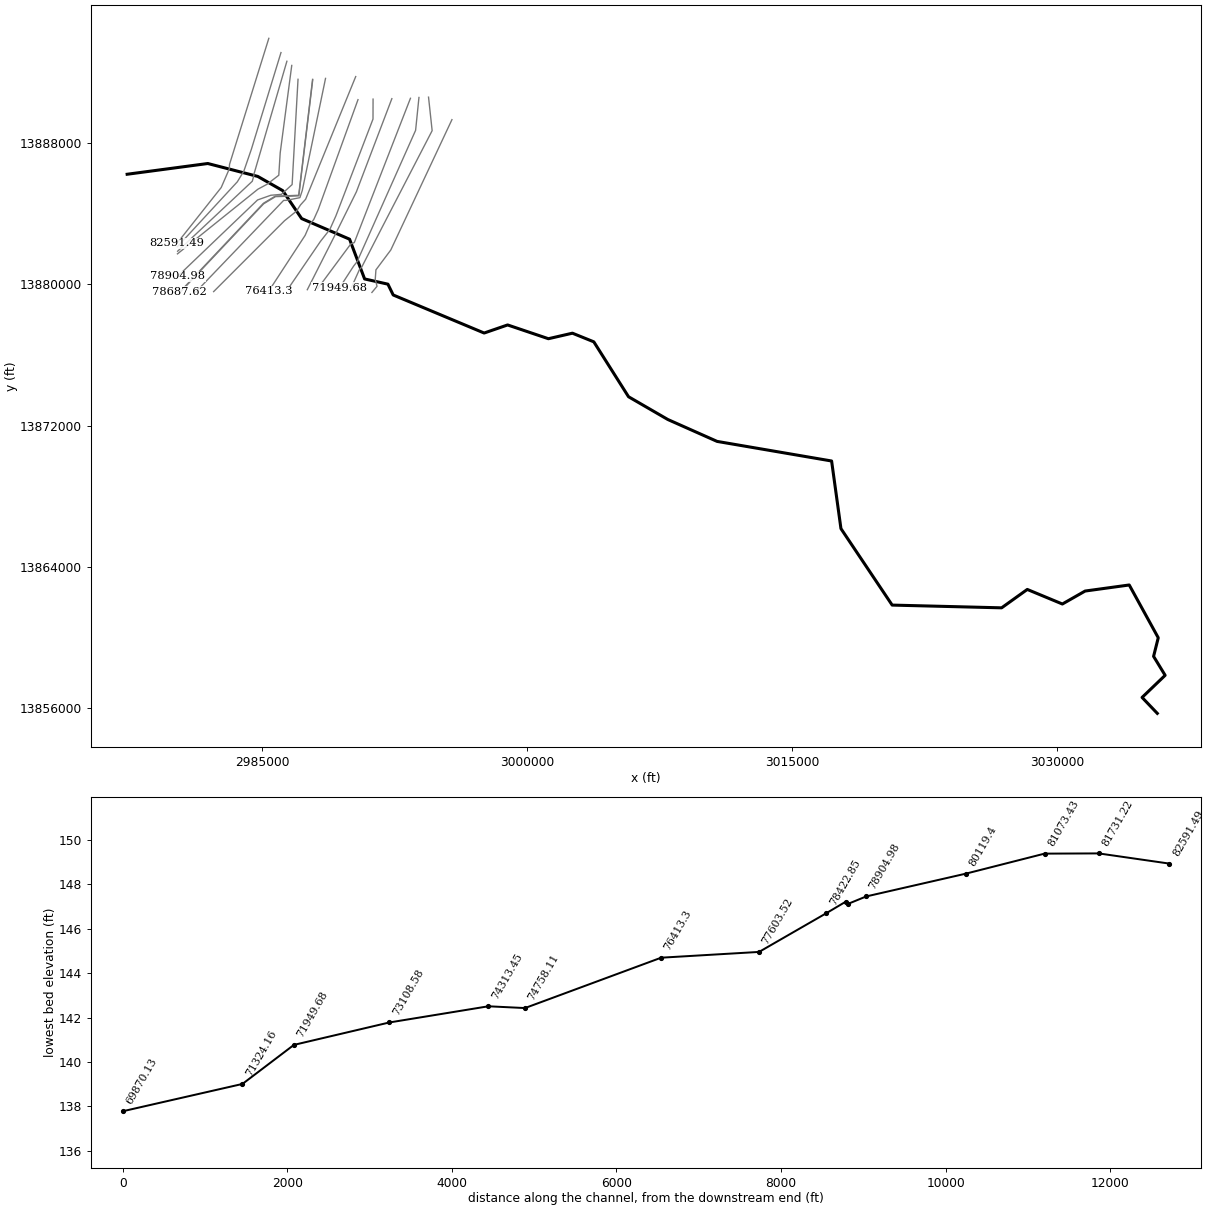
HEC-RAS study U102-00-00.prj: U102-00-00 (Update)

--- U102-00-00.f02 (steady flow) ---

Flow Title=Effective FW 2020 (Re-Study)
Program Version=4.10
Number of Profiles= 2
Profile Names=100YR,FW
River Rch & RM=U102-00-00,U102-00-00_0197 ,82591.49
    6535    6535
River Rch & RM=U102-00-00,U102-00-00_0197 ,81073.43
    6347    6347
River Rch & RM=U102-00-00,U102-00-00_0197 ,80119.4
    6115    6115
River Rch & RM=U102-00-00,U102-00-00_0197 ,78904.98
    5877    5877
River Rch & RM=U102-00-00,U102-00-00_0197 ,77603.52
    5667    5667
River Rch & RM=U102-00-00,U102-00-00_0197 ,76413.3
    5387    5387
River Rch & RM=U102-00-00,U102-00-00_0197 ,74758.11
    5314    5314
River Rch & RM=U102-00-00,U102-00-00_0197 ,74313.45
    5122    5122
River Rch & RM=U102-00-00,U102-00-00_0197 ,73108.58
    4944    4944
River Rch & RM=U102-00-00,U102-00-00_0197 ,71949.68
    4850    4850
River Rch & RM=U102-00-00,U102-00-00_0197 ,71324.16
    4639    4639
River Rch & RM=U102-00-00,U102-00-00_0197 ,69870.13
    4440    4440
River Rch & RM=U102-00-00,U102-00-00_0197 ,68441.07
    4331    4331
River Rch & RM=U102-00-00,U102-00-00_0197 ,67625.08
    4153    4153
River Rch & RM=U102-00-00,U102-00-00_0197 ,66253.16
    4014    4014
River Rch & RM=U102-00-00,U102-00-00_0197 ,65139.42
    3823    3823
River Rch & RM=U102-00-00,U102-00-00_0197 ,63543.31
    3781    3781
River Rch & RM=U102-00-00,U102-00-00_0197 ,63182.11
    3864    3864
River Rch & RM=U102-00-00,U102-00-00_0197 ,61507.56
    3931    3931
River Rch & RM=U102-00-00,U102-00-00_0197 ,60176.11
    3983    3983
River Rch & RM=U102-00-00,U102-00-00_0197 ,59168.92
    4039    4039
River Rch & RM=U102-00-00,U102-00-00_0197 ,58086.16
    4125    4125
River Rch & RM=U102-00-00,U102-00-00_0197 ,56470.21
    4210    4210
River Rch & RM=U102-00-00,U102-00-00_0197 ,54885.61
    4245    4245
River Rch & RM=U102-00-00,U102-00-00_0197 ,54244.41
    4308    4308
River Rch & RM=U102-00-00,U102-00-00_0197 ,53109.38
    4383    4383
River Rch & RM=U102-00-00,U102-00-00_0197 ,51782.55
    4419    4419
River Rch & RM=U102-00-00,U102-00-00_0197 ,51146.17
    4488    4488
River Rch & RM=U102-00-00,U102-00-00_0197 ,49965.56
    4553    4553
River Rch & RM=U102-00-00,U102-00-00_0197 ,48859.02
    4613    4613
River Rch & RM=U102-00-00,U102-00-00_0197 ,47847.21
    4694    4694
River Rch & RM=U102-00-00,U102-00-00_0197 ,46507.83
    4939    4939
River Rch & RM=U102-00-00,U102-00-00_0197 ,43344.77
    5187    5187
River Rch & RM=U102-00-00,U102-00-00_0197 ,40319
    5450    5450
River Rch & RM=U102-00-00,U102-00-00_0197 ,37245.13
    5672    5672
River Rch & RM=U102-00-00,U102-00-00_0197 ,34772.93
    5968    5968
River Rch & RM=U102-00-00,U102-00-00_0197 ,31627.03
    6255    6255
River Rch & RM=U102-00-00,U102-00-00_0197 ,28717.43
    6576    6576
River Rch & RM=U102-00-00,U102-00-00_0197 ,25612.09
    6837    6837
River Rch & RM=U102-00-00,U102-00-00_0197 ,23202.72
    7993    7993
River Rch & RM=U102-00-00,U102-00-00_0197 ,22713.43
    7802    7802
River Rch & RM=U102-00-00,U102-00-00_0197 ,21190.79
    7618    7618
Boundary for River Rch & Prof#=U102-00-00,U102-00-00_0197 , 1
Up Type= 0
Dn Type= 1
Dn Known WS=100.8
Boundary for River Rch & Prof#=U102-00-00,U102-00-00_0197 , 2
Up Type= 0
Dn Type= 1
Dn Known WS=101.8
Observed WS=U102-00-00      ,U102-00-00_0197 ,82591.49,0,158.16,159.06
Observed WS=U102-00-00      ,U102-00-00_0197 ,81731.22,0,158.01,158.96
Observed WS=U102-00-00      ,U102-00-00_0197 ,81073.43,0,157.89,158.87
Observed WS=U102-00-00      ,U102-00-00_0197 ,80119.4 ,0,157.43,158.58
Observed WS=U102-00-00      ,U102-00-00_0197 ,78904.98,0,156.64,157.98
Observed WS=U102-00-00      ,U102-00-00_0197 ,78687.62,0,156.43,157.74
Observed WS=U102-00-00      ,U102-00-00_0197 ,78654.82,0,156.28,157.62
Observed WS=U102-00-00      ,U102-00-00_0197 ,78422.85,0,156.08,157.26
Observed WS=U102-00-00      ,U102-00-00_0197 ,77603.52,0,155.6,156.75
Observed WS=U102-00-00      ,U102-00-00_0197 ,76413.3 ,0,154.81,155.74
Observed WS=U102-00-00      ,U102-00-00_0197 ,74758.11,0,153.89,154.79
Observed WS=U102-00-00      ,U102-00-00_0197 ,74313.45,0,153.53,154.42
Observed WS=U102-00-00      ,U102-00-00_0197 ,73108.58,0,152.52,153.47
Observed WS=U102-00-00      ,U102-00-00_0197 ,71949.68,0,151.23,152.18
Observed WS=U102-00-00      ,U102-00-00_0197 ,71324.16,0,150.35,151.52
Observed WS=U102-00-00      ,U102-00-00_0197 ,69870.13,0,149.28,150.04
Observed WS=U102-00-00      ,U102-00-00_0197 ,69031.07,0,148.94,149.64
Observed WS=U102-00-00      ,U102-00-00_0197 ,68924.32,0,148.84,149.46
Observed WS=U102-00-00      ,U102-00-00_0197 ,68877.77,0,148.38,149.14
Observed WS=U102-00-00      ,U102-00-00_0197 ,68441.07,0,148.05,148.79
Observed WS=U102-00-00      ,U102-00-00_0197 ,67625.08,0,147.5,148.29
Observed WS=U102-00-00      ,U102-00-00_0197 ,66253.16,0,146.34,147.21
Observed WS=U102-00-00      ,U102-00-00_0197 ,65864.54,0,146.04,146.77
Observed WS=U102-00-00      ,U102-00-00_0197 ,65139.42,0,145.46,146.17
Observed WS=U102-00-00      ,U102-00-00_0197 ,64170.07,0,144.7,145.61
Observed WS=U102-00-00      ,U102-00-00_0197 ,63598.3 ,0,144.41,145.37
Observed WS=U102-00-00      ,U102-00-00_0197 ,63543.31,0,144.42,145.37
Observed WS=U102-00-00      ,U102-00-00_0197 ,63435.61,0,144.37,144.97
Observed WS=U102-00-00      ,U102-00-00_0197 ,63182.11,0,144.2,144.81
Observed WS=U102-00-00      ,U102-00-00_0197 ,62613.3 ,0,143.73,144.41
Observed WS=U102-00-00      ,U102-00-00_0197 ,61507.56,0,143.15,143.84
Observed WS=U102-00-00      ,U102-00-00_0197 ,60176.11,0,142.48,143.23
Observed WS=U102-00-00      ,U102-00-00_0197 ,59168.92,0,141.94,142.74
Observed WS=U102-00-00      ,U102-00-00_0197 ,58086.16,0,141.36,142.12
Observed WS=U102-00-00      ,U102-00-00_0197 ,57213.66,0,140.83,141.31
Observed WS=U102-00-00      ,U102-00-00_0197 ,57093.08,0,140.71,140.99
Observed WS=U102-00-00      ,U102-00-00_0197 ,57037.9 ,0,136.95,139.28
Observed WS=U102-00-00      ,U102-00-00_0197 ,56832.31,0,136.92,139.23
Observed WS=U102-00-00      ,U102-00-00_0197 ,56666.18,0,136.69,139.02
Observed WS=U102-00-00      ,U102-00-00_0197 ,56470.21,0,136.41,138.77
Observed WS=U102-00-00      ,U102-00-00_0197 ,56194.89,0,135.49,137.8
Observed WS=U102-00-00      ,U102-00-00_0197 ,56132.66,0,135.2,137.52
Observed WS=U102-00-00      ,U102-00-00_0197 ,55887.13,0,134.52,136.85
Observed WS=U102-00-00      ,U102-00-00_0197 ,55580.36,0,133.67,136.01
Observed WS=U102-00-00      ,U102-00-00_0197 ,55351.98,0,133.04,135.39
Observed WS=U102-00-00      ,U102-00-00_0197 ,54885.61,0,132.59,134.99
Observed WS=U102-00-00      ,U102-00-00_0197 ,54244.41,0,131.97,134.45
Observed WS=U102-00-00      ,U102-00-00_0197 ,53109.38,0,130.86,133.41
Observed WS=U102-00-00      ,U102-00-00_0197 ,52414.93,0,130.45,133.04
Observed WS=U102-00-00      ,U102-00-00_0197 ,52204.51,0,130.33,132.92
Observed WS=U102-00-00      ,U102-00-00_0197 ,52104.96,0,130.27,132.87
Observed WS=U102-00-00      ,U102-00-00_0197 ,52014.66,0,130.22,132.82
Observed WS=U102-00-00      ,U102-00-00_0197 ,51929.68,0,130.18,132.78
Observed WS=U102-00-00      ,U102-00-00_0197 ,51782.55,0,130.11,132.7
Observed WS=U102-00-00      ,U102-00-00_0197 ,51146.17,0,129.79,132.37
Observed WS=U102-00-00      ,U102-00-00_0197 ,50998.88,0,129.67,132.25
Observed WS=U102-00-00      ,U102-00-00_0197 ,49965.56,0,128.86,131.37
Observed WS=U102-00-00      ,U102-00-00_0197 ,48859.02,0,127.64,130.07
Observed WS=U102-00-00      ,U102-00-00_0197 ,47847.21,0,126.34,128.74
Observed WS=U102-00-00      ,U102-00-00_0197 ,47111.71,0,125.62,128.08
Observed WS=U102-00-00      ,U102-00-00_0197 ,46984.47,0,124.9,127.09
Observed WS=U102-00-00      ,U102-00-00_0197 ,46873.4 ,0,124.69,126.85
Observed WS=U102-00-00      ,U102-00-00_0197 ,46507.83,0,124.75,126.99
Observed WS=U102-00-00      ,U102-00-00_0197 ,46401.06,0,124.68,126.9
Observed WS=U102-00-00      ,U102-00-00_0197 ,46387.11,0,124.69,126.91
Observed WS=U102-00-00      ,U102-00-00_0197 ,46369.31,0,122.29,124.72
Observed WS=U102-00-00      ,U102-00-00_0197 ,46304.02,0,122.28,124.71
Observed WS=U102-00-00      ,U102-00-00_0197 ,45910.1 ,0,122.21,124.67
Observed WS=U102-00-00      ,U102-00-00_0197 ,45379.92,0,121.81,124.2
Observed WS=U102-00-00      ,U102-00-00_0197 ,44394.45,0,120.84,123.15
Observed WS=U102-00-00      ,U102-00-00_0197 ,43344.77,0,119.68,121.93
Observed WS=U102-00-00      ,U102-00-00_0197 ,42393.07,0,118.22,120.51
Observed WS=U102-00-00      ,U102-00-00_0197 ,41585.04,0,117.3,119.54
Observed WS=U102-00-00      ,U102-00-00_0197 ,41483.83,0,117.2,119.44
Observed WS=U102-00-00      ,U102-00-00_0197 ,41354.38,0,116.88,119.07
Observed WS=U102-00-00      ,U102-00-00_0197 ,40963.29,0,116.62,118.81
Observed WS=U102-00-00      ,U102-00-00_0197 ,40319   ,0,116.03,118.19
Observed WS=U102-00-00      ,U102-00-00_0197 ,39300.46,0,115.16,117.35
Observed WS=U102-00-00      ,U102-00-00_0197 ,38178.64,0,114.19,116.38
Observed WS=U102-00-00      ,U102-00-00_0197 ,37416.59,0,113.67,115.77
Observed WS=U102-00-00      ,U102-00-00_0197 ,37245.13,0,113.52,115.58
Observed WS=U102-00-00      ,U102-00-00_0197 ,37157.18,0,113.36,115.4
Observed WS=U102-00-00      ,U102-00-00_0197 ,36534.81,0,112.53,114.61
Observed WS=U102-00-00      ,U102-00-00_0197 ,35899.56,0,111.76,113.95
Observed WS=U102-00-00      ,U102-00-00_0197 ,34772.93,0,110.1,112.59
Observed WS=U102-00-00      ,U102-00-00_0197 ,33548.85,0,109.65,112.22
Observed WS=U102-00-00      ,U102-00-00_0197 ,33198.41,0,109.44,111.99
Observed WS=U102-00-00      ,U102-00-00_0197 ,32860.97,0,109.24,111.76
Observed WS=U102-00-00      ,U102-00-00_0197 ,32501.36,0,109.03,111.52
Observed WS=U102-00-00      ,U102-00-00_0197 ,31927.16,0,108.96,111.48
Observed WS=U102-00-00      ,U102-00-00_0197 ,31627.03,0,108.89,111.4
Observed WS=U102-00-00      ,U102-00-00_0197 ,31502.26,0,108.77,111.28
Observed WS=U102-00-00      ,U102-00-00_0197 ,30893.76,0,108.59,111.08
Observed WS=U102-00-00      ,U102-00-00_0197 ,30519.31,0,108.48,110.95
Observed WS=U102-00-00      ,U102-00-00_0197 ,30404.01,0,108.32,110.88
Observed WS=U102-00-00      ,U102-00-00_0197 ,29758.59,0,107.88,110.38
Observed WS=U102-00-00      ,U102-00-00_0197 ,28717.43,0,107.33,109.8
Observed WS=U102-00-00      ,U102-00-00_0197 ,27577.4 ,0,106.66,109.05
Observed WS=U102-00-00      ,U102-00-00_0197 ,26703.26,0,105.75,107.95
Observed WS=U102-00-00      ,U102-00-00_0197 ,25612.09,0,103.3,104.73
Observed WS=U102-00-00      ,U102-00-00_0197 ,24471.49,0,102.93,104.3
Observed WS=U102-00-00      ,U102-00-00_0197 ,24458.73,0,102.92,104.29
Observed WS=U102-00-00      ,U102-00-00_0197 ,24381.77,0,102.87,104.2
Observed WS=U102-00-00      ,U102-00-00_0197 ,24132.54,0,102.7,103.94
Observed WS=U102-00-00      ,U102-00-00_0197 ,24113.3 ,0,102.69,103.92
Observed WS=U102-00-00      ,U102-00-00_0197 ,23852.4 ,0,102.6,103.78
Observed WS=U102-00-00      ,U102-00-00_0197 ,23538.14,0,102.5,103.61
Observed WS=U102-00-00      ,U102-00-00_0197 ,23202.72,0,102.37,103.43
Observed WS=U102-00-00      ,U102-00-00_0197 ,22713.43,0,102.27,103.28
Observed WS=U102-00-00      ,U102-00-00_0197 ,21190.79,0,101.8,102.66
Observed WS=U102-00-00      ,U102-00-00_0197 ,20750.87,0,101.65,102.46
Observed WS=U102-00-00      ,U102-00-00_0197 ,19692.43,0,98.2,99.9
DSS Import GetInterval= 0
DSS Import GetPeak= 0
DSS Import FillOption= 0

--- U102-00-00.g01 (geometry) ---

Geom Title=U102-00-00 2020
Program Version=4.10

River Reach=U102-00-00      ,U102-00-00_0197
Reach XY= 30
2977348.96149352 13886232.0262622981913.5032174413886839.9955185
2984741.4496612713886109.43070672986155.3979488613885303.9500342
2987223.7448935213883723.99420462989937.0790337813882556.9410925
2990787.9605341113880307.39178582992106.8099305313880011.8014978
2992406.0803293613879399.51958582997553.1231848613877246.2397717
2998880.9633769413877703.7030956 3001189.881003213876924.3565572
3002549.1571560213877237.36807033003760.0025033713876748.0002826
3005724.7751486213873640.54127443007947.5489182813872352.8660283
3010736.3179470313871112.96496483017217.7518345313870004.0009754
3017746.5253832813866176.61656983020644.5008865313861848.9969442
3026840.1600831213861693.72002383028291.4849363613862734.4643334
3030278.2362121913861909.97123173031565.0371162713862643.8578873
3034062.2105996213862987.01336893035704.2634178513859999.7611413
3035440.1691297713858947.06770873036094.0913783613857874.3831743
3034789.4036990313856622.83023123035650.5197589413855720.4996868

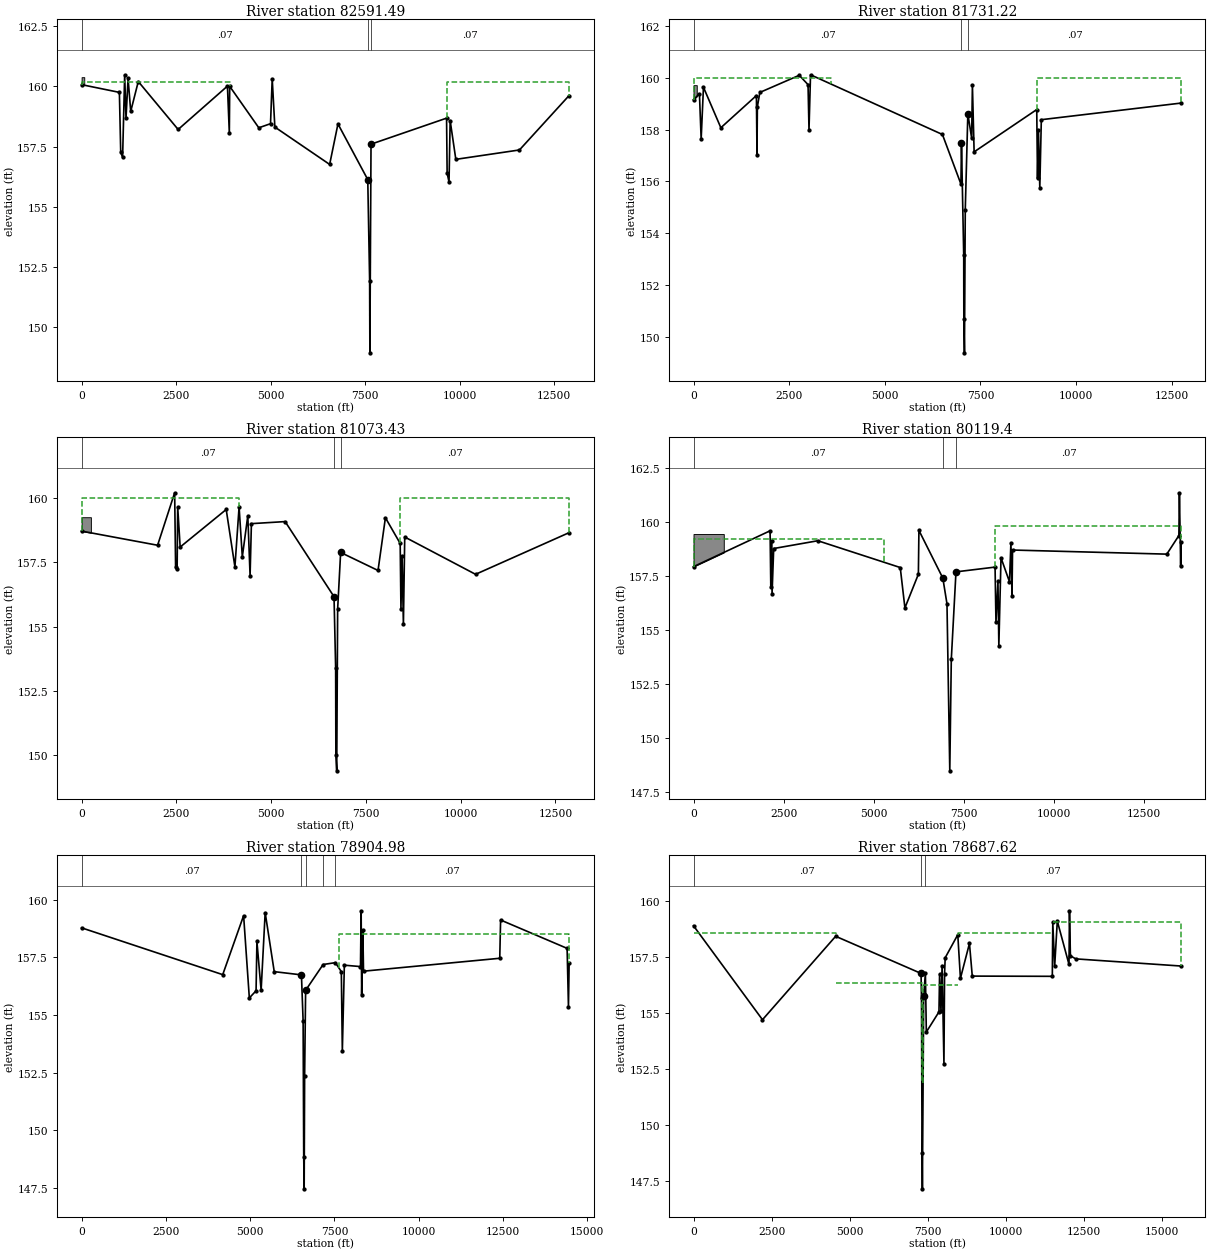
Type RM Length L Ch R = 1 ,82591.49,1315.58,860.27,721.06
Node Name=AK
XS GIS Cut Line= 6
2985366.8824655313893924.29532632983144.6999020313886796.5198837
2983133.8400156113886633.76003862983144.6999020313886568.6601032
2982672.9498612713885481.59009892980178.4541941113882333.4992822
#Sta/Elev= 30
       0  160.07  999.48  159.75 1034.47  157.27 1084.44  157.05 1139.41  160.48
 1174.39  158.67 1229.37  160.33 1299.33  158.96 1499.23   160.2 2553.69  158.21
 3858.02  160.01 3907.99  158.06 3917.99     160 4687.59  158.28 4997.44  158.45
 5042.42  160.31 5112.38  158.31 6561.65  156.76 6781.54  158.44 7569.99  156.13
 7619.43  151.93 7625.98  148.94 7656.28   157.6 9654.73  158.68 9669.72   156.4
 9719.68  156.03 9749.66  158.58 9899.54  156.9711583.19  157.3612897.14  159.62
#Mann= 3 , 0 , 0
       0     .07       0 7569.99     .05       0 7656.28     .07       0
#XS Ineff= 2 ,-1
       0 3917.99   160.2 9654.7312897.14   160.2
Permanent Ineff=
       F       F
#Block Obstruct= 2 , 0
       0   69.96  160.38               0
Bank Sta=7569.99,7656.28
XS Rating Curve= 0 ,0
Exp/Cntr=0.3,0.1

Type RM Length L Ch R = 1 ,81731.22,539.18,657.79,604.69
XS GIS Cut Line= 6
2986055.1720994413893118.01281812984379.3700048613887645.6901014
2983969.3501556113886455.8099352 2983934.630080713886377.6900127
2983584.7075521913885804.6012639 2980188.584423213882126.1807992
#Sta/Elev= 30
       0  159.15  154.95  159.38  199.94  157.63  259.92  159.63  714.77  158.07
 1644.47  159.31 1659.47  157.03 1669.47  158.88 1734.44  159.43 2764.11  160.09
 2994.04  159.73 3019.03  157.99 3059.02  160.11 6507.19  157.81 6991.13   155.9
 7005.38  157.47 7063.98  153.15 7067.12   150.7 7083.01   149.4 7104.48  154.92
 7171.57  158.61 7271.05  157.67 7290.95  159.72 7335.71  157.14 8972.73  158.77
 8992.71  156.12 9017.69  157.98 9052.67  155.75 9092.64  158.3812745.04  159.02
#Mann= 3 , 0 , 0
       0     .07       0 7005.38     .05       0 7171.57     .07       0
#XS Ineff= 2 ,-1
       0 3588.85     160 8972.7312745.04     160
Permanent Ineff=
       F       F
#Block Obstruct= 2 , 0
       0   84.97  159.7112735.04       0  159.43
Bank Sta=7005.38,7171.57
XS Rating Curve= 0 ,0
Exp/Cntr=0.3,0.1

Type RM Length L Ch R = 1 ,81073.43,1162.51,954.04,559.97
XS GIS Cut Line= 5
2986389.4844229413892626.37731842984524.8998975313886238.7998705
2984524.8998975313886178.02997892984431.33315553 13885835.460126
2980205.2553216113881876.1169949
#Sta/Elev= 30
       0  158.71 2004.75  158.16  2454.7   160.2 2479.69   157.3 2519.69  157.22
 2534.69  159.65 2599.68  158.09 3814.54  159.55 4044.51  157.32  4154.5  159.65
 4239.48  157.71 4384.46  159.31 4444.46  156.98 4479.45     159 5369.33  159.08
 6658.84  156.16 6701.92  153.37 6707.49     150 6730.07  149.39 6754.39  155.68
  6833.3  157.88 7819.54  157.18  8014.4  159.23 8404.14  158.23 8424.12   155.7
  8454.1  157.73 8489.08  155.08 8524.05  158.4810392.78  157.0312861.09  158.65
#Mann= 3 ,-1 , 0
       0     .07       0 6658.84     .05       0  6833.3     .07       0
#XS Ineff= 2 ,-1
       0  4154.5     160 8404.1412861.09     160
Permanent Ineff=
       F       F
#Block Obstruct= 2 , 0
       0  244.97  159.2512791.14       0     160
Bank Sta=6658.84,6833.3
XS Rating Curve= 0 ,0
Exp/Cntr=0.3,0.1

Type RM Length L Ch R = 1 ,80119.4 ,801.6,1214.41,523.74
Node Name=AJ
XS GIS Cut Line= 6
2986664.8004733613892390.39222612986011.2899693513887444.4598608
2985930.9098807713886176.84002072985275.2501028613885670.1999578
2984748.0805535313885385.34554072980196.9197083613881726.0789091
#Sta/Elev= 30
       0  157.94 2124.54   159.6 2144.54  157.01 2164.53  159.13 2179.53  156.68
 2224.52  158.78 3449.25  159.14 5736.02   157.9 5865.53  156.03  6239.1  157.59
 6254.04  159.62  6917.9  157.41 7032.71  156.22 7110.52  148.49 7152.53  153.65
 7282.35   157.7  8366.8  157.92  8391.8  155.36  8446.8  157.26  8471.8  154.27
  8531.8  158.35  8766.8  157.24  8806.8  159.05  8836.8  156.57  8851.8  158.71
 13131.8  158.52 13466.8  159.38 13481.8  161.36 13516.8  157.96 13526.8  159.09
#Mann= 3 ,-1 , 0
       0     .07       0  6917.9     .05       0 7282.35     .07       0
#XS Ineff= 2 ,-1
       0 5297.11   159.2  8366.8 13526.8   159.8
Permanent Ineff=
       T       T
#Block Obstruct= 2 , 0
       0  839.82  159.45 13481.8       0  161.36
Bank Sta=6917.9,7282.35
XS Rating Curve= 0 ,0
Exp/Cntr=0.3,0.1

Type RM Length L Ch R = 1 ,78904.98,600.47,217.36,302.96
Node Name=AI
XS GIS Cut Line= 6
2987020.0061277713891606.36853172986685.9100111913885649.0999344
2986079.4899641913885095.08004512985481.6027085313885043.5496363
2984729.9027683613884777.62693982980205.2553216113880450.7537038
#Sta/Elev= 30
       0  158.78 4186.89  156.75 4806.46  159.31 4976.34  155.74  5176.2  156.05
 5201.18  158.19 5326.09  156.07 5446.01  159.44 5715.23  156.88 6522.18  156.74
 6571.88  154.74 6589.77  148.86 6603.21  147.46  6616.6  152.36 6646.42  156.07
 7165.48  157.19 7529.82  157.27 7705.59  156.88 7735.49  153.42 7795.29  157.16
 8273.87   157.1 8293.86  159.52 8308.85  155.86 8343.82   158.7 8363.81   156.9
12405.81  157.4612430.79  159.1214404.33  157.89 14444.3  155.3314464.28  157.25
#Mann= 5 ,-1 , 0
       0     .07       0 6522.18     .05       0 6646.42     .07       0
 7165.48     .12       0 7529.82     .07       0
#XS Ineff= 4 ,-1
       0 5446.01   158.5 5446.01 6487.39   156.1 6816.66  7640.8   156.1
  7640.814464.28   158.5
Permanent Ineff=
       T       F       F       T
#Block Obstruct= 2 , 0
       0                14404.33       0  157.89
Bank Sta=6522.18,6646.42
XS Rating Curve= 0 ,0
Exp/Cntr=0.5,0.3

Type RM Length L Ch R = 1 ,78687.62,11.9,32.8,31.02
BEGIN DESCRIPTION:
Upstream Section (LONGENBAUGH ROAD)
END DESCRIPTION:
XS GIS Cut Line= 6
2987844.1071698713891603.34688422987058.0113011213885042.8905169
2986490.49143878 13885019.0286882985738.8708947713884997.6701349
2985065.3758506913884590.84909822980329.7698363713879568.4319777
#Sta/Elev= 30
       0  158.89 2209.13  154.69 4553.18  158.42 7288.35  156.76 7303.08  155.64
 7320.62  148.74 7331.38  147.13 7372.61  155.75 7427.59  156.77 7457.57  154.14
 7862.38  155.04 7882.37  156.73 7927.34  155.06  7962.2  157.11 8021.96  152.73
 8041.88  156.75  8061.8  157.46 8465.18  158.49 8549.84  156.54 8839.13   158.1
  8929.1  156.64 11493.1  156.6311508.09  159.0411568.07  157.0711653.03   159.1
12027.89  157.1612042.88  159.5612072.87  157.55 12242.8  157.4115616.48  157.09
#Mann= 3 ,-1 , 0
       0     .07       0 7288.35     .05       0 7427.59     .07       0
#XS Ineff= 5 ,-1
       0 4553.18  158.55 4553.18 7312.61  156.33    7354 8465.18  156.25
 8465.1811508.09  158.5511508.0915616.48  159.04
Permanent Ineff=
       F       F       F       F       F
#Block Obstruct= 2 , 0
       0                15591.49       0  158.12
Bank Sta=7288.35,7372.61
XS Rating Curve= 0 ,0
Exp/Cntr=0.5,0.3

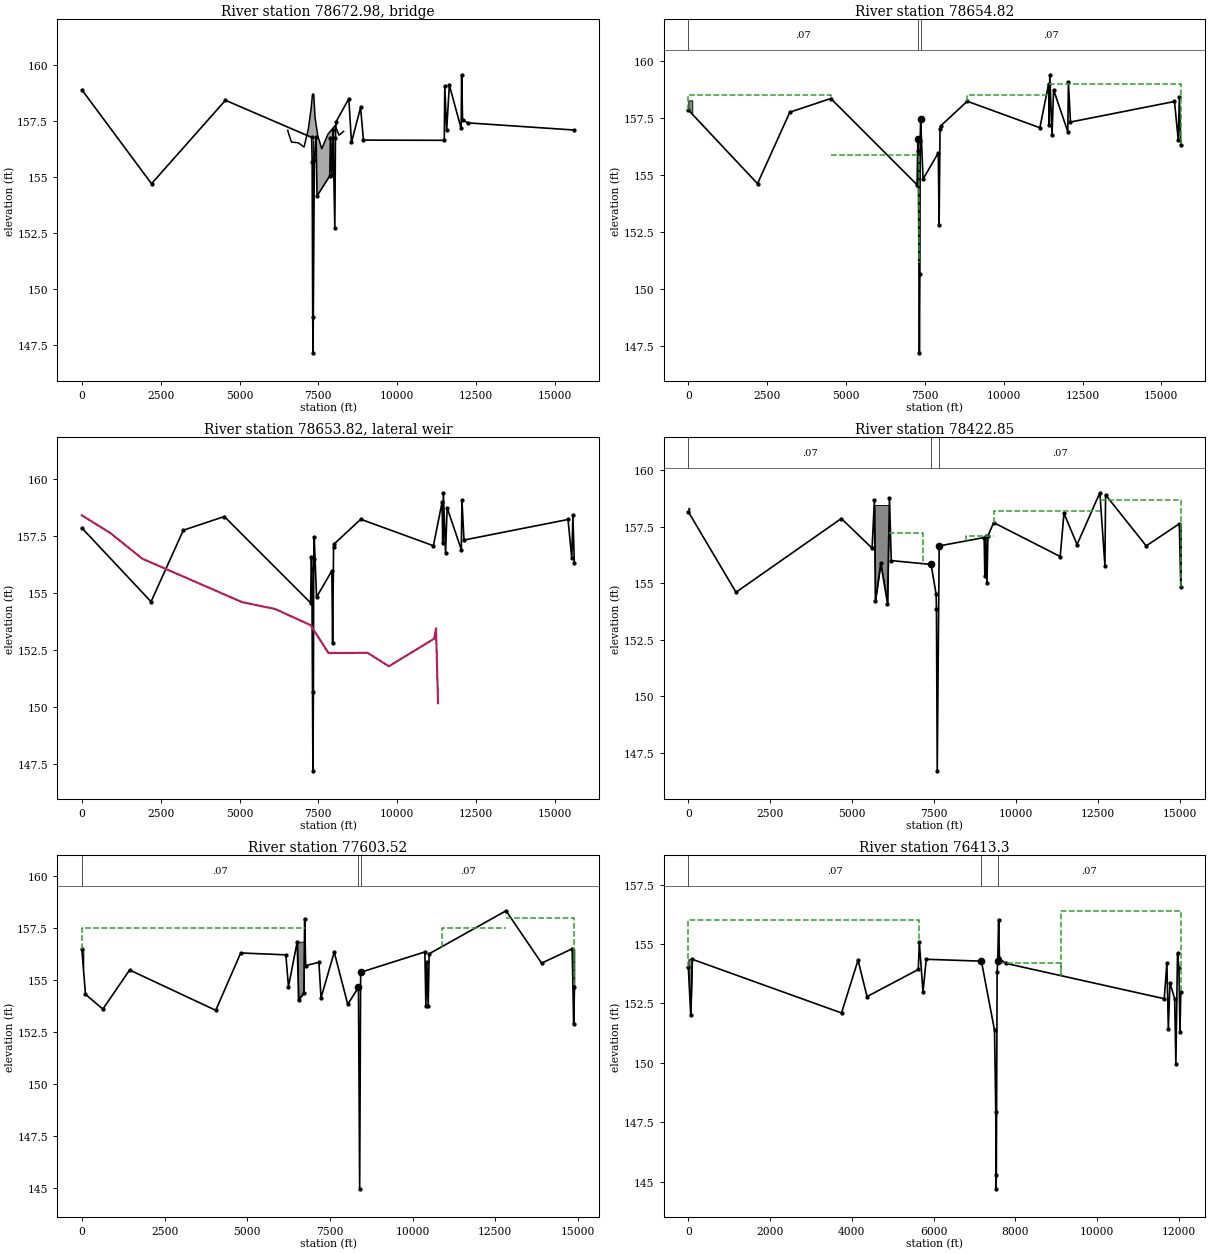
Type RM Length L Ch R = 3 ,78672.98,,,
BEGIN DESCRIPTION:
LONGENBAUGH ROAD
END DESCRIPTION:
Node Name=LONGENBAUGH ROAD
Bridge Culvert--1,0,-1,-1, 0
Deck Dist Width WeirC Skew NumUp NumDn MinLoCord MaxHiCord MaxSubmerge Is_Ogee
4,26.5,2.6,0, 20, 20, , , 0.98, 0, 0,0,,
 6527.38 6552.36  6647.2 6861.46 7045.83 7180.29 7267.39  7312.9 7322.73 7327.64
 7332.64 7347.63 7352.63 7395.08 7482.56  7607.5 7802.41 8031.93 8156.42 8300.84
  157.08  156.95  156.55  156.52  156.33  157.13  158.02  158.68  158.68 158.681
  158.69   158.7   158.7  157.65  156.83  156.25   156.9  157.29  156.86  157.03
       0       0       0       0       0       0       0  156.62  156.62 156.621
  156.63  156.64  156.64       0       0       0       0       0       0       0
 6547.37 6552.36  6647.2 6861.46 7045.83 7180.29 7267.39  7312.9 7322.73 7327.64
 7332.64 7347.63 7352.63 7395.08 7482.56  7607.5 7802.41 8031.93 8156.42 8300.84
  157.03  156.95  156.55  156.52  156.33  157.13  158.02  158.68  158.68 158.681
  158.69   158.7   158.7  157.65  156.83  156.25   156.9  157.29  156.86  157.03
       0       0       0       0       0       0       0  156.57  156.57 156.571
  156.58  156.59  156.59       0       0       0       0       0       0       0
Pier Skew, UpSta & Num, DnSta & Num=  ,7329.88, 2 ,7329.88, 2 , 0 , 0 , 0 ,,
       1       1
     146   157.6
       1       1
     146   157.6
Pier Skew, UpSta & Num, DnSta & Num=  ,7329.88, 2 ,7329.88, 2 , 0 , 0 , 0 ,,
       1       1
     146   157.6
       1       1
     146   157.6
Abutment Skew #Up #Dn= , 3 , 3
 7302.08 7311.98 7315.48
  156.62  156.62  151.15
 7302.08 7311.98 7315.48
  156.62  156.57   151.1
BR Coef=-1 , 1 , 1 ,0.9, 0 ,,,0.8,-1,1.2,0,
WSPro=,,,, 1 ,,,, 0 ,,,, 0 ,,,,-1 ,-1 ,-1 , 0 , 0 , 0 , 0 , 0
BC Design=,, 0 ,, 0 ,,,,,,
BC Use User HTab Curves=0
BC User HTab FreeFlow(D)= 0

Type RM Length L Ch R = 1 ,78654.82,265.53,231.97,697.84
BEGIN DESCRIPTION:
Downstream Section (LONGENBAUGH ROAD)
END DESCRIPTION:
Node Name=AH
XS GIS Cut Line= 6
 2987851.464766713891571.98113332987065.36889794 13885011.524766
2986497.8490356113884987.6629371 2985746.2284916 13884966.304384
2985072.7334475213884559.4833473 2980337.127433213879537.0662268
#Sta/Elev= 30
       0  157.86 2194.13  154.63 3218.72  157.76  4518.2  158.36 7253.96  154.58
 7278.52  156.57 7293.26  156.06    7327  147.22 7342.63  150.66 7352.63  156.52
 7367.62  157.47 7442.58  154.83 7927.35  155.98 7952.25  152.82 7982.12  157.01
 8002.04  157.16 8844.13  158.2411148.23  157.0811423.12  158.9911443.12   157.2
11463.11   159.411533.08  156.7811583.06  158.7412032.89  156.9112052.88  159.07
12117.85  157.3315416.56  158.2315536.52  156.53 15571.5  158.4115616.49  156.33
#Mann= 3 ,-1 , 0
       0     .07       0 7278.52     .05       0 7367.62     .07       0
#XS Ineff= 5 ,-1
       0  4518.2   158.5  4518.2 7311.98   155.9 7352.63 8844.13   155.9
 8844.1311423.12   158.511423.1215616.49  158.99
Permanent Ineff=
       F       F       F       F       F
#Block Obstruct= 2 , 0
       0  124.95  158.28 15571.5       0  158.41
Bank Sta=7278.52,7367.62
XS Rating Curve= 0 ,0
Exp/Cntr=0.5,0.3

Type RM Length L Ch R = 6 ,78653.82,,,
Lateral Weir Pos= 3
Lateral Weir Distance=0
Lateral Weir TW Multiple XS=0
Lateral Weir WD=25
Lateral Weir Coef=2
Lateral Weir WSCriteria=-1
Lateral Weir Flap Gates= 0
Lateral Weir Hagers EQN= 0 ,,,,,
Lateral Weir SS=0.05,0.05,
Lateral Weir Type= 0
Lateral Weir Connection Pos and Dist= 0 ,
Lateral Weir SE= 12
       0  158.41     900  157.64    1920  156.51    5080  154.61    6130  154.31
    7255   153.6    7820  152.38    9060  152.39    9735   151.8   11175  153.01
   11230  153.46   11295  150.18
Lateral Weir HW RS User Defined=-1
Lateral Weir HW RS Station=78654.82,0
Lateral Weir HW RS Station=78422.85,900
Lateral Weir HW RS Station=77603.52,1920
Lateral Weir HW RS Station=76413.3 ,5080
Lateral Weir HW RS Station=74758.11,6130
Lateral Weir HW RS Station=74313.45,7255
Lateral Weir HW RS Station=73108.58,7820
Lateral Weir HW RS Station=71949.68,9060
Lateral Weir HW RS Station=71324.16,9735
Lateral Weir HW RS Station=69870.13,11175
Lateral Weir HW RS Station=69031.07,11230
Lateral Weir HW RS Station=68924.32,11295
LW Div RC= 0 ,False,

Type RM Length L Ch R = 1 ,78422.85,559.88,819.34,827.93
XS GIS Cut Line= 6
2988576.6509803513891656.51836582987260.9698846913885315.1898411
2987125.0298678613884907.37996122986354.6498469413884753.2900463
2986206.7859694413884753.2900463 2981235.247684213879568.4362428
#Sta/Elev= 30
       0  158.17 1454.18  154.61  4667.4  157.87 5606.85  156.56 5676.81  158.68
 5706.79  154.22 5871.69  155.89 6076.57  154.11 6136.54  158.77 6191.51  156.01
  7407.1  155.84  7560.3  154.52 7570.17  153.89 7594.31  146.71 7654.07  156.66
 9026.17  157.03 9046.17  155.32 9076.16  157.09 9111.15  155.01 9141.15   157.1
 9316.11  157.6911345.72  156.19 11460.7   158.111860.62  156.7212555.48  159.01
12710.45  155.7912730.45  158.9213970.21  156.6614980.01  157.64   15025  154.86
#Mann= 3 , 0 , 0
       0     .07       0  7407.1     .05       0 7654.07     .07       0
#XS Ineff= 5 ,-1
       0 6136.54   157.6 6136.54 7149.22  157.24 8481.28 9316.11  157.11
 9316.1112555.48   158.212555.48   15025   158.7
Permanent Ineff=
       T       T       F       F       F
#Block Obstruct= 3 ,-1
       0   29.98  158.35 5676.81 6126.54  158.4714980.01   15025  157.64
Bank Sta=7407.1,7654.07
XS Rating Curve= 0 ,0
Exp/Cntr=0.3,0.1

Type RM Length L Ch R = 1 ,77603.52,813.28,1190.22,1625.62
Node Name=AG
XS GIS Cut Line= 6
2990284.8549130313891761.25700142987451.4173384513884819.2033003
2987158.1000116913884493.45985732986930.2300606113884142.1698774
2986256.4331798613883602.92587722982243.8700107813879590.3627081
#Sta/Elev= 30
       0  156.48  109.97  154.32  634.83  153.61 1444.62  155.49 4048.95  153.55
 4803.75  156.31 6168.39  156.22 6248.37  154.69  6513.3  156.85 6553.29  154.06
 6713.25  154.38 6738.24  157.96 6768.23   155.7 7168.13  155.86 7233.11  154.15
 7632.53  156.35 8041.06  153.84 8364.86  154.65 8401.55  144.96 8431.46  155.38
10373.74  156.3610403.74  153.7710433.74  155.8610473.73  153.7610503.73  156.27
12828.58  158.3413903.51  155.8214828.44  156.5114873.43  152.8814893.43  154.69
#Mann= 3 , 0 , 0
       0     .07       0 8364.86     .05       0 8431.46     .07       0
#XS Ineff= 4 ,-1
       0 6738.24   157.510178.7610883.71  156.1810883.7112828.58   157.5
12828.5814893.43     158
Permanent Ineff=
       T       F       F       F
#Block Obstruct= 3 ,-1
       0   44.99  156.51  6513.3 6738.24  156.8514828.4414893.43  156.51
Bank Sta=8364.86,8431.46
XS Rating Curve= 0 ,0
Exp/Cntr=0.3,0.1

Type RM Length L Ch R = 1 ,76413.3 ,1140.85,1655.19,985.54
XS GIS Cut Line= 6
2990413.4957318613890453.01519542988164.4999017713884237.1201469
2987908.1500207813883667.45002632987699.2698611213883411.1099879
 2987423.762866213882776.34682172985357.4438361113879612.2895015
#Sta/Elev= 30
       0  154.03   59.96     152   94.93  154.36  3747.3   152.1 4152.01  154.32
 4371.85  152.79 5625.94  153.93 5650.92  155.08 5740.85  152.99 5820.79  154.36
 7169.94  154.28 7490.93  151.37 7521.22  147.92    7527   144.7 7534.98  145.29
 7554.44  153.83  7568.5  154.28 7591.21  156.03 7611.12   154.4 7760.47  154.19
 11642.4   152.711707.38  154.2111742.37  151.4211782.36  153.3611897.33   152.7
11927.33  149.9611967.32  154.6112002.31  153.99 12027.3   151.3 12047.3  152.97
#Mann= 3 , 0 , 0
       0     .07       0 7169.94     .05       0  7568.5     .07       0
#XS Ineff= 4 ,-1
       0 5650.92     156 5650.92 7005.02   154.2 7591.21 9128.04   154.2
 9128.04 12047.3   156.4
Permanent Ineff=
       T       F       F       T
#Block Obstruct= 2 , 0
       0   94.93  154.3611982.31       0  154.61
Bank Sta=7169.94,7568.5
XS Rating Curve= 0 ,0
Exp/Cntr=0.3,0.1

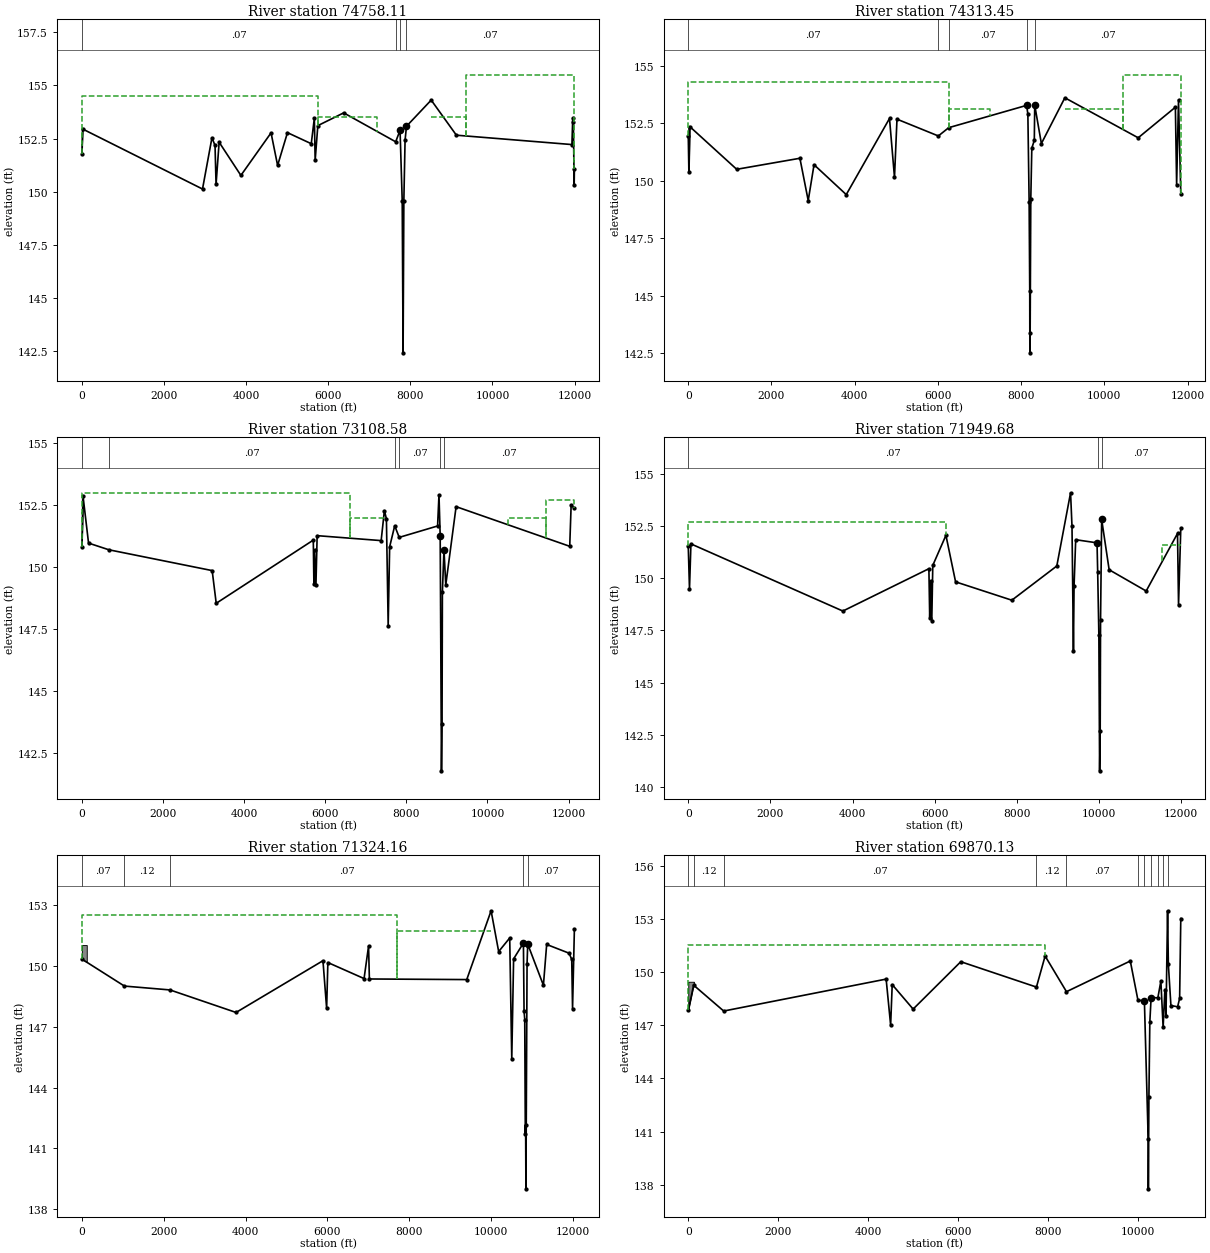
Type RM Length L Ch R = 1 ,74758.11,842.52,444.66,617.9
Node Name=AF
XS GIS Cut Line= 6
   2991267.06531   13890484.3883   2991263.07098   13889356.5146
  2989164.29875513883877.8994086 2988819.610140113883107.2900574
 2988290.6505681 13882434.592912 2986453.772352113879743.8489497
#Sta/Elev= 30
       0  151.79   19.99  152.95 2938.28  150.13 3168.14  152.54  3243.1  152.18
 3268.09  150.35 3343.04  152.33 3872.73  150.77 4607.31  152.77 4767.21  151.24
 5007.08  152.78 5586.74  152.26  5661.7  153.46 5681.69  151.48 5746.65  153.11
 6376.29  153.71 7642.73  152.35 7748.95  152.89 7801.66  149.58 7822.83  142.43
 7841.53  149.59 7871.01  152.42 7905.38  153.08 8507.41  154.31 9121.06  152.66
11934.41  152.22 11954.4  153.4711969.39  153.2711989.38  150.3211994.38  151.06
#Mann= 4 ,-1 , 0
       0     .07       0 7642.73     .12       0 7748.95     .05       0
 7905.38     .07       0
#XS Ineff= 4 ,-1
       0 5746.65   154.5 5746.65 7195.47   153.5 8507.41 9360.92   153.5
 9360.9211994.38   155.5
Permanent Ineff=
       T       T       F       F
#Block Obstruct= 2 , 0
       0   19.99  152.95 11954.4       0  153.47
Bank Sta=7748.95,7905.38
XS Rating Curve= 0 ,0
Exp/Cntr=0.3,0.1

Type RM Length L Ch R = 1 ,74313.45,1369.86,1204.87,922.93
Node Name=AE
XS GIS Cut Line= 5
2992330.0942608613890509.79690592990322.9152043613885237.3146688
2989556.3583385213883689.51691142989151.9100004413882869.9299679
2987544.9558652813879697.8319813
#Sta/Elev= 30
       0  151.94   14.99  150.37   34.98  152.35  1164.3  150.49 2683.39  150.97
 2883.27  149.13 3023.19  150.69 3797.72  149.39  4837.1   152.7 4957.02  150.14
 5016.99  152.67 6011.03  151.94 6260.63   152.3 8132.98  153.27 8162.94  152.89
 8193.34  149.06 8207.95  145.18 8210.66  142.51 8217.85  143.37 8233.07  149.18
 8257.83  151.41 8317.76  151.75 8327.75  153.28 8487.56  151.61  9051.9   153.6
10814.83  151.8611708.79  153.1911738.75  149.81 11783.7  153.5111838.63  149.42
#Mann= 5 ,-1 , 0
       0     .07       0 6011.03     .12       0 6260.63     .07       0
 8132.98     .05       0 8327.75     .07       0
#XS Ineff= 4 ,-1
       0 6260.63   154.3 6260.63 7259.05   153.1  9051.910460.25   153.1
10460.2511838.63   154.6
Permanent Ineff=
       T       T       F       F
#Block Obstruct= 2 , 0
       0   34.98  152.35 11783.7       0  153.51
Bank Sta=8132.98,8327.75
XS Rating Curve= 0 ,0
Exp/Cntr=0.3,0.1

Type RM Length L Ch R = 1 ,73108.58,779.48,1158.9,978.57
Node Name=AD
XS GIS Cut Line= 6
 2993382.569846213890531.72337132990881.1401377813884105.5600425
2990205.7799399513882366.72985882990091.8500496913882319.2601374
2990015.9000703513882300.27001792988121.3799092813879744.5700769
#Sta/Elev= 30
       0  150.81   29.98  152.85   164.9  150.97  665.77   150.7 3213.05  149.86
 3312.99  148.54 5706.56  151.09 5721.55  149.32 5736.54   150.7 5771.52  149.27
 5801.51  151.27 7379.68  151.07 7459.48  152.28 7509.36  151.95 7553.11  147.64
 7589.16  150.82 7713.86  151.67 7824.79   151.2 8771.12  151.66 8805.67  152.92
 8835.29  151.26 8867.05  141.78 8881.15  143.67 8889.67     149  8928.7   150.7
 8972.94  149.28 9227.64  152.4412029.35  150.8412064.31  152.5112144.22  152.37
#Mann= 6 ,-1 , 0
       0     .12       0  665.77     .07       0 7713.86     .12       0
 7824.79     .07       0 8835.29     .05       0  8928.7     .07       0
#XS Ineff= 4 ,-1
       0 6606.03     153 6606.03 7459.48     15210511.1311450.03     152
11450.0312144.22   152.7
Permanent Ineff=
       T       T       F       F
#Block Obstruct= 1 ,-1
       0   29.98  152.85
Bank Sta=8835.29,8928.7
XS Rating Curve= 0 ,0
Exp/Cntr=0.3,0.1

Type RM Length L Ch R = 1 ,71949.68,833.3,625.52,482.23
XS GIS Cut Line= 6
    2993863.7719   13890577.3563   2993674.58977   13888719.3797
  2990433.64989113881445.7700865 2990424.160080613881360.3299687
 2990167.809871513881037.5199188 2989367.574595413879802.8386611
#Sta/Elev= 30
       0  151.53   29.99  149.48   64.99  151.65 3764.15  148.43 5858.72  150.46
 5878.72  148.12 5903.72  149.88 5928.71  147.94 5953.71  150.62 6273.64  152.06
  6508.6  149.83 7878.33  148.95 8973.11  150.59 9308.05   154.1 9343.04  152.49
 9378.04  146.53 9393.03  149.62 9433.02  151.85 9952.44   151.7 9968.23  150.31
 9997.21  147.2710015.33  140.7710029.27  142.6710038.29     14810065.28  152.82
10247.33  150.4111148.91  149.3911911.97  152.15 11936.9  148.7211991.76  152.39
#Mann= 3 ,-1 , 0
       0     .07       0 9968.23     .05       010065.28     .07       0
#XS Ineff= 3 ,-1
       0 6273.64   152.7 6273.64 9308.05   151.811542.9111991.76  151.58
Permanent Ineff=
       T       T       F
Bank Sta=9952.44,10065.28
XS Rating Curve= 0 ,0
Exp/Cntr=0.3,0.1

Type RM Length L Ch R = 1 ,71324.16,1338.71,1454.03,1314.68
XS GIS Cut Line= 6
     2994406.016     13890595.58      2994610.21     13888699.26
  2991731.91008913883137.3700498 2990623.919851713880974.8500966
 2990496.309870713880841.1699178 2990044.489580113879832.3123554
#Sta/Elev= 30
       0  150.33 1039.72     149 2153.98  148.81 3767.78   147.7 5891.53  150.25
 5981.48   147.9 6011.46  150.16 6895.94  149.37 7005.88  150.97 7025.87  149.35
  9405.1  149.3210000.09  152.7110185.09   150.710455.09  151.3710505.09  145.39
10550.09  150.3410790.04  151.1210805.45  147.7910822.22  147.3510836.55  141.72
10843.74  142.1510851.03  139.0110879.02  150.1110894.93  151.0711278.46  149.04
11358.14  151.0511905.88  150.6211970.61  150.3111990.53  147.8812035.35   151.8
#Mann= 5 ,-1 , 0
       0     .07       0 1039.72     .12       0 2153.98     .07       0
10790.04     .05       010894.93     .07       0
#XS Ineff= 3 ,-1
       0 7700.47   152.5 7700.4710000.09   151.711617.0712035.35  150.81
Permanent Ineff=
       T       T       F
#Block Obstruct= 2 , 0
       0  119.93  151.02               0
Bank Sta=10790.04,10894.93
XS Rating Curve= 0 ,0
Exp/Cntr=0.3,0.1

Type RM Length L Ch R = 1 ,69870.13,1260.9,839.06,80.96
XS GIS Cut Line= 6
2995730.5615412713889322.58569772992269.4300121113881945.2599012
2991428.7099087813880820.81005042991390.2798675313880282.7599453
2991491.2757285213879890.79025692991201.31994361 13879543.149876
#Sta/Elev= 30
       0  147.84  118.99  149.26  787.97   147.8 4399.39   149.6 4499.38  147.01
 4534.37  149.29 4999.29  147.91 6059.12  150.58 7740.82  149.15  7933.8   150.9
 8408.57  148.89 9827.43  150.62  9997.7  148.4110141.05  148.3710225.33   140.6
10229.04  137.7810241.56  142.9810261.69  147.1810290.21  148.5510440.51  148.55
10507.34  149.4910557.67  146.8810596.67  149.0110621.48  147.5410656.22  153.45
10673.77  150.4310730.66  148.1110879.54  148.0410924.21  148.5110950.14  153.01
#Mann= 11 ,-1 , 0
       0     .07       0  118.99     .12       0  787.97     .07       0
 7740.82     .12       0 8408.57     .07       0  9997.7     .12       0
10141.05     .06       010290.21     .12       010440.51     .07       0
10557.67     .12       010673.77     .07       0
#XS Ineff= 3 ,-1
       0  7933.8   151.5  7933.8 9827.43  150.6210507.3410950.14  149.49
Permanent Ineff=
       T       T       F
#Block Obstruct= 2 , 0
       0  124.98  149.4510656.22       0     152
Bank Sta=10141.05,10290.21
XS Rating Curve= 0 ,0
Exp/Cntr=0.3,0.1