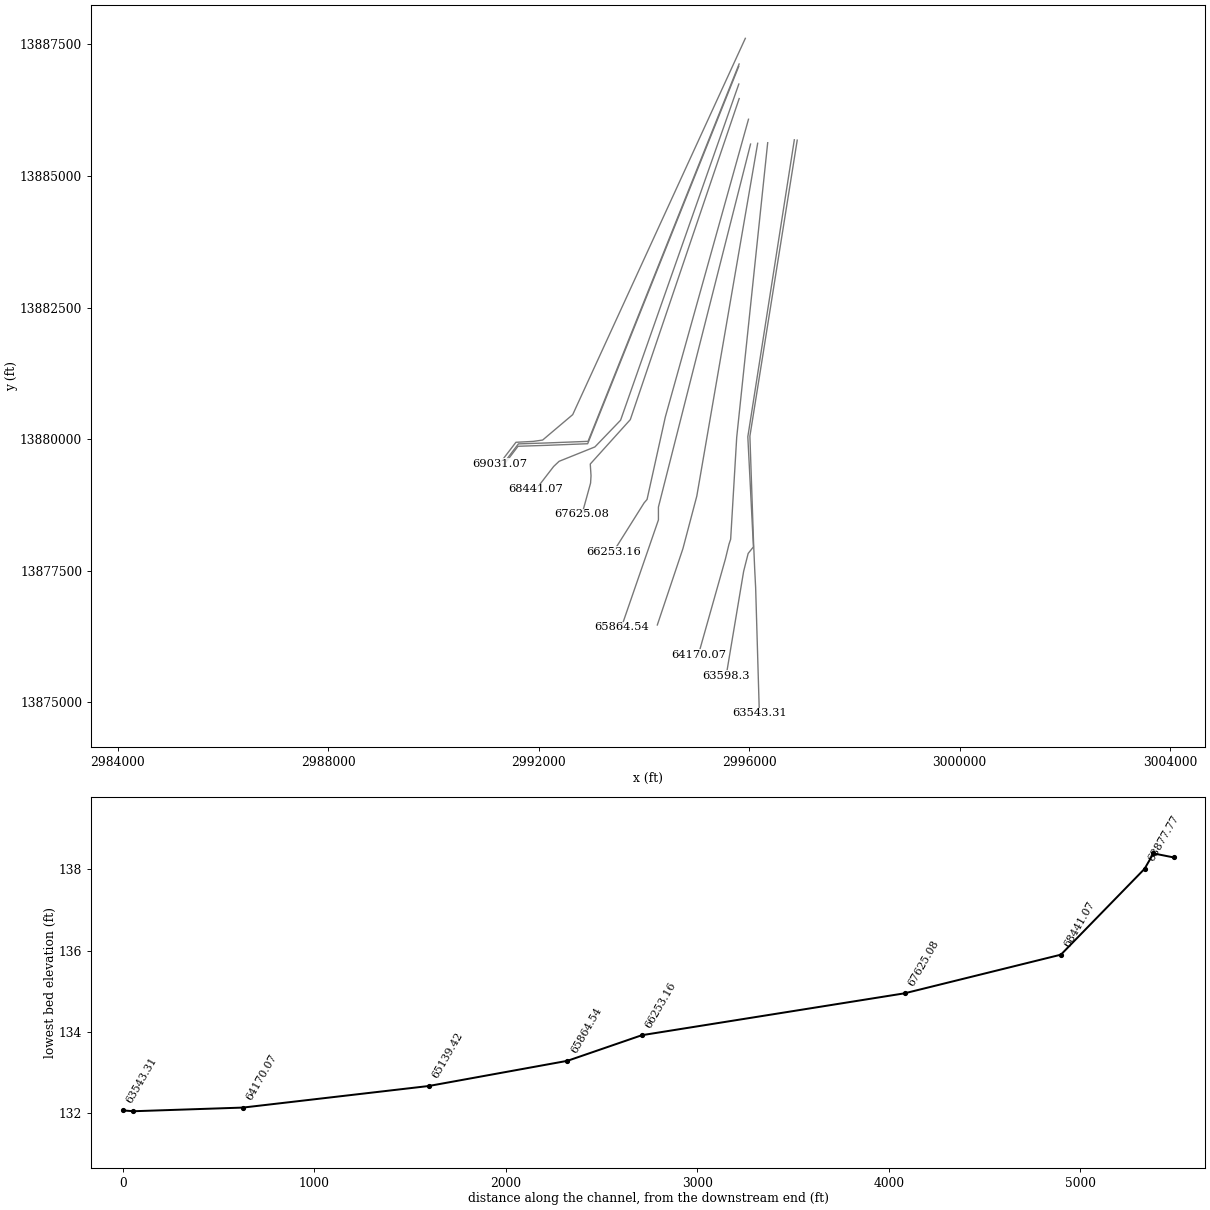
HEC-RAS study U102-00-00.prj: U102-00-00 (Update)

--- U102-00-00.g01 (geometry) --- (continued)

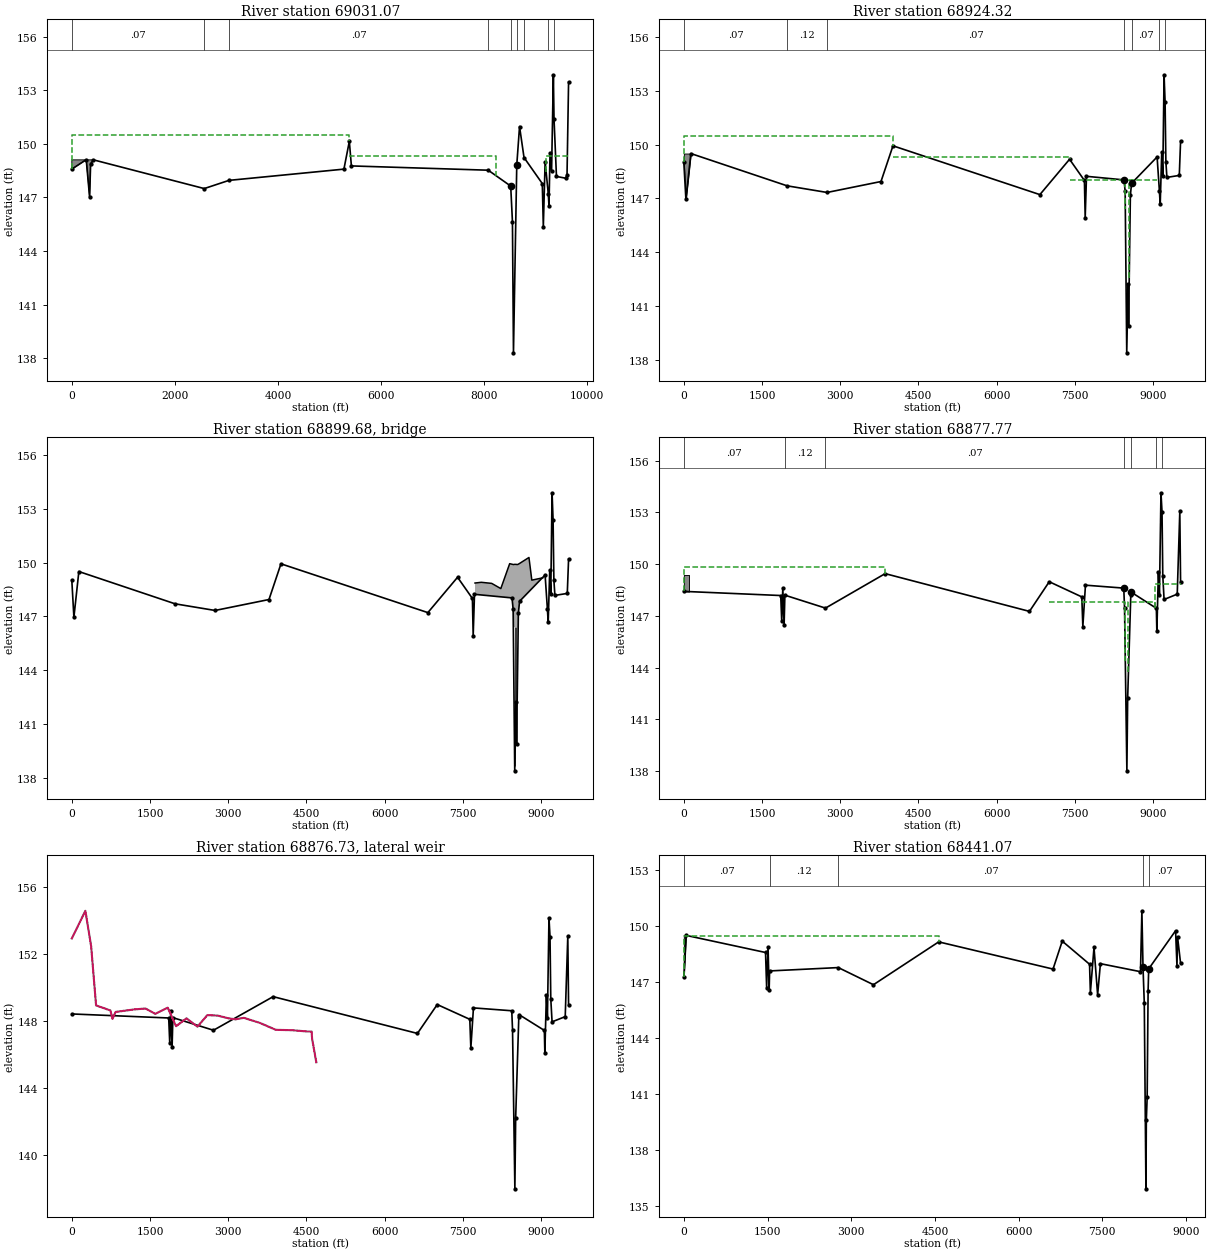
Type RM Length L Ch R = 1 ,69031.07,569.64,106.75,58.11
Node Name=AC
XS GIS Cut Line= 6
2995926.0522920313887615.48904632992644.5808366113880464.3986897
 2992072.859867213879981.25431482991893.5285329413879955.5831063
2991565.1013682813879938.82132882991254.7899810213879534.3598673
#Sta/Elev= 30
       0  148.59  279.93  149.12  344.91  147.03  364.91  148.88   419.9  149.11
 2569.22   147.5 3049.25  147.96 5278.69  148.59 5383.66  150.15 5423.65  148.77
 8078.01  148.53  8514.2  147.64 8547.99  145.64 8567.82  138.29 8631.71  148.81
 8685.57  150.98 8772.59  149.24 9127.03  147.78 9147.03  145.36 9182.01  149.01
 9243.45  147.19 9256.98  146.53 9276.97  149.49 9306.96  148.48 9341.95  153.88
 9354.51   151.4 9401.93  148.18 9581.86  148.08 9606.85  148.27 9636.83  153.46
#Mann= 9 ,-1 , 0
       0     .07       0 2569.22     .12       0 3049.25     .07       0
 8078.01     .12       0  8514.2     .06       0 8631.71     .12       0
 8772.59     .07       0 9243.45     .12       0 9354.51     .07       0
#XS Ineff= 3 ,-1
       0 5383.66   150.5 5383.66 8226.07  149.32    9202 9636.83  149.35
Permanent Ineff=
       T       T       F
#Block Obstruct= 2 , 0
       0   419.9  149.11 9341.95       0     152
Bank Sta=8514.2,8631.71
XS Rating Curve= 0 ,0
Exp/Cntr=0.5,0.3

Type RM Length L Ch R = 1 ,68924.32,10.66,46.55,77.95
BEGIN DESCRIPTION:
Upstream Section (FREEMAN (FM 529))
END DESCRIPTION:
XS GIS Cut Line= 5
 2995808.0827117 13887128.008722 2992936.218376713879956.6752957
2992161.8111328613879926.37023822991612.1055393713879908.3778201
2991321.5949655313879526.2735974
#Sta/Elev= 30
       0  149.01   39.97  146.95  134.91   149.5 1981.46   147.7 2748.55  147.33
 3782.55  147.94  4012.4  149.93 6830.63  147.21 7400.27  149.18 7685.09     148
 7700.08  145.93 7725.07  148.23 8445.07  148.03  8466.7   147.4 8497.12  138.39
 8523.39  142.23 8532.54  139.87 8566.84  147.17 8590.07  147.84 9079.76  149.31
 9123.65  147.42 9139.14  146.66 9168.83   149.6 9188.62  148.25 9213.36  153.89
 9233.03  152.37    9248  149.04 9267.79  148.17 9505.31  148.28 9530.05  150.18
#Mann= 7 ,-1 , 0
       0     .07       0 1981.46     .12       0 2748.55     .07       0
 8445.07     .06       0 8590.07     .07       0 9123.65     .12       0
 9233.03     .07       0
#XS Ineff= 5 ,-1
       0  4012.4   150.5  4012.4 7400.27  149.31 7400.27 8470.07     148
 8545.07 9079.76     148 9079.76 9530.05  149.31
Permanent Ineff=
       T       T       F       F       F
#Block Obstruct= 2 , 0
       0  134.91   149.5 9223.26       0     152
Bank Sta=8445.07,8590.07
XS Rating Curve= 0 ,0
Exp/Cntr=0.5,0.3

Type RM Length L Ch R = 3 ,68899.68,,,
BEGIN DESCRIPTION:
FREEMAN (FM 529)
END DESCRIPTION:
Node Name=FREEMAN (FM 529)
Bridge Culvert--1,0,-1,-1, 0
Deck Dist Width WeirC Skew NumUp NumDn MinLoCord MaxHiCord MaxSubmerge Is_Ogee
6,37,2.6,0, 20, 20, , , 0.98, 0, 0,0,,
 7735.07 7855.07 8055.07 8230.07 8400.07 8470.07 8475.07 8490.07 8495.07 8510.07
 8520.07 8530.07 8545.07 8560.07 8575.07 8590.07 8600.07 8770.07 8825.07 9035.07
  148.86   148.9  148.84  148.55 149.939  149.89  149.89   149.9   149.9   149.9
   149.9 149.896  149.89 149.899 149.926 149.952  149.97 150.284  149.02  149.15
       0       0       0       0       0  146.39  146.39   146.4   146.4   146.4
   146.4 146.396  146.39   14.83       0       0       0       0       0       0
 7700.08 7790.07 7990.07 8195.07 8325.07 8345.07 8400.07 8470.07 8475.07 8490.07
 8495.07 8510.07 8520.07 8530.07 8545.07 8560.07 8575.07 8695.07 8755.07 8975.07
  148.37  148.75  148.62  148.55 149.982  149.97 149.929 149.899   149.9   149.9
   149.9   149.9 149.892  149.89 149.895 149.922 149.948  150.12 150.278  149.08
       0       0       0       0       0       0       0 146.299   146.3   146.3
   146.3   146.3 146.292  146.29  74.098       0       0       0       0       0
Pier Skew, UpSta & Num, DnSta & Num=  ,8496.2, 2 ,8483.32, 2 , 0 , 0 , 0 ,,
     1.4     1.4
     138   147.5
     1.4     1.4
     138   147.4
Pier Skew, UpSta & Num, DnSta & Num=  ,8526.3, 2 ,8513.42, 2 , 0 , 0 , 0 ,,
     1.4     1.4
     138   147.5
     1.4     1.4
     138   147.4
BR Coef= 1 , 1 , 1 ,0.9, 0 ,,,0.8,-1,1.2,0,
WSPro=,,,, 1 ,,,, 0 ,,,, 0 ,,,,-1 ,-1 ,-1 , 0 , 0 , 0 , 0 , 0
BC Design=,, 0 ,, 0 ,,,,,,
BC Use User HTab Curves=0
BC User HTab FreeFlow(D)= 0

Type RM Length L Ch R = 1 ,68877.77,171.24,436.7,721.1
BEGIN DESCRIPTION:
Downstream Section (FREEMAN (FM 529))
END DESCRIPTION:
XS GIS Cut Line= 5
2995800.7736711913887082.71714592992928.9093361913879911.3837196
2992154.5020923613879881.07866212991604.79649886 13879863.086244
2991314.2859250313879480.9820213
#Sta/Elev= 30
       0  148.42  1858.8  148.18 1878.79  146.68 1898.78  148.62 1923.76  146.45
 1938.75   148.2 2717.77  147.45 3862.49  149.45 6630.75  147.26 7010.52  148.98
 7635.13   148.1 7655.11  146.38 7705.08  148.78 8440.07  148.61 8455.07  147.47
 8499.81  138.01 8515.07  142.24 8575.07  148.22 8580.07  148.38 9065.16  147.44
 9074.81   146.1  9104.5  149.56 9124.29  148.19 9153.98  154.14 9174.06  153.03
 9188.62  149.33 9213.36  147.95 9465.72  148.26 9515.21  153.06 9530.05  148.96
#Mann= 7 ,-1 , 0
       0     .07       0 1938.75     .12       0 2717.77     .07       0
 8440.07     .05       0 8575.07     .07       0 9065.16     .12       0
 9174.06     .07       0
#XS Ineff= 5 ,-1
       0 3862.49  149.85 3862.49 7010.52  148.98 7010.52 8470.07   147.8
 8530.07 9045.07   147.8 9045.07 9530.05  148.86
Permanent Ineff=
       T       T       F       F       F
#Block Obstruct= 2 , 0
       0   99.94  149.37 9168.83       0     151
Bank Sta=8440.07,8580.07
XS Rating Curve= 0 ,0
Exp/Cntr=0.5,0.3

Type RM Length L Ch R = 6 ,68876.73,,,
Node Name=Start U102 OVFL
Lateral Weir Pos= 3
Lateral Weir Distance=0
Lateral Weir TW Multiple XS=0
Lateral Weir WD=25
Lateral Weir Coef=2
Lateral Weir WSCriteria=-1
Lateral Weir Flap Gates= 0
Lateral Weir Hagers EQN= 0 ,,,,,
Lateral Weir SS=0.05,0.05,
Lateral Weir Type= 0
Lateral Weir Connection Pos and Dist= 0 ,
Lateral Weir SE= 26
       0 152.912     260 154.561     370 152.466     465 148.929     740 148.628
     780  148.13     840  148.54    1200 148.692    1415 148.742    1600 148.428
    1840 148.794    2000 147.689    2200 148.158    2410  147.66    2600  148.35
    2800 148.321    3005 148.161    3140   148.1    3300 148.188    3605  147.89
    3915 147.474    4210 147.454    4520 147.376    4600 147.376    4610 146.941
    4690 145.547
Lateral Weir HW RS User Defined=-1
Lateral Weir HW RS Station=68877.77,0
Lateral Weir HW RS Station=68441.07,780
Lateral Weir HW RS Station=67625.08,1850
Lateral Weir HW RS Station=66253.16,3150
Lateral Weir HW RS Station=65864.54,4690
LW Div RC= 0 ,False,

Type RM Length L Ch R = 1 ,68441.07,159.92,815.99,830.49
XS GIS Cut Line= 6
2995802.5853473513886747.2135518 2993554.780131713880358.2099257
2993066.62001878 13879850.720127 2992386.069870713879577.2800571
2992282.7698804413879480.06010722991946.01235186 13879043.139065
#Sta/Elev= 30
       0  147.25   39.99  149.51 1464.54  148.59 1484.54   146.7 1509.53   148.9
 1529.52  146.59 1537.45   147.6 2769.14  147.78 3398.95  146.86 4568.59  149.16
 6617.94   147.7 6782.88   149.2 7272.29  147.96 7287.27  146.44  7352.2  148.86
 7417.12  146.32 7467.06  147.99 8185.52  147.56 8210.47  150.83 8230.54   147.8
 8253.43  145.88 8283.18   135.9 8290.11  139.58 8305.03  140.82 8321.91  146.54
 8332.57  147.71 8814.54  149.76 8839.39  147.85 8849.33  149.44 8903.99  148.01
#Mann= 5 ,-1 , 0
       0     .07       0 1537.45     .12       0 2769.14     .07       0
 8230.54     .05       0 8332.57     .07       0
#XS Ineff= 2 ,-1
       0 4568.59   149.5 4568.59 6782.88   148.8
Permanent Ineff=
       T       T
#Block Obstruct= 2 , 0
       0   39.99  149.51 8814.54       0  149.76
Bank Sta=8230.54,8332.57
XS Rating Curve= 0 ,0
Exp/Cntr=0.3,0.1

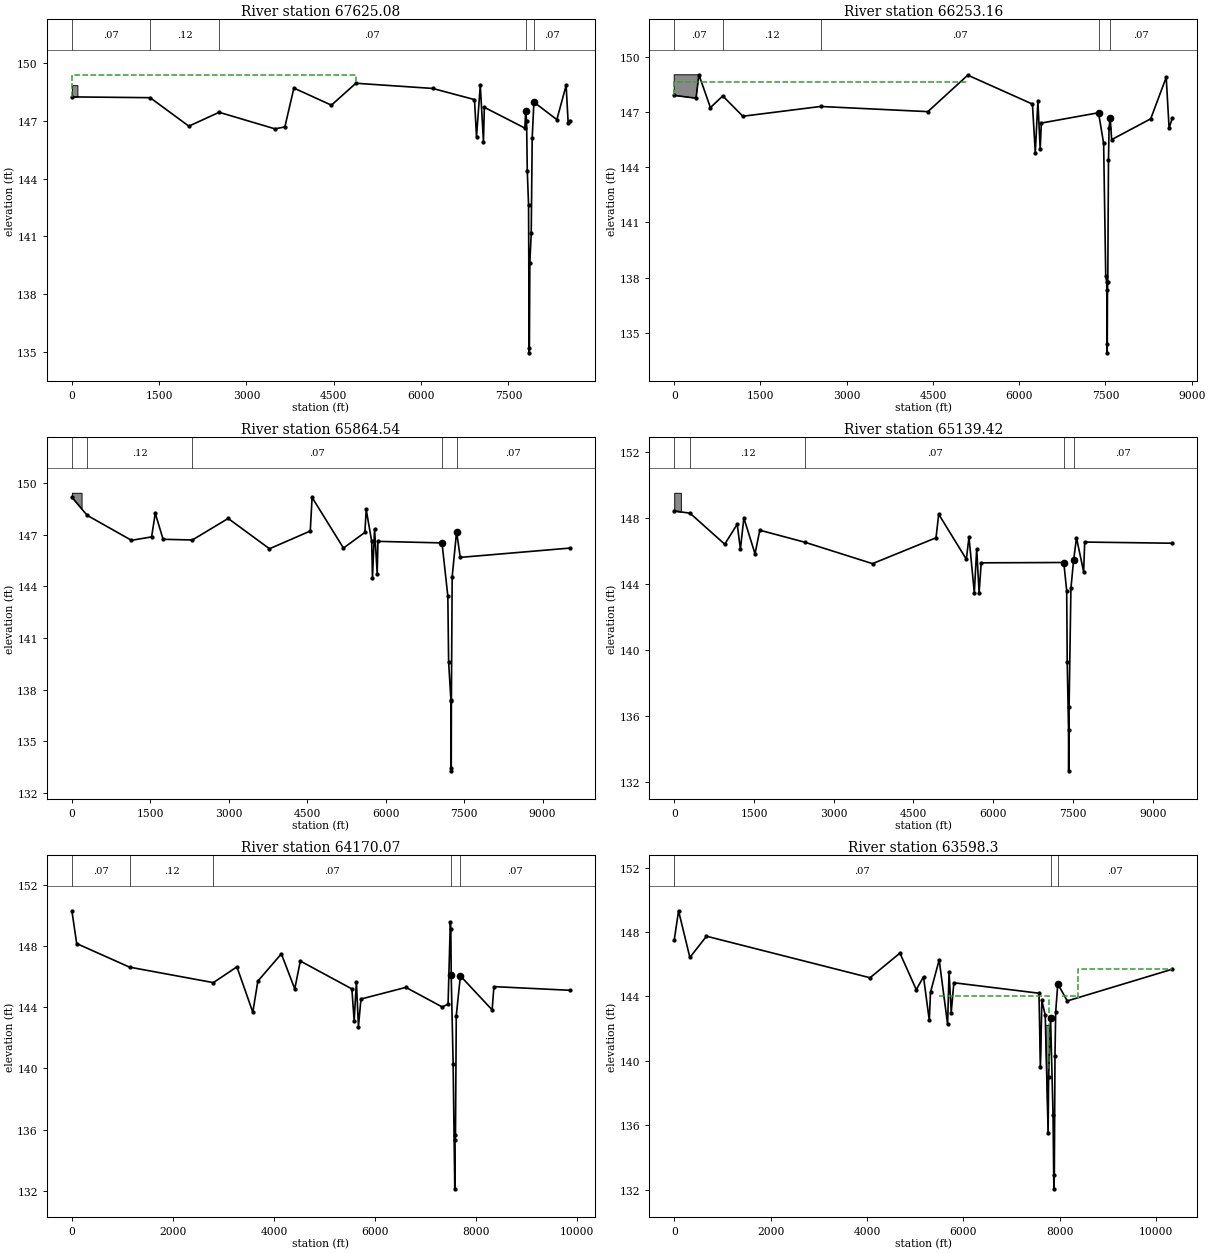
Type RM Length L Ch R = 1 ,67625.08,1073.91,1371.93,1097.22
Node Name=AB
XS GIS Cut Line= 6
2995809.2231293613886471.09927472993739.09997302 13880369.030114
2992978.2901429413879525.51014752992992.6900485313879303.3301457
2992984.1300262813879163.41999242992820.9676229513878571.5166487
#Sta/Elev= 30
       0  148.25 1344.15  148.21 2009.58  146.73 2530.25  147.45  3489.3  146.59
 3659.27  146.69 3814.24  148.71 4459.11  147.82 4879.03  148.96 6198.77  148.69
 6917.03  148.11 6951.91  146.17 7016.67  148.85 7071.48  145.93 7086.42  147.71
 7782.52  146.63 7797.36  147.54 7812.06  147.02 7824.31  144.39 7846.27  142.63
 7856.82  134.95 7860.57  135.22  7868.3  139.63 7891.99  141.16 7909.07  146.14
 7937.98  147.98 8332.16  147.07  8491.9  148.85 8526.84  146.88 8556.79  147.02
#Mann= 5 ,-1 , 0
       0     .07       0 1344.15     .12       0 2530.25     .07       0
 7797.36     .05       0 7937.98     .07       0
#XS Ineff= 2 ,-1
       0 4879.03   149.4 4879.03 6198.77  148.69
Permanent Ineff=
       T       T
#Block Obstruct= 2 , 0
       0   94.98  148.86  8491.9       0  148.85
Bank Sta=7797.36,7937.98
XS Rating Curve= 0 ,0
Exp/Cntr=0.3,0.1

Type RM Length L Ch R = 1 ,66253.16,274.64,388.61,430.15
XS GIS Cut Line= 6
 2995986.211948613886077.79067812994404.9099931113880418.9699748
2994057.6600314413878852.22015552994026.24998927 13878815.100151
2994003.4101399513878789.40007122993418.2777800313877858.7834941
#Sta/Elev= 30
       0  147.89  379.72  147.74  429.68  149.01  629.53  147.23  844.37  147.86
 1194.11  146.76 2545.04  147.29 4411.71  147.01 5106.19  148.99 6230.58  147.42
 6280.57  144.79 6325.57  147.58 6365.56  144.98 6385.56  146.39 7380.45  146.95
 7469.01  145.29 7505.84  138.07 7523.59  137.75 7529.67  133.92 7532.45   134.4
 7536.01  137.33 7541.13  137.74  7553.7   144.4 7563.44  146.12 7583.43  146.69
 7608.41  145.49 8287.97  146.62  8557.8  148.87 8607.77  146.11 8662.74  146.65
#Mann= 5 ,-1 , 0
       0     .07       0  844.37     .12       0 2545.04     .07       0
 7380.45     .05       0 7583.43     .07       0
#XS Ineff= 1 ,-1
       0 5106.19   148.6
Permanent Ineff=
       T
#Block Obstruct= 2 , 0
       0  449.66  149.01  8557.8       0  148.87
Bank Sta=7380.45,7583.43
XS Rating Curve= 0 ,0
Exp/Cntr=0.3,0.1

Type RM Length L Ch R = 1 ,65864.54,646.43,725.12,606.5
Node Name=AA
XS GIS Cut Line= 4
2996025.5429066913885605.82049342994273.9899793613878707.3398678
 2994273.987354713878463.52670722993568.1403411913876419.7896529
#Sta/Elev= 30
       0  149.17  292.98  148.12 1139.58  146.67 1524.44  146.87 1594.41  148.24
 1744.35  146.73 2304.15  146.69 2988.91  147.94 3778.63  146.18 4558.34  147.21
 4593.32  149.16 5193.09  146.22 5602.93  147.13 5627.92  148.46 5732.88  146.61
 5747.87  144.48 5787.86  147.34 5837.84  144.74 5852.83  146.61 7077.35  146.52
 7188.94  143.43 7203.82  139.63 7247.31  137.41 7251.03  133.29  7254.2  133.47
 7256.98  137.34 7271.92  144.55 7356.17  147.17 7426.07  145.68 9523.33  146.22
#Mann= 5 ,-1 , 0
       0     .07       0  292.98     .12       0 2304.15     .07       0
 7077.35     .05       0 7356.17     .07       0
#XS Ineff= 1 ,-1
       0 5627.92  148.25
Permanent Ineff=
       T
#Block Obstruct= 2 , 0
       0  184.93  149.43 9488.37       0  147.21
Bank Sta=7077.35,7356.17
XS Rating Curve= 0 ,0
Exp/Cntr=0.3,0.1

Type RM Length L Ch R = 1 ,65139.42,691.25,969.35,873.81
XS GIS Cut Line= 4
2996160.7427675313885621.18397982995003.5298588613878916.3200929
2994740.2098474513877919.43002642994252.9247327713876466.8564879
#Sta/Elev= 30
       0  148.44  297.76   148.3  949.86  146.42 1184.82  147.63 1244.82  146.12
 1309.81  148.01 1519.78  145.84 1609.76  147.27 2466.64  146.53 3729.43  145.24
 4924.28  146.81 4974.27  148.24 5494.21  145.51  5544.2  146.85 5644.19  143.47
 5689.19  146.13 5734.18  143.47 5774.17  145.29 7327.05  145.31 7381.84   143.6
  7391.8   139.3  7416.4  135.17 7419.26  132.67 7426.82  136.53 7461.54  143.74
 7511.35  145.44 7566.14  146.81 7700.62  144.75 7720.55  146.55 9367.28  146.48
#Mann= 5 ,-1 , 0
       0     .07       0  297.76     .12       0 2466.64     .07       0
 7327.05     .05       0 7511.35     .07       0
#XS Ineff= 2 ,-1
       0 4974.27   147.8 8289.26 9367.28  146.31
Permanent Ineff=
       T       F
#Block Obstruct= 2 , 0
       0  124.98  149.54               0
Bank Sta=7327.05,7511.35
XS Rating Curve= 0 ,0
Exp/Cntr=0.3,0.1

Type RM Length L Ch R = 1 ,64170.07,361.64,571.77,434.34
Node Name=Z
XS GIS Cut Line= 6
 2996351.111153213885631.66689842995762.1913992813880032.8870855
2995647.0498972813878096.51989532995616.2500901113878004.1299882
2995546.6800192713877719.02983662995032.3165466913875896.8536909
#Sta/Elev= 30
       0  150.29   94.99  148.15 1141.46  146.61 2799.83   145.6  3264.8  146.63
 3579.78  143.67 3679.77   145.7 4144.74  147.48 4409.73  145.19 4519.72  147.01
 5539.67  145.19 5584.67  143.12 5629.67  145.64 5669.63  142.73 5719.59  144.53
 6608.77  145.29 7328.11  144.01    7443   144.2 7487.96  149.58 7497.95   149.1
 7505.07  146.07 7543.06  140.31    7576  132.14 7580.67  135.34 7589.53  135.68
 7605.47  143.45 7686.83  146.04 8315.09  143.82 8350.06  145.34 9853.81   145.1
#Mann= 5 ,-1 , 0
       0     .07       0 1141.46     .12       0 2799.83     .07       0
 7505.07     .05       0 7686.83     .07       0
#XS Ineff= 2 ,-1
       0 4144.74  147.48 4144.74 4519.72  147.01
Permanent Ineff=
       F       F
Bank Sta=7505.07,7686.83
XS Rating Curve= 0 ,0
Exp/Cntr=0.3,0.1

Type RM Length L Ch R = 1 ,63598.3 ,23.8,54.99,446.27
XS GIS Cut Line= 6
2996857.63638686  13885687.554912995973.4025910213880043.9579295
2996079.9896481913877950.88435982995979.9731159513877826.5991753
2995894.0628546913877487.05687532995561.2019718613875499.3144598
#Sta/Elev= 30
       0  147.49   89.96  149.32  324.85  146.42   669.7  147.74 4063.16  145.16
  4682.9  146.69 5022.75  144.42 5172.69  145.22 5292.64  142.51 5317.63  144.26
 5497.55  146.27 5672.47  142.27 5702.46  145.53 5747.33     143 5802.14  144.85
 7568.37   144.2 7598.35   139.6 7628.34  143.75 7698.31  142.82 7758.28  135.51
 7768.27  139.01 7808.25  142.69 7860.36  136.61 7876.98  132.05 7886.73  132.91
 7900.59  140.31 7915.04  143.03  7958.4  144.78 8155.48  143.7210333.61  145.69
#Mann= 3 ,-1 , 0
       0     .07       0 7808.25     .05       0  7958.4     .07       0
#XS Ineff= 5 ,-1
       0  4682.9  146.69  4682.9 5497.55  146.27 5497.55 7773.27     144
 8037.09 8373.14     144 8373.1410333.61  145.69
Permanent Ineff=
       F       F       F       F       F
#Block Obstruct= 1 ,-1
 7568.37 7808.25  142.19
Bank Sta=7808.25,7958.4
XS Rating Curve= 0 ,0
Exp/Cntr=0.5,0.3

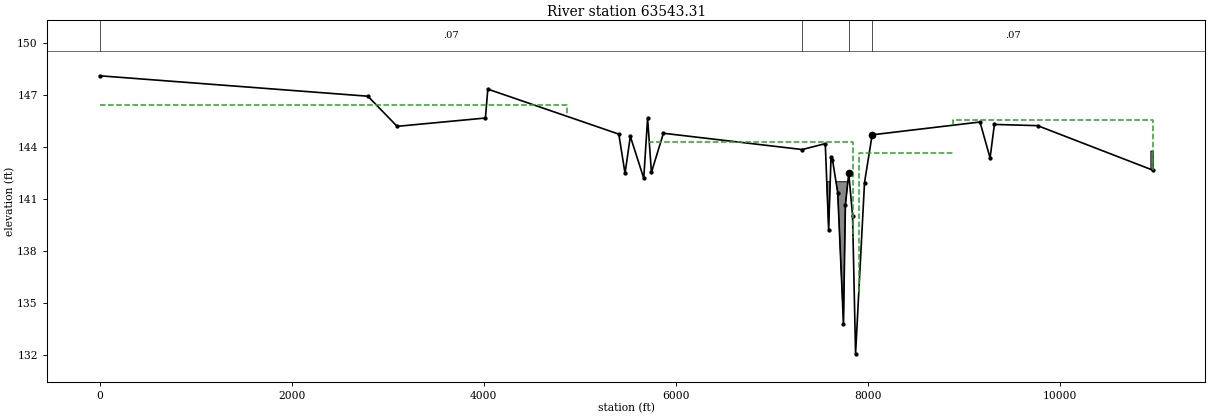
Type RM Length L Ch R = 1 ,63543.31,107.17,107.7,126.76
BEGIN DESCRIPTION:
Upstream Section (STOCKDICK SCHOOL)
END DESCRIPTION:
XS GIS Cut Line= 6
2996912.6293871113885680.82920172996012.87068795 13880055.188222
2996081.7537522813878051.14236142996103.55324936 13877538.980656
2996122.2631856913877170.13034392996192.5832550213874786.9517113
#Sta/Elev= 30
       0  148.13 2793.61  146.95 3098.46  145.21 4018.01  145.69    4043  147.36
 5407.33  144.76  5472.3  142.49 5527.27  144.63  5667.2  142.21 5707.17  145.68
 5747.07  142.55 5871.78  144.81 7317.77  143.87  7557.8  144.21 7592.71  139.25
 7617.66  143.43 7632.62  143.29 7687.49  141.38 7747.34  133.81 7767.29  140.65
  7802.2  142.51  7842.1  140.05 7873.23  132.07  7966.5  141.96 8046.05  144.72
 9169.23  145.46 9274.19  143.38 9319.18  145.32 9769.04  145.2510968.66  142.68
#Mann= 4 ,-1 , 0
       0     .07       0 7317.77     .12       0  7802.2     .06       0
 8046.05     .07       0
#XS Ineff= 5 ,-1
       0 4867.59  146.46 4867.59 5707.17  145.68 5707.17 7847.09  144.28
 7906.84 8889.31  143.69 8889.3110968.66  145.57
Permanent Ineff=
       F       F       F       F       F
#Block Obstruct= 2 ,-1
  7557.8  7802.2  142.0110943.6710968.66  143.81
Bank Sta=7802.2,8046.05
XS Rating Curve= 0 ,0
Exp/Cntr=0.5,0.3