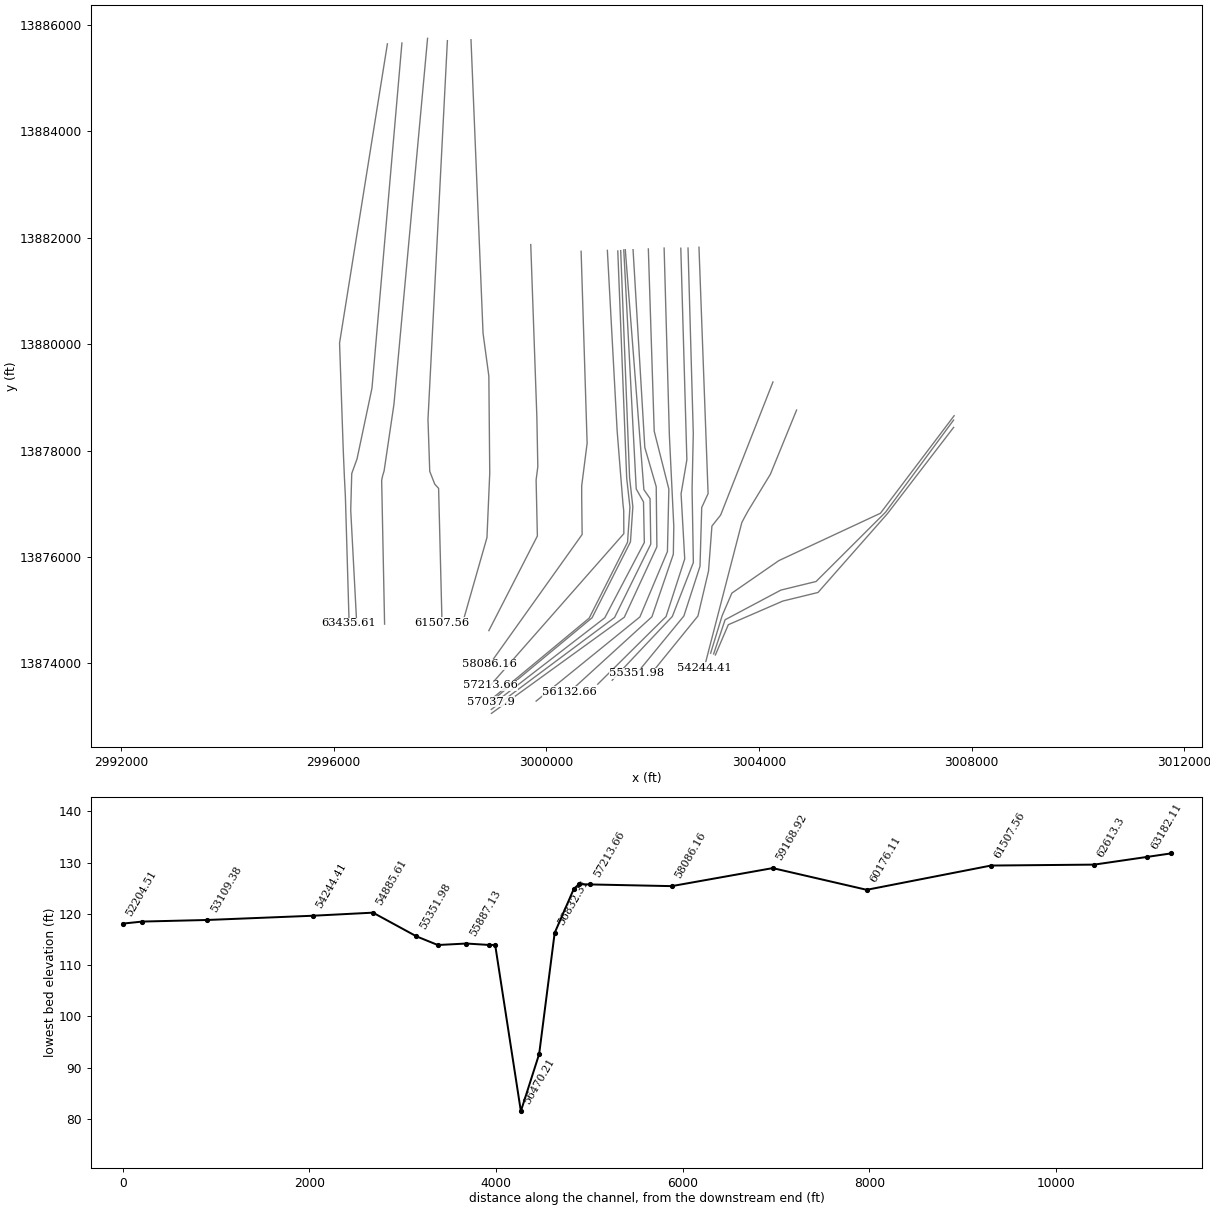
HEC-RAS study U102-00-00.prj: U102-00-00 (Update)

--- U102-00-00.g01 (geometry) --- (continued)

Type RM Length L Ch R = 3 ,63482.86,,,
BEGIN DESCRIPTION:
STOCKDICK SCHOOL
END DESCRIPTION:
Node Name=STOCKDICK SCHOOL
Bridge Culvert--1,0,-1,-1, 0
Deck Dist Width WeirC Skew NumUp NumDn MinLoCord MaxHiCord MaxSubmerge Is_Ogee
41,43,2.6,0, 24, 24, , , 0.98, 0, 0,0,,
 5762.04 5936.62 6380.58 7198.64 7702.46 7812.18 7837.11  7842.1 7847.09 7867.04
 7872.02 7877.01 7881.98  7896.9 7901.87 7906.84 7956.56 7986.39 8449.66 8749.36
 9419.1510088.9410588.7810968.66
  144.28  144.92   144.9  144.26  144.31  147.89  148.43  148.43  148.51  148.56
  148.56  148.59  148.59  148.59  148.59  148.51  145.54  144.92  143.49  143.86
  144.13  144.21  144.03   143.2
       0       0       0       0       0       0       0       0  143.71  143.76
  143.76  143.79  143.79  143.79  143.79  143.71       0       0       0       0
       0       0       0       0
 5722.13 5896.72 6365.61 7153.75 7687.49 7702.46 7812.18 7837.11  7842.1 7847.09
 7867.04 7872.02 7877.01 7881.98  7896.9 7901.87 7906.84 7956.56 8389.77 8734.36
 9394.1610008.9610568.7910953.67
  144.92  144.71  144.76  144.25  144.19  144.31  147.89  148.43  148.43  148.51
  148.56  148.56  148.59  148.59  148.59  148.59  148.51  145.54  143.41  143.79
  143.98  144.11  143.92   143.1
       0       0       0       0       0       0       0       0       0  143.45
   143.5   143.5  143.53  143.53  143.53  143.53  143.45       0       0       0
       0       0       0       0
Abutment Skew #Up #Dn= , 2 , 2
 7904.03 7909.92
  142.81  143.68
 7904.03 7909.92
  142.55  143.42
BR Coef=-1 , 0 , 0 ,0.9, 0 ,,,0.8,-1,1.2,0,
WSPro=,,,, 1 ,,,, 0 ,,,, 0 ,,,,-1 ,-1 ,-1 , 0 , 0 , 0 , 0 , 0
BC Design=,, 0 ,, 0 ,,,,,,
BC Use User HTab Curves=0
BC User HTab FreeFlow(D)= 0

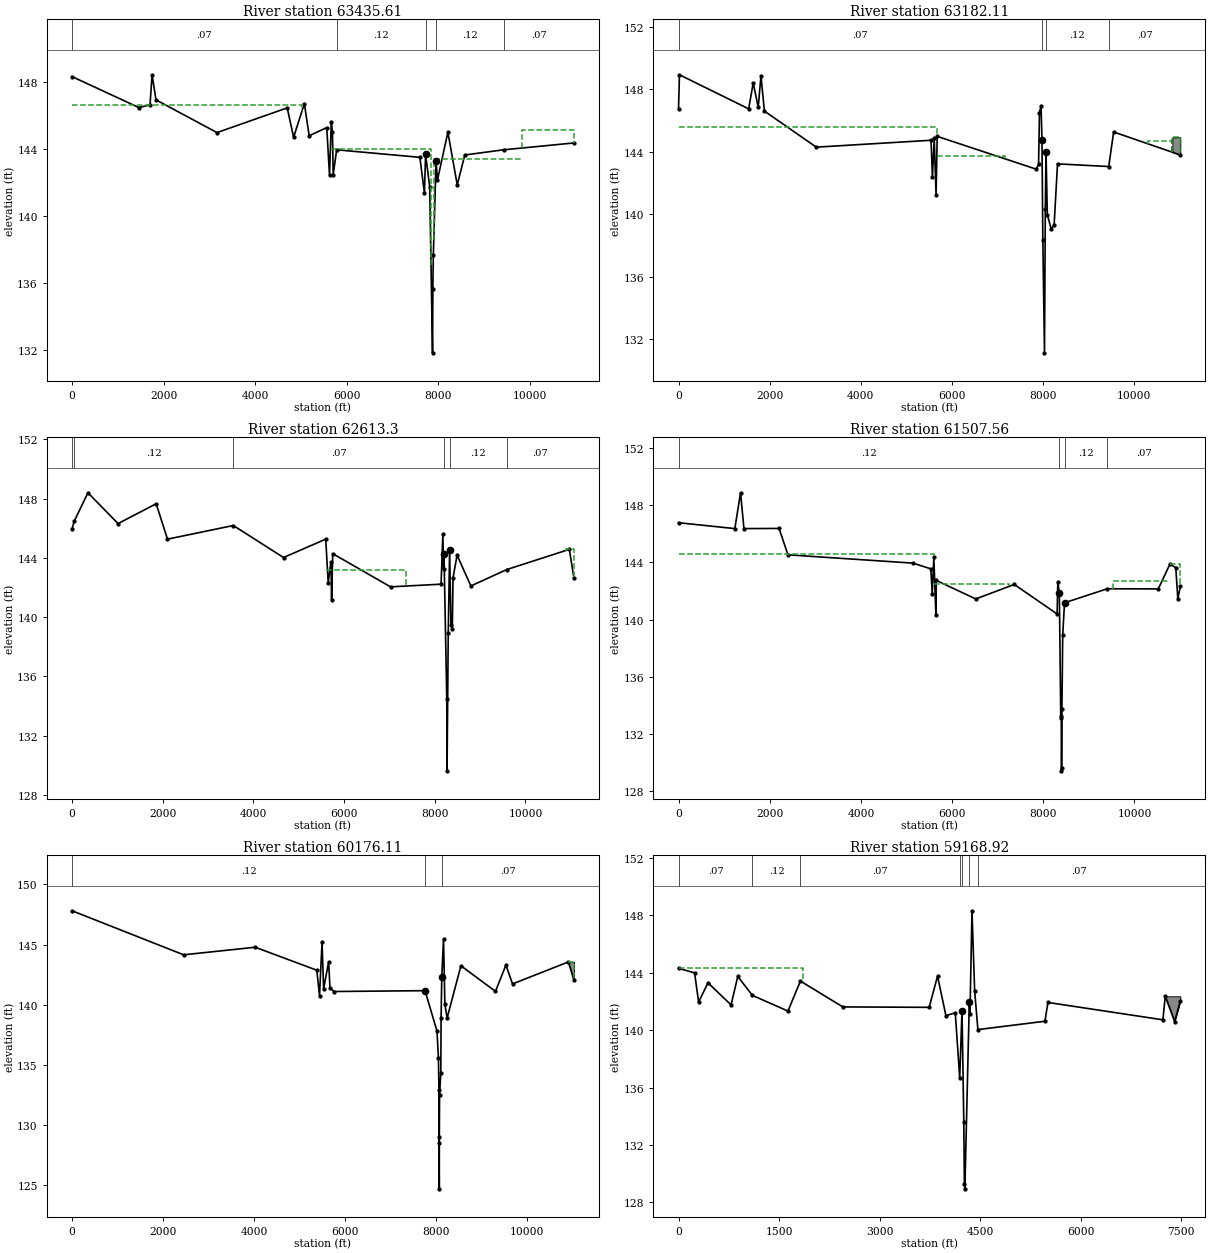
Type RM Length L Ch R = 1 ,63435.61,458.26,253.49,113.81
BEGIN DESCRIPTION:
Downstream Section (STOCKDICK SCHOOL)
END DESCRIPTION:
Node Name=Y
XS GIS Cut Line= 6
2997012.4096993713885648.23773142996112.6510001913880022.5967518
2996181.5340645313878018.55089112996203.3335616113877506.3891858
2996222.0434979513877137.53887362996292.36356728 13874754.360241
#Sta/Elev= 30
       0  148.34 1459.27  146.49 1704.15  146.65 1749.12  148.45 1834.08  146.95
 3168.43  144.99 4702.67  146.47 4842.61  144.71 5077.49  146.73 5182.44   144.8
 5567.25  145.29 5627.22  142.44  5667.2  145.63 5692.19     145 5707.17  142.47
 5784.05  143.96 7602.69  143.51 7702.46  141.38 7727.39  143.69 7817.16  141.75
 7879.35  131.81 7886.95  135.66  7896.9  137.64 7956.56  143.29 7986.39  142.15
 8215.08  145.01 8419.71  141.86 8584.41  143.65 9431.05  143.9610968.66  144.37
#Mann= 5 ,-1 , 0
       0     .07       0 5784.05     .12       0 7727.39     .06       0
 7956.56     .12       0 9431.05     .07       0
#XS Ineff= 5 ,-1
       0 5022.52  146.65 5022.52  5667.2  145.63  5667.2 7847.09     144
 7906.84 9839.02  143.41 9839.0210968.66  145.14
Permanent Ineff=
       F       F       F       F       F
Bank Sta=7727.39,7956.56
XS Rating Curve= 0 ,0
Exp/Cntr=0.5,0.3

Type RM Length L Ch R = 1 ,63182.11,493.9,568.82,632.81
XS GIS Cut Line= 6
2997285.5000324413885664.02378912996722.2252403613879172.5449742
2996441.0899758613877841.31010382996341.7601220313877567.6400475
2996322.56987169 13876876.4898552996436.1989095213874726.7356244
#Sta/Elev= 30
       0  146.76   19.99  148.92 1539.02  146.74 1638.96   148.4 1748.89  146.83
 1808.85  148.86 1883.81   146.6 3023.09  144.29 5541.48  144.73 5571.46  142.36
 5611.43  144.85  5651.4  141.21 5676.39  144.98 7851.53  142.88 7901.12  143.19
 7920.86   146.5  7955.4  146.95 7975.14  144.75 7994.88  138.32 8030.98  131.13
 8049.16  140.32 8063.96  143.97 8064.08  143.96 8093.57  139.98 8177.54  139.05
  8242.2   139.3 8316.82  143.22 9441.01  143.05 9548.32  145.2611011.87  143.79
#Mann= 4 ,-1 , 0
       0     .07       0 7975.14     .06       0 8063.96     .12       0
 9441.01     .07       0
#XS Ineff= 5 ,-1
       0 5676.39  145.55 5676.39 7158.77  143.75 8064.0810292.59  143.96
10292.5910837.05  144.7110837.0511011.87  144.92
Permanent Ineff=
       F       F       F       F       F
#Block Obstruct= 1 ,-1
10837.0511011.87  144.92
Bank Sta=7975.14,8064.08
XS Rating Curve= 0 ,0
Exp/Cntr=0.3,0.1

Type RM Length L Ch R = 1 ,62613.3 ,729.35,1105.74,1090.34
XS GIS Cut Line= 6
2997767.8845663713885751.73030662997135.2798604413878867.0400078
2996950.4101514413877616.49001542996924.1300202813877531.0699107
2996904.4200859413877439.0901078 2996959.426537613874734.4846246
#Sta/Elev= 30
       0  145.95   45.94  146.46  349.93  148.39 1014.81  146.31 1854.65  147.65
 2104.61  145.26 3555.99  146.18 4664.14  144.02 5593.98  145.26 5648.97  142.32
 5708.96  143.73 5723.96  141.18 5748.96  144.28 7023.68  142.04 8137.91  142.22
 8177.88  145.62 8192.78  143.25 8202.71  144.27 8263.88  134.45 8269.88  129.62
 8296.23  138.92 8326.67  144.55 8356.37  139.47 8386.28  139.22 8401.25  142.63
  8491.1  144.18 8795.56   142.1 9589.16  143.2110966.74  144.5711066.56  142.67
#Mann= 6 ,-1 , 0
       0     .07       0   45.94     .12       0 3555.99     .07       0
 8202.71     .06       0 8326.67     .12       0 9589.16     .07       0
#XS Ineff= 5 ,-1
       0 5593.98  145.26 5593.98 7373.44  143.21 8326.67 10477.6     143
 10477.610886.88  143.8710886.8811066.56  144.59
Permanent Ineff=
       F       F       F       F       F
#Block Obstruct= 2 , 0
       0                10886.88       0  144.59
Bank Sta=8202.71,8326.67
XS Rating Curve= 0 ,0
Exp/Cntr=0.3,0.1

Type RM Length L Ch R = 1 ,61507.56,1142.71,1331.45,904.44
XS GIS Cut Line= 6
2998140.6364455213885707.87704792997775.5604040313878582.7479254
2997808.7247077813877608.35256452997903.0900046113877366.8199111
2997975.3598731913877287.9798457 2998039.552658213874758.3395638
#Sta/Elev= 30
       0  146.76 1234.91  146.35  1359.9  148.85 1434.89  146.35 2204.84  146.36
 2399.83  144.52 5139.63  143.94 5534.59  143.54 5564.59  141.75 5599.59  144.35
 5644.58  140.34 5654.58  142.73  6519.5  141.44 7364.43  142.45 8303.88  140.39
 8318.84  142.61 8352.45  141.88  8384.1  133.11 8395.66  133.28 8396.83  129.44
 8405.38  129.63 8409.33  133.77 8426.61  138.93 8465.94  141.17 9404.88  142.15
10522.06  142.1410776.61  143.8610906.38  143.63 10951.3  141.4511006.21  142.31
#Mann= 4 ,-1 , 0
       0     .12       0 8352.45     .06       0 8465.94     .12       0
 9404.88     .07       0
#XS Ineff= 4 ,-1
       0 5599.59  144.55 5599.59 7249.43  142.47  9533.810776.61   142.7
10776.6111006.21  143.86
Permanent Ineff=
       F       F       F       F
#Block Obstruct= 2 , 0
       0                10776.61       0  143.86
Bank Sta=8352.45,8465.94
XS Rating Curve= 0 ,0
Exp/Cntr=0.3,0.1

Type RM Length L Ch R = 1 ,60176.11,911.22,1007.19,987.26
Node Name=X
XS GIS Cut Line= 6
 2998584.490216613885725.3989944 2998811.2699468 13880206.050125
 2998920.290069913879398.5500996 2998937.229996713877575.7499394
  2998884.91645313876362.3698203 2998429.380618713874766.3323299
#Sta/Elev= 30
       0  147.81 2454.55  144.15 4029.28  144.78 5384.07  142.87 5444.06  140.76
 5499.05  145.21 5534.05  141.33 5644.02  143.55 5674.02   141.4    5764   141.1
 7764.95  141.17 8027.41  137.82 8060.41  135.59 8070.25  132.91 8073.04  128.53
 8078.65   124.7 8079.66  129.04 8084.59  132.48 8112.15  134.36 8118.25  138.89
 8133.25 142.283 8171.82  145.46 8201.65  140.05 8251.36   138.9 8554.57  143.24
 9314.97  141.11 9544.54   143.3 9689.51  141.7310919.27  143.5611039.25  142.06
#Mann= 3 ,-1 , 0
       0     .12       0 7764.95     .06       0 8133.25     .07       0
#XS Ineff= 3 ,-1
       0 5499.05  144.35 9544.5410919.27   143.310919.2711039.25  143.56
Permanent Ineff=
       F       F       F
#Block Obstruct= 1 ,-1
10919.2711039.25  143.56
Bank Sta=7764.95,8133.25
XS Rating Curve= 0 ,0
Exp/Cntr=0.3,0.1

Type RM Length L Ch R = 1 ,59168.92,1003.83,1082.75,855.31
XS GIS Cut Line= 6
 2999708.320974213881873.1425914 2999823.249878213878630.0998649
 2999841.289868413877696.6401176 2999809.267294613877444.9831406
 2999832.810882713876391.7887247 2998920.514150913874611.9812607
#Sta/Elev= 30
       0  144.31  239.64  143.99  299.55  141.96  439.33   143.3  783.81  141.76
  883.66  143.74 1102.96  142.42 1632.53  141.33 1818.36  143.42 2451.29  141.62
 3739.35  141.59 3864.16  143.77 3988.98  141.01 4128.78  141.21 4194.74  136.66
 4229.07  141.36 4255.78  133.59 4264.48  129.31 4271.89  128.94 4337.99  141.93
 4347.96  141.12 4377.87  148.32 4417.75  142.74 4466.21  140.04 5466.19  140.62
 5511.16  141.93 7226.18  140.72 7261.18  142.36 7401.18   140.6 7486.18  142.03
#Mann= 7 ,-1 , 0
       0     .07       0 1102.96     .12       0 1818.36     .07       0
 4194.74     .12       0 4229.07     .06       0 4337.99     .12       0
 4466.21     .07       0
#XS Ineff= 3 ,-1
       0  1852.2   144.3  1852.2 3864.16   142.5 5511.16 7486.18  141.93
Permanent Ineff=
       F       F       F
#Block Obstruct= 1 ,-1
 7261.18 7486.18  142.36
Bank Sta=4229.07,4337.99
XS Rating Curve= 0 ,0
Exp/Cntr=0.3,0.1

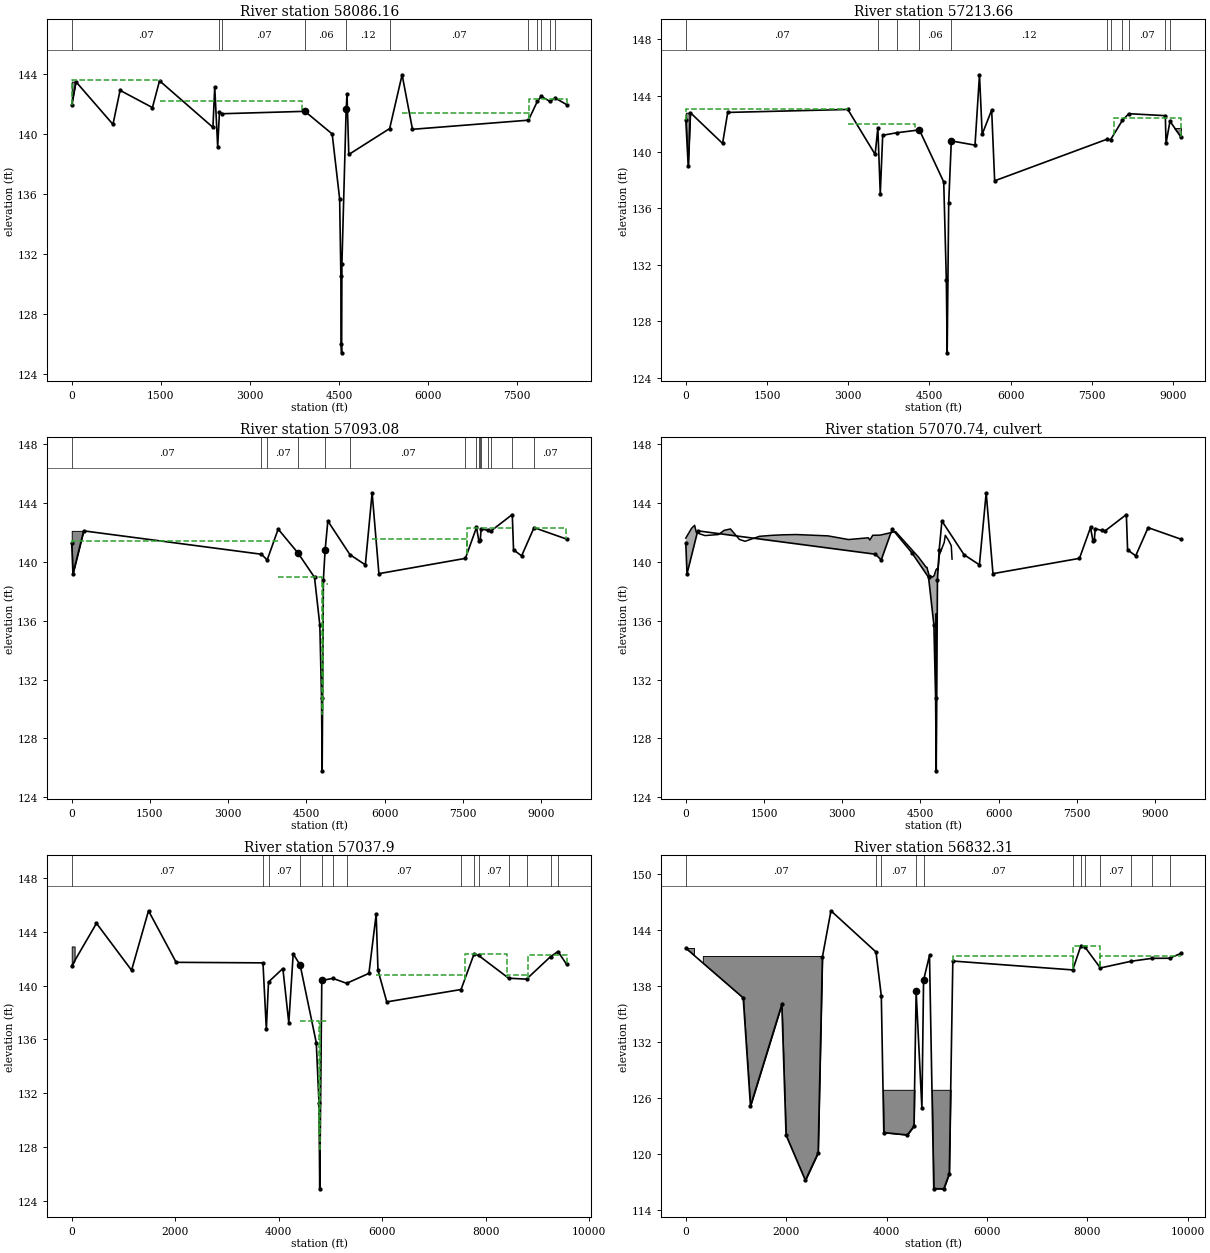
Type RM Length L Ch R = 1 ,58086.16,1002.45,872.51,800.31
Node Name=W
XS GIS Cut Line= 6
  3000655.46507713881746.9420564 3000768.620034713878136.2999994
 3000666.500160213877333.9699112 3000666.500160213877128.9801637
 3000674.857426913876420.7893229 2998933.840895913873977.6639598
#Sta/Elev= 30
       0  141.98   69.95  143.52   694.5  140.67  814.42  142.94 1359.03  141.79
 1478.94  143.58  2378.3  140.47 2408.28  143.17 2458.25  139.17 2488.22  141.49
  2536.3  141.38 3926.95  141.54 4386.27  140.03    4512   135.7 4532.86  130.56
 4537.42  126.03 4545.26  125.42 4550.48  131.38  4621.5  141.67  4636.2  142.68
  4666.2  138.66 5354.38  140.39 5564.03  143.98 5738.74  140.34 7692.49  140.95
 7842.97  142.22 7908.13  142.54  8053.4   142.2  8140.5  142.43 8334.37  141.99
#Mann= 11 ,-1 , 0
       0     .07       0 2488.22     .12       0  2536.3     .07       0
 3926.95     .06       0  4621.5     .12       0 5354.38     .07       0
 7692.49     .07       0 7842.97    .015       0 7908.13     .07       0
  8053.4    .015       0  8140.5     .07       0
#XS Ineff= 4 ,-1
       0 1478.94   143.6 1478.94 3872.03   142.2 5564.03 7699.49   141.4
 7699.49 8334.37  142.33
Permanent Ineff=
       F       F       F       T
#Block Obstruct= 2 , 0
       0   69.95  143.52               0
Bank Sta=3926.95,4621.5
XS Rating Curve= 0 ,0
Exp/Cntr=0.3,0.1

Type RM Length L Ch R = 1 ,57213.66,120.83,120.58,91.22
Node Name=V
XS GIS Cut Line= 6
 3001149.281674913881764.3229271   3001333.3800613878367.2201413
 3001442.720064513876996.1398782 3001456.630141613876870.9498398
 3001459.150805913876436.0369958 2998948.8930311 13873583.212977
#Sta/Elev= 30
       0  142.28   44.96  138.97   84.93  142.78  679.42   140.6  774.34   142.8
 2992.45  143.01 3496.72  139.82 3546.52   141.7 3591.34  137.03 3636.16  141.18
  3900.1  141.36 4313.44  141.56 4763.02  137.87 4811.47  130.89 4826.84  125.75
 4855.07  136.41 4903.52  140.78 5340.71  140.48 5423.44  145.47 5473.44  141.25
 5648.44  142.97 5703.44  137.95 7778.47   140.9 7843.48  140.86  8060.8  142.23
  8180.4  142.71 8854.83  142.57 8868.48   140.6 8940.85  142.18 9138.48  141.08
#Mann= 11 ,-1 , 0
       0     .07       0 3546.52     .12       0  3900.1     .07       0
 4313.44     .06       0 4903.52     .12       0 7778.47     .07       0
 7843.48     .07       0  8060.8    .015       0  8180.4     .07       0
 8854.83    .015       0 8940.85     .07       0
#XS Ineff= 4 ,-1
       0 2992.45  143.01 2992.45 4233.76     142 5423.44 7898.39   140.9
 7898.39 9138.48  142.38
Permanent Ineff=
       F       F       F       T
#Block Obstruct= 2 ,-1
       0   84.93  142.78 8958.48 9138.48  141.72
Bank Sta=4313.44,4903.52
XS Rating Curve= 0 ,0
Exp/Cntr=0.5,0.3

Type RM Length L Ch R = 1 ,57093.08,70.85,55.18,53.51
BEGIN DESCRIPTION:
Upstream Section (BORROW PIT ROAD)
END DESCRIPTION:
XS GIS Cut Line= 6
 3001345.197621713881752.9266244 3001512.909884713877478.2488221
 3001573.999985613876935.3279919 3001528.8881992 13876274.900507
 3000806.757753713874847.1303967  2998959.11315513873315.3962554
#Sta/Elev= 30
       0  141.29   23.31  139.19  229.15  142.12 3638.27  140.53 3748.44  140.14
 3959.33  142.24  4338.2  140.62 4656.17  138.96 4758.39  135.72 4791.24  130.77
 4803.15   125.8 4826.44   138.8 4859.15  140.79 4912.12  142.79 5336.43   140.5
 5631.35  139.81 5761.35  144.71 5891.35  139.21 7550.38  140.25 7762.86  142.35
 7809.84  141.41 7834.78   141.5 7852.88  142.27 7975.21  142.15 8042.45  142.12
 8449.41  143.23 8473.43  140.83 8628.11  140.42 8866.96  142.34 9491.28  141.56
#Mann= 15 ,-1 , 0
       0     .07       0 3638.27     .12       0 3748.44     .07       0
  4338.2     .06       0 4859.15     .12       0 5336.43     .07       0
 7550.38     .07       0 7762.86    .015       0 7809.84     .07       0
 7834.78    .015       0 7852.88     .07       0 7975.21    .015       0
 8042.45     .07       0 8449.41     .07       0 8866.96     .07       0
#XS Ineff= 7 ,-1
       0 3959.33  141.41 3959.33  4794.1  138.97  4810.6 4912.12  138.54
 5761.35 7582.26  141.56 7582.26 8449.41  142.29 8449.41 8866.96  141.56
 8866.96 9484.96  142.34
Permanent Ineff=
       F       F       F       F       T       T       T
#Block Obstruct= 1 ,-1
       0  229.15  142.12
Bank Sta=4338.2,4859.15
XS Rating Curve= 0 ,0
Exp/Cntr=0.5,0.3

Type RM Length L Ch R = 2 ,57070.74,,,
BEGIN DESCRIPTION:
BORROW PIT ROAD
END DESCRIPTION:
Node Name=BORROW PIT ROAD
Bridge Culvert--1,0,-1,-1, 0
Deck Dist Width WeirC Skew NumUp NumDn MinLoCord MaxHiCord MaxSubmerge Is_Ogee
8,35,2.6,0, 43, 43, , , 0.98, 0, 0,0,,
       0  109.85  169.31  204.22  368.75  628.02  737.72  857.38  1026.9 1136.18
 1414.13 1627.55 1847.28 2121.98 2726.31 3120.87 3500.42 3530.35 3585.22 3724.89
 4024.18 4457.44 4611.45 4621.39 4626.36 4646.23  4651.2  4666.1 4695.73 4719.65
 4748.35 4767.48 4781.84 4800.51  4817.8 4831.11 4835.79 4863.83    4957 4976.94
 5036.77 5091.62 5106.57
  141.63  142.29   142.5  141.99   141.8  141.87  142.16  142.25  141.54  141.41
  141.75  141.81  141.85  141.87  141.78  141.53  141.65   141.5  141.82  141.83
  142.07  140.36  139.64  139.64  139.64  139.32  139.32  139.08  139.08  138.97
  139.02  139.11  139.29  139.48  139.55  139.56  139.47  140.49  141.34  141.82
  141.49  141.11   140.2
       0       0       0       0       0       0       0       0       0       0
       0       0       0       0       0       0       0       0       0       0
       0       0       0       0       0       0       0       0       0       0
       0       0       0       0       0       0       0       0       0       0
       0       0       0
       0  109.85  169.31  204.22  368.75  628.02  737.72  857.38  1026.9 1136.18
 1414.13 1627.55 1847.28 2121.98 2726.31 3120.87 3500.42 3530.35 3585.22 3724.89
 4024.18 4457.44 4611.45 4621.39 4626.36 4646.23  4651.2  4666.1 4695.73 4719.65
 4748.35 4767.48 4781.84 4800.51  4817.8 4831.11 4835.79 4863.83    4957 4976.94
 5036.77 5091.62 5106.57
  141.63  142.29   142.5  141.99   141.8  141.87  142.16  142.25  141.54  141.41
  141.75  141.81  141.85  141.87  141.78  141.53  141.65   141.5  141.82  141.83
  142.07  140.36  139.64  139.32  139.32  139.32  139.08  139.08  138.95  138.97
  139.08  139.21  139.29  139.55  139.74  139.56  139.47  140.49  141.34  141.82
  141.49  141.11   140.2
       0       0       0       0       0       0       0       0       0       0
       0       0       0       0       0       0       0       0       0       0
       0       0       0       0       0       0       0       0       0       0
       0       0       0       0       0       0       0       0       0       0
       0       0       0
BR Coef=-1 , 0 , 0 ,, 0 ,,,0.8,0,,1,
WSPro=,,,, 1 ,,,, 0 ,,,, 0 ,,,,-1 ,-1 ,-1 , 0 , 0 , 0 , 0 , 0
Culvert=1,9.5,,41,0.024,0.9,1,2,3,127.01,4802.85,126.7,4791.1,Culvert #1  , 0 ,5
Culvert Bottom n=0.024
BC Design=,, 0 ,, 0 ,,,,,,
BC Use User HTab Curves=0
BC User HTab FreeFlow(D)= 0

Type RM Length L Ch R = 1 ,57037.9 ,134.08,205.59,238.81
BEGIN DESCRIPTION:
Downstream Section (BORROW PIT ROAD)
END DESCRIPTION:
XS GIS Cut Line= 6
 3001399.920281313881759.4148004 3001567.632544313877484.7369981
 3001628.722645213876941.8161679 3001583.6108588 13876281.388683
 3000861.480413313874853.6185727 2998960.551144313873277.7106353
#Sta/Elev= 30
       0  141.47  478.44  144.63 1156.04  141.14 1483.61  145.56 2017.09  141.73
 3694.54  141.69 3759.81  136.75 3801.64  140.27 4079.05  141.27 4193.78  137.23
 4278.58  142.36 4412.72  141.53 4724.43  135.76 4777.05  131.28  4791.4   124.9
 4831.11  140.38 5044.06  140.54 5310.91  140.17 5741.35  140.91 5881.35   145.3
 5916.35  141.15 6086.35  138.79 7521.22  139.71 7772.37  142.35 7860.25  142.24
 8440.94  140.55 8785.83  140.48 9252.08  142.16 9394.13  142.53 9560.58  141.58
#Mann= 14 ,-1 , 0
       0     .07       0 3694.54     .12       0 3801.64     .07       0
 4412.72     .06       0 4831.11     .07       0 5044.06     .12       0
 5310.91     .07       0 7521.22     .07       0 7772.37    .015       0
 7860.25     .07       0 8440.94     .07       0 8785.83     .07       0
 9252.08    .015       0 9394.13     .07       0
#XS Ineff= 7 ,-1
       0 4412.72  141.31 4412.72 4782.35   137.4 4798.85 4952.01   137.4
 5881.35 7589.14   140.8 7589.14 8399.69  142.33 8399.69 8811.34   140.8
 8811.34 9560.58  142.28
Permanent Ineff=
       F       T       T       F       T       T       T
#Block Obstruct= 2 , 0
       0   55.93  142.91               0
Bank Sta=4412.72,4831.11
XS Rating Curve= 0 ,0
Exp/Cntr=0.5,0.3

Type RM Length L Ch R = 1 ,56832.31,164.47,166.12,123.59
XS GIS Cut Line= 6
 3001457.846018513881772.6913487 3001692.095549913877277.1767177
 3001828.808859213877033.1594892 3001844.588355213876270.1885742
 3001100.868057913874853.5447539 2998963.364786913873203.9752184
#Sta/Elev= 30
       0  142.04 1143.62  136.72 1288.44  125.14 1912.69  136.02 1997.59  122.02
 2382.12  117.19 2636.81  120.13 2721.71   141.1  2891.5  146.04 3788.72  141.63
 3894.65  136.93 3944.43   122.3 4412.18  122.05 4545.14  122.98 4588.54  137.41
 4703.26  124.88  4736.5  138.62 4854.65  141.26 4939.59   116.3 5139.46  116.28
 5249.39  117.91 5319.35  140.66 7707.82  139.71    7870   142.3 7945.65   142.2
 8257.82  139.92 8872.82  140.64 9287.82  140.95 9637.82  140.96 9857.82  141.47
#Mann= 12 ,-1 , 0
       0     .07       0 3788.72     .12       0 3894.65     .07       0
 4588.54     .06       0  4736.5     .07       0 7707.82     .07       0
    7870    .015       0 7945.65     .07       0 8257.82     .07       0
 8872.82     .07       0 9287.82     .07       0 9637.82     .07       0
#XS Ineff= 6 ,-1
       0 3690.52   141.2 3690.52 4588.54   136.5 4750.27 5319.35   136.5
 5319.35 7711.32   141.2 7711.32 8247.24  142.23 8247.24 9857.82   141.2
Permanent Ineff=
       F       T       T       F       T       T
#Block Obstruct= 4 ,-1
       0   164.8  142.04  339.59 2776.64   141.2 3788.72 4583.71  126.88
 4834.66 5319.35  126.88
Bank Sta=4588.54,4736.5
XS Rating Curve= 0 ,0
Exp/Cntr=0.3,0.1

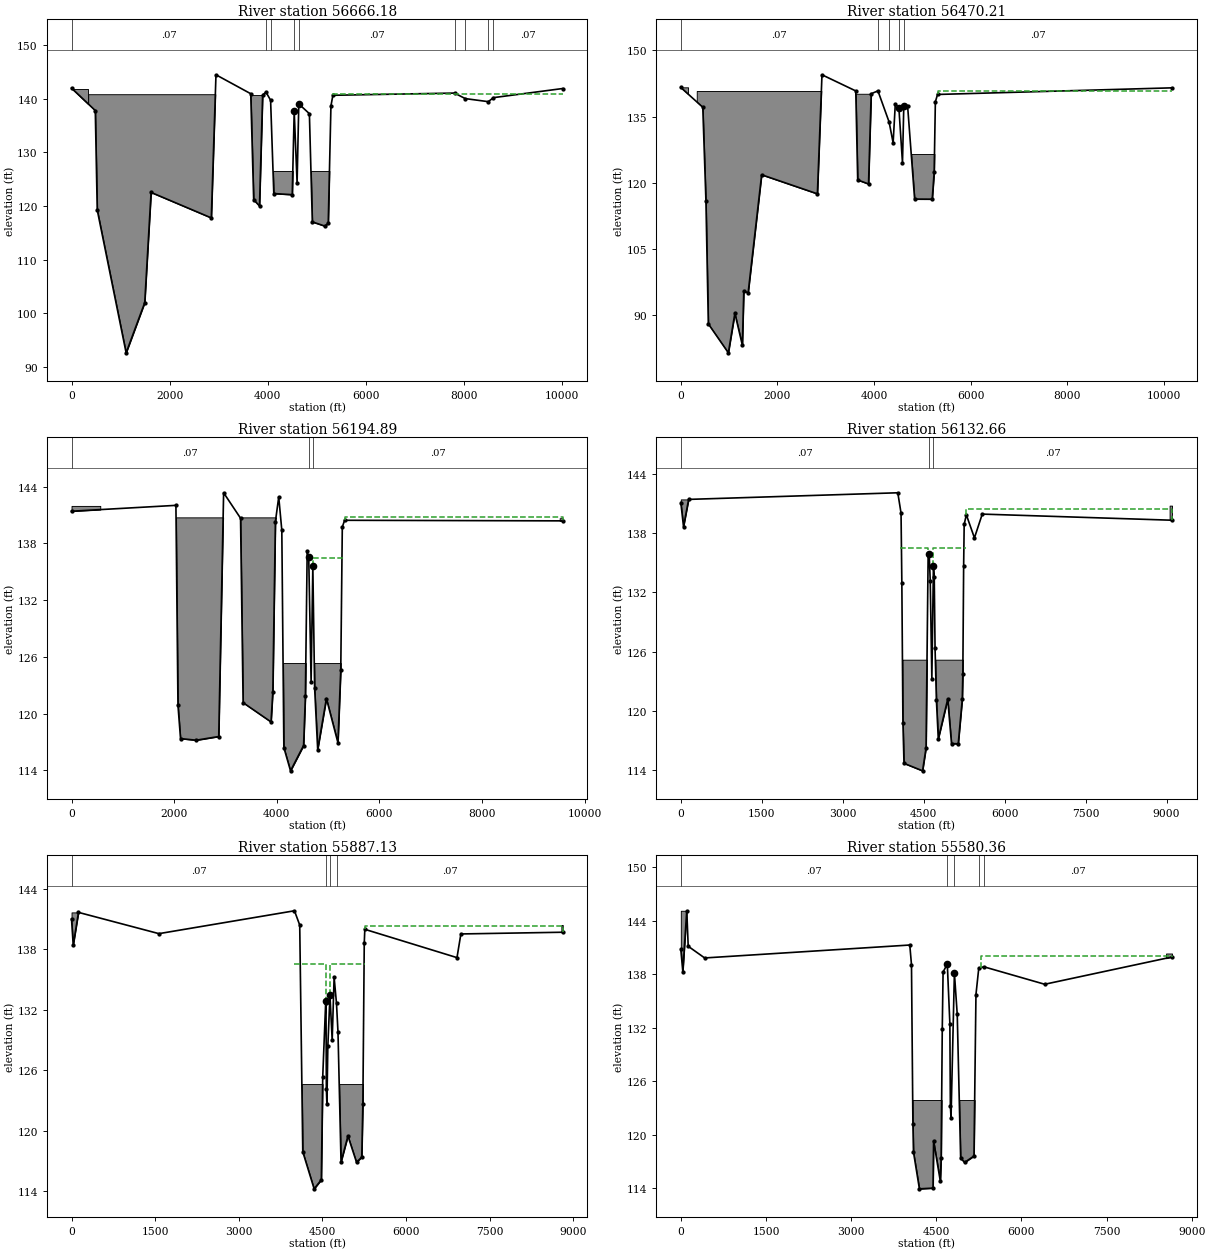
Type RM Length L Ch R = 1 ,56666.18,189.4,195.97,113.68
Node Name=U
XS GIS Cut Line= 6
 3001486.683887313881776.0443604 3001835.962388213877264.4592234
 3001952.009728313877095.9520145 3001965.690147113876239.3986095
 3001284.563556613874859.0782074  2998966.18761613873130.0009569
#Sta/Elev= 30
       0  141.97  484.39  137.77  524.34  119.24  1113.6   92.63 1493.13  101.98
 1622.96  122.52 2851.43  117.77 2946.32  144.44 3655.44  140.91 3715.36  121.17
 3834.25  119.98 3898.39  140.67 3966.32  141.21 4060.52   139.7  4125.8  122.31
 4502.39   122.1 4542.15  137.64 4601.02   124.3  4635.7  139.01 4851.88  137.19
 4911.84  117.03 5166.66  116.25 5236.62  116.76 5291.58  138.66 5331.55  140.62
 7812.17  141.03 8031.96     140  8501.5  139.43 8606.39  140.1810020.01  141.88
#Mann= 9 ,-1 , 0
       0     .07       0 3966.32     .12       0 4060.52     .07       0
 4542.15     .06       0  4635.7     .07       0 7812.17     .07       0
 8031.96     .07       0  8501.5     .07       0 8606.39     .07       0
#XS Ineff= 4 ,-1
       0 3972.39   140.8 3972.39 4542.15   136.5 4652.03 5331.55   136.5
 5331.5510020.01   140.8
Permanent Ineff=
       F       T       T       F
#Block Obstruct= 5 ,-1
       0  339.57  141.82  339.57 2946.32  140.82 3655.44 3898.39  140.67
 4060.52 4542.51  126.52 4841.89 5331.55  126.52
Bank Sta=4542.15,4635.7
XS Rating Curve= 0 ,0
Exp/Cntr=0.3,0.1

Type RM Length L Ch R = 1 ,56470.21,232.84,275.32,222.93
XS GIS Cut Line= 6
 3001632.414238913881777.0486234 3001853.705134913878056.1863145
 3002068.339876213877318.2301133 3002080.584930513876188.0132136
 3001468.2587273 13874864.611989 2998969.010444913873056.0266954
#Sta/Elev= 30
       0  141.59  454.69  137.11  519.64  115.97  569.61   88.02  984.32   81.46
 1119.23   90.41 1274.12    83.2  1304.1   95.43 1394.04   95.06 1673.85  121.81
 2828.05  117.49 2922.99  144.47  3622.5  140.81 3662.47  120.64 3887.12  119.72
 3942.01  140.17 4081.12  140.83 4312.86  133.77 4396.16  129.05 4441.07  137.82
 4515.24  137.01 4589.96  124.52 4616.79  137.29 4696.28  137.36 4841.16   116.3
 5205.86  116.28 5245.83  122.33 5270.81  138.35 5315.77  140.0110171.32  141.51
#Mann= 5 ,-1 , 0
       0     .07       0 4081.12     .12       0 4312.86     .07       0
 4515.24     .06       0 4616.79     .07       0
#XS Ineff= 4 ,-1
       0 4081.12  140.83 4081.12 4515.24   136.5 4646.52 5315.77   136.5
 5315.7710171.32   140.8
Permanent Ineff=
       F       T       T       F
#Block Obstruct= 4 ,-1
       0   149.9  141.63  329.77 2922.99   140.8  3622.5 3942.01  140.17
    4646 5295.79  126.52
Bank Sta=4515.24,4616.79
XS Rating Curve= 0 ,0
Exp/Cntr=0.3,0.1

Type RM Length L Ch R = 1 ,56194.89,96.74,62.23,94.91
XS GIS Cut Line= 6
 3001919.945159913881790.5794363 3002030.306487713878363.1650313
 3002305.809873713877273.4201635 3002278.839127113876099.3460681
  3001760.55210613874869.2343551 2999809.671165213873286.8598952
#Sta/Elev= 30
       0   141.4 2034.53  142.02 2074.52  120.87 2124.51  117.35 2429.43  117.18
 2869.33  117.57  2964.3  143.35 3294.22  140.66 3344.21  121.15  3888.8  119.11
 3923.77  122.33 3973.72   140.3 4038.67  142.91 4098.62  139.39 4138.58   116.4
 4268.48  113.94 4523.26  116.62 4558.23  121.83 4593.21  137.15 4623.18  136.56
 4669.75  123.34 4703.12  135.62  4738.1  122.71 4798.06  116.19 4967.93  121.59
 5192.77  116.91 5247.73  124.61 5277.71  139.73 5322.67  140.44 9574.46  140.38
#Mann= 3 ,-1 , 0
       0     .07       0 4623.18     .06       0 4703.12     .07       0
#XS Ineff= 4 ,-1
       0 4038.67  140.75 4038.67  4598.2   136.5 4703.12 5322.67   136.5
 5322.67 9574.46  140.75
Permanent Ineff=
       F       T       T       F
#Block Obstruct= 6 ,-1
       0  559.87  141.96 2034.53  2964.3  140.75 3279.23 4013.69  140.75
 4083.63  4593.2  125.34 4703.12 5322.67  125.34 9514.53 9574.46  140.66
Bank Sta=4623.18,4703.12
XS Rating Curve= 0 ,0
Exp/Cntr=0.3,0.1

Type RM Length L Ch R = 1 ,56132.66,252.8,245.53,203.03
XS GIS Cut Line= 6
 3002216.778555713881807.4183134 3002315.499158813878286.3823764
 3002398.620055513876575.1499065 3002390.040676413876049.6125718
  3001987.51621913874872.8235868 3000438.250616713873459.4586314
#Sta/Elev= 30
       0  141.11   49.96  138.67  144.89  141.43 4020.84   142.1 4080.65  140.04
  4095.6  132.97 4115.54  118.81 4135.48  114.69 4479.39  113.93 4544.19  116.25
 4583.23  135.94 4602.61  135.85 4621.99  133.15  4651.5  123.19  4680.9  134.67
 4695.89  133.58 4710.88  126.39 4735.88  121.09 4770.86  117.17 4945.79  121.19
 5015.77  116.69 5140.72  116.67 5215.69  121.19 5225.68  123.74 5240.68  134.67
 5250.68   138.9 5290.67  139.87 5440.66  137.53 5585.65  139.94 9102.11  139.32
#Mann= 3 ,-1 , 0
       0     .07       0 4602.61     .06       0  4680.9     .07       0
#XS Ineff= 4 ,-1
       0 4055.73   140.5 4055.73 4588.07   136.5  4680.9 5290.67   136.5
 5290.67 9102.11   140.5
Permanent Ineff=
       F       T       T       F
#Block Obstruct= 4 ,-1
       0  144.89  141.43 4055.73 4588.07  125.19  4680.9 5290.67  125.19
 9057.17 9102.11   140.8
Bank Sta=4602.61,4680.9
XS Rating Curve= 0 ,0
Exp/Cntr=0.3,0.1

Type RM Length L Ch R = 1 ,55887.13,155.82,306.77,177.67
XS GIS Cut Line= 6
 3002530.525631613881804.1102491 3002644.568054413877825.6861193
 3002535.636513813877185.1788702 3002604.305667813875960.9277098
  3002253.31129113874877.0266623 3000968.6370231 13873605.094823
#Sta/Elev= 30
       0  140.98   29.96   138.4  124.84  141.65 1568.06  139.54 3999.98  141.81
 4094.46  140.39 4149.16  117.89 4353.04  114.21 4482.34  115.11  4507.2   125.3
 4561.06  132.84 4565.83  132.62 4572.49  124.13 4582.16  122.61 4599.18  128.38
 4637.29  133.41 4676.97  128.97 4711.69  135.21 4754.43  132.61 4781.13  129.77
 4835.69  116.87  4959.7  119.46 5113.46  116.85  5207.7  117.36 5227.54  122.63
  5252.5  138.59  5262.5  139.97 6916.31  137.16 6986.27  139.51 8814.07  139.68
#Mann= 4 ,-1 , 0
       0     .07       0 4561.06     .06       0 4637.29     .12       0
 4754.43     .07       0
#XS Ineff= 4 ,-1
       0 3999.98  140.25 3999.98 4561.06   136.5 4637.29  5262.5   136.5
  5262.5 8814.07  140.25
Permanent Ineff=
       F       T       T       F
#Block Obstruct= 4 ,-1
       0  124.84  141.65 4089.49 4561.06  124.61 4711.69  5262.5  124.61
  8789.1 8814.07   140.4
Bank Sta=4561.06,4637.29
XS Rating Curve= 0 ,0
Exp/Cntr=0.3,0.1

Type RM Length L Ch R = 1 ,55580.36,345.24,228.38,168.45
XS GIS Cut Line= 6
 3002666.506002713881807.4183134 3002765.226605813878319.2894628
 3002742.587543413877270.8125572  3002766.57798113875893.7624898
 3002370.928509913874878.8865668 3001239.8546565 13873679.567115
#Sta/Elev= 30
       0  140.76      35  138.29  104.99   145.1  129.98  141.12  419.94  139.81
 4033.84  141.26  4063.8  139.06 4088.77  121.24 4098.76  118.05 4203.63  113.92
 4443.35     114 4453.34  119.29 4572.16  114.77 4586.69  117.42 4606.07  131.79
 4620.61  138.24 4694.97  139.12 4739.95  132.46 4748.86  123.23 4760.64  121.88
 4819.92  138.12  4869.9  133.48 4929.87  117.36 4999.85  116.88 5164.78   117.6
 5199.77  135.71 5248.89  138.65 5339.17  138.82    6411  136.86 8654.14  139.92
#Mann= 5 ,-1 , 0
       0     .07       0 4694.97     .06       0 4819.92     .07       0
 5248.89     .12       0 5339.17     .07       0
#XS Ineff= 4 ,-1
       0 3928.97  140.05 3928.97 4694.97   136.5 4819.92 5284.75   136.5
 5284.75 8654.14  140.05
Permanent Ineff=
       F       T       T       F
#Block Obstruct= 4 ,-1
       0  104.99   145.1 4033.84 4694.97  123.88 4819.82 5284.75  123.88
 8549.23 8654.14  140.31
Bank Sta=4694.97,4819.92
XS Rating Curve= 0 ,0
Exp/Cntr=0.3,0.1

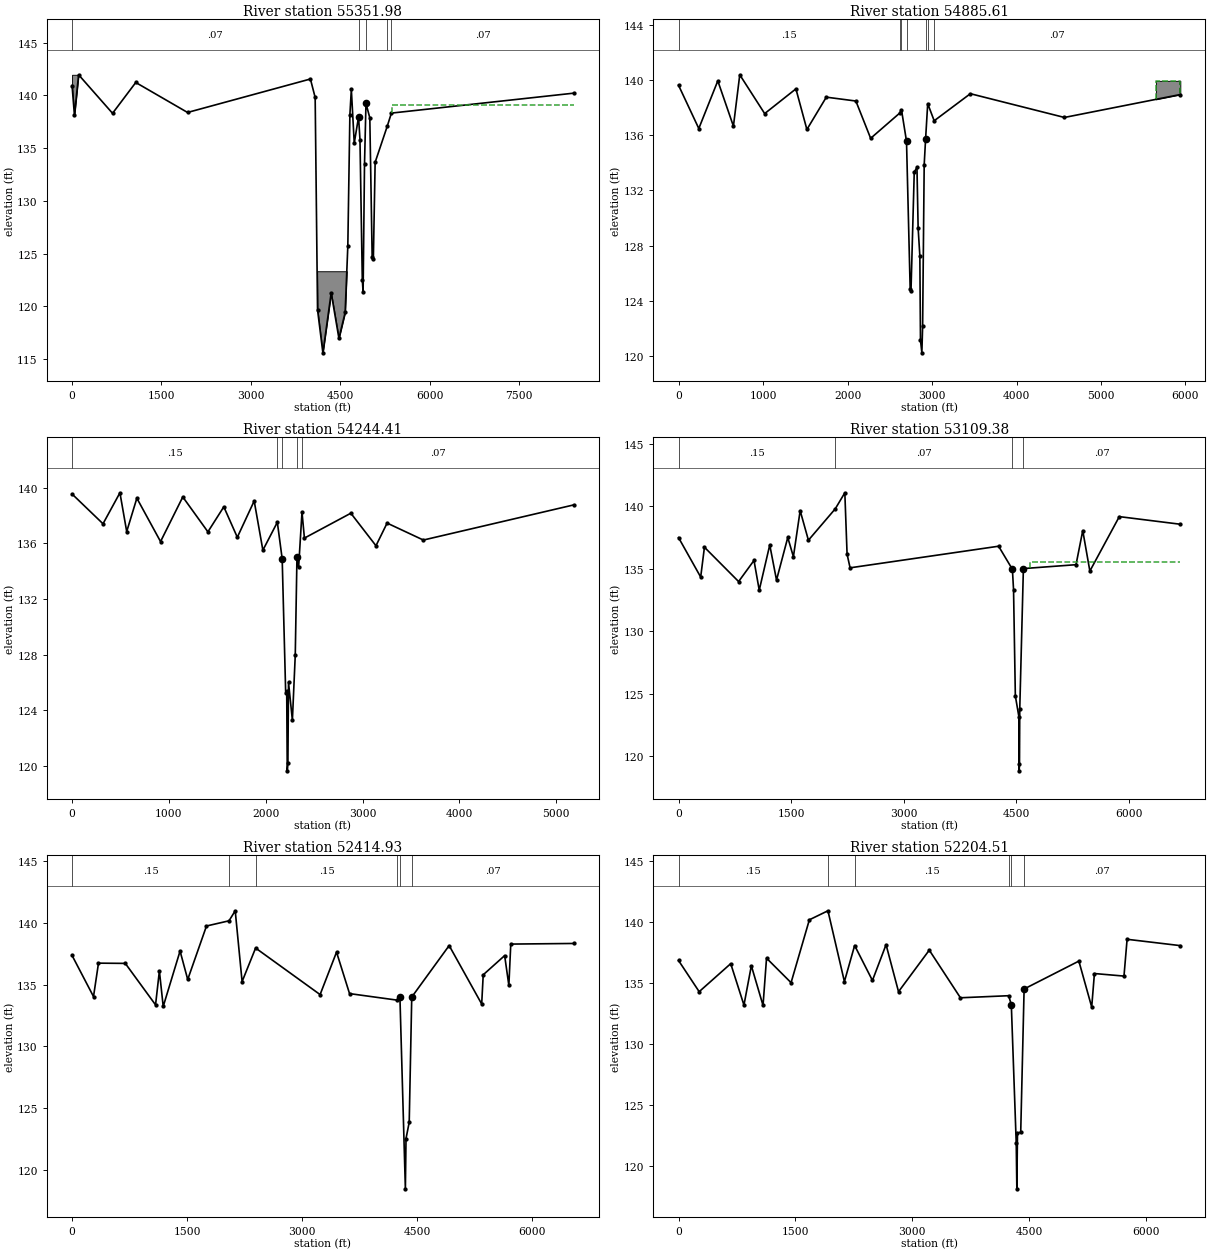
Type RM Length L Ch R = 1 ,55351.98,511.24,466.36,285.35
Node Name=T
XS GIS Cut Line= 6
  3002872.18013213881822.7151988 3003043.8599068 13877189.449859
 3002923.769923913876927.7600937 3002891.779830413875823.1930771
 3002588.539295113874887.7093838 3001701.582735713873806.3509822
#Sta/Elev= 30
       0  140.93   39.95  138.11  109.86  141.95  679.13   138.3 1068.63  141.22
 1937.51  138.38  3998.8  141.55 4078.51   139.8 4118.37  119.69 4208.04  115.61
 4347.54  121.29 4477.07  116.98 4581.69  119.44 4626.53  125.73 4660.95  138.14
  4685.4  140.57  4734.3  135.47 4806.58  137.96 4830.27  135.81 4869.48  122.55
 4882.83  121.34 4906.33  133.46 4931.03  139.24 4995.36  137.87 5034.95  124.65
  5054.8  124.51 5084.78  133.66 5287.12  137.06 5357.55  138.32 8418.84  140.21
#Mann= 5 ,-1 , 0
       0     .07       0 4806.58     .06       0 4931.03     .07       0
 5287.12     .12       0 5357.55     .07       0
#XS Ineff= 4 ,-1
       0  3998.8   139.5  3998.8 4806.58   136.5 4931.03 5369.61   136.5
 5369.61 8418.84  139.06
Permanent Ineff=
       F       T       T       F
#Block Obstruct= 2 ,-1
       0  109.86  141.95  3998.8  4685.4  123.34
Bank Sta=4806.58,4931.03
XS Rating Curve= 0 ,0
Exp/Cntr=0.3,0.1

Type RM Length L Ch R = 1 ,54885.61,517.79,641.2,590.67
XS GIS Cut Line= 6
 3004263.646181113879288.7232195 3003280.035287413876786.6324232
 3003115.863699813876578.9422218 3003051.769667913875733.0154359
 3002852.277284713874886.4984282 3002053.903553413873903.0929147
#Sta/Elev= 30
       0  139.61  239.86  136.48  464.74  139.93  649.63  136.65  724.59  140.37
 1019.42  137.56 1389.21  139.35 1519.14  136.41 1749.01  138.75 2098.81  138.47
 2273.72  135.77 2620.23  137.61 2638.51  137.84 2698.11  135.56 2741.43  124.88
 2751.05  124.69 2789.72  133.33 2821.81  133.67 2835.68  129.28 2856.08  127.25
 2863.29  121.17 2879.84  120.24 2888.85  122.17 2907.39  133.86 2924.17  135.74
 2949.07  138.28 3025.63  137.04 3453.99     139 4567.13  137.28 5938.81  138.94
#Mann= 7 ,-1 , 0
       0     .15       0 2620.23     .07       0 2638.51     .07       0
 2698.11     .06       0 2924.17     .07       0 2949.07     .12       0
 3025.63     .07       0
#XS Ineff= 3 ,-1
       0 2638.51  137.84 2949.07 5649.56  137.84 5649.56 5938.81  139.93
Permanent Ineff=
       F       F       F
#Block Obstruct= 1 ,-1
 5649.56 5938.81  139.93
Bank Sta=2698.11,2924.17
XS Rating Curve= 0 ,0
Exp/Cntr=0.3,0.1

Type RM Length L Ch R = 1 ,54244.41,1116.14,1135.03,1040.21
XS GIS Cut Line= 6
3004708.01701152 13878760.4506543004215.6925368613877554.1938802
3003793.9099158613876860.92000433003736.0901496113876755.7899652
3003678.2700552813876645.40993663002970.9448624913873913.6626526
#Sta/Elev= 30
       0  139.55  319.47  137.41  494.19  139.64  564.07  136.85   668.9  139.25
   913.5  136.13 1143.12  139.34 1402.43  136.83 1566.72  138.63 1706.12  136.44
 1880.36  139.05 1969.98  135.51 2119.35  137.52 2169.34  134.89 2205.38  125.26
 2216.04  125.37 2221.69  119.64 2228.45  120.19 2234.64  126.01 2274.66  123.28
 2304.29  127.95 2321.92  134.99    2339  134.28 2373.92  138.25 2398.88  136.38
 2878.13  138.17 3137.72  135.83 3252.54  137.46 3626.95  136.24 5180.78  138.77
#Mann= 5 ,-1 , 0
       0     .15       0 2119.35     .07       0 2169.34     .04       0
 2321.92     .07       0 2373.92     .07       0
#XS Ineff= 2 ,-1
       0 2054.61   136.5 2373.92 5180.78   136.5
Permanent Ineff=
       F       F
Bank Sta=2169.34,2321.92
XS Rating Curve= 0 ,0
Exp/Cntr=0.3,0.1

Type RM Length L Ch R = 1 ,53109.38,692.93,694.45,614.21
XS GIS Cut Line= 6
3007671.2404157813878654.11523683006284.6352493613876819.6064386
3004375.6200385213875929.70008193003490.6296825313875317.7810302
3003308.1018323613874893.70674713003091.7029869413874188.0575678
#Sta/Elev= 30
       0  137.49  294.95  134.33  344.94  136.72  799.86  133.97 1004.82  135.66
 1074.81  133.28 1214.78   136.9 1304.77  134.09 1454.74   137.5 1529.73  135.96
 1619.71  139.65 1729.69  137.28 2087.78   139.8 2214.61  141.08  2244.6  136.16
  2284.6  135.07 4262.44   136.8 4446.19  134.95 4461.48  133.31 4485.49  124.81
 4532.81  123.14 4536.09  118.81 4540.67  119.35 4544.28  123.77 4592.53  135.01
 5293.49  135.32 5383.16  138.05 5477.81  134.81 5870.01  139.17 6682.57  138.56
#Mann= 4 ,-1 , 0
       0     .15       0 2087.78     .07       0 4446.19     .04       0
 4592.53     .07       0
#XS Ineff= 2 ,-1
       0 4277.33   135.5 4680.74 6682.57   135.5
Permanent Ineff=
       F       F
Bank Sta=4446.19,4592.53
XS Rating Curve= 0 ,0
Exp/Cntr=0.3,0.1

Type RM Length L Ch R = 1 ,52414.93,209.7,210.42,209.5
XS GIS Cut Line= 6
 3007660.621998713878571.82078193006381.4293471113876839.5338922
3005074.4414755313875536.25336233004412.9601869413875374.9167427
3003363.7641226113874816.9949583 3003148.154645713874173.9444071
#Sta/Elev= 30
       0  137.35  279.79  134.03  344.74  136.73  694.49  136.71 1089.19  133.36
 1139.16   136.1 1189.12  133.23 1408.96  137.71 1508.88  135.41  1753.7  139.73
 2047.58  140.15 2128.42  140.96 2218.26  135.24 2394.51  137.95 3235.91  134.19
 3450.42  137.62 3620.03  134.27 4243.58  133.74 4277.47  133.96  4348.5   118.5
 4356.82  122.56 4398.57  123.88 4431.54  133.99  4919.7  138.15 5344.11  133.43
 5364.08  135.79 5643.69  137.34 5698.62  134.93 5723.58  138.27  6546.6  138.32
#Mann= 6 ,-1 , 0
       0     .15       0 2047.58     .07       0 2394.51     .15       0
 4243.58     .07       0 4277.47     .04       0 4431.54     .07       0
#XS Ineff= 3 ,-1
       0 3439.34   135.5 3439.34 4016.67  133.27 4888.18  6546.6  134.57
Permanent Ineff=
       F       F       F
Bank Sta=4277.47,4431.54
XS Rating Curve= 0 ,0
Exp/Cntr=0.3,0.1

Type RM Length L Ch R = 1 ,52204.51,106.8,99.55,103.51
Node Name=S
XS GIS Cut Line= 6
3007661.9490957713878435.10616043006414.9893193513876810.1687934
3005110.8807071113875329.76427393004449.3994185313875168.4276544
3003423.8581625213874723.51483033003181.0850260313874155.1271875
#Sta/Elev= 30
       0  136.84  264.77  134.28  669.43  136.58  839.28  133.18   934.2  136.41
 1084.08  133.15 1129.04  137.03 1443.77  135.02 1678.57  140.18 1916.89  140.92
 2128.17  135.11 2259.39  138.07 2487.79   135.2 2662.61  138.14 2822.44  134.28
 3217.03  137.69 3616.61  133.78  4235.9  133.95 4269.68  133.21 4332.57  121.87
 4340.56   118.1 4348.73  122.67 4390.26  122.75 4433.68   134.5 5136.24  136.79
 5300.93  133.02 5335.86  135.77 5715.14  135.56 5755.07  138.58 6438.02  138.06
#Mann= 6 ,-1 , 0
       0     .15       0 1916.89     .07       0 2259.39     .15       0
  4235.9     .07       0 4269.68     .04       0 4433.68     .07       0
#XS Ineff= 3 ,-1
       0 3082.17  135.25 3082.17 4157.76  133.27 4634.74 6438.02  134.57
Permanent Ineff=
       F       F       F
Bank Sta=4269.68,4433.68
XS Rating Curve= 0 ,0
Exp/Cntr=0.5,0.3