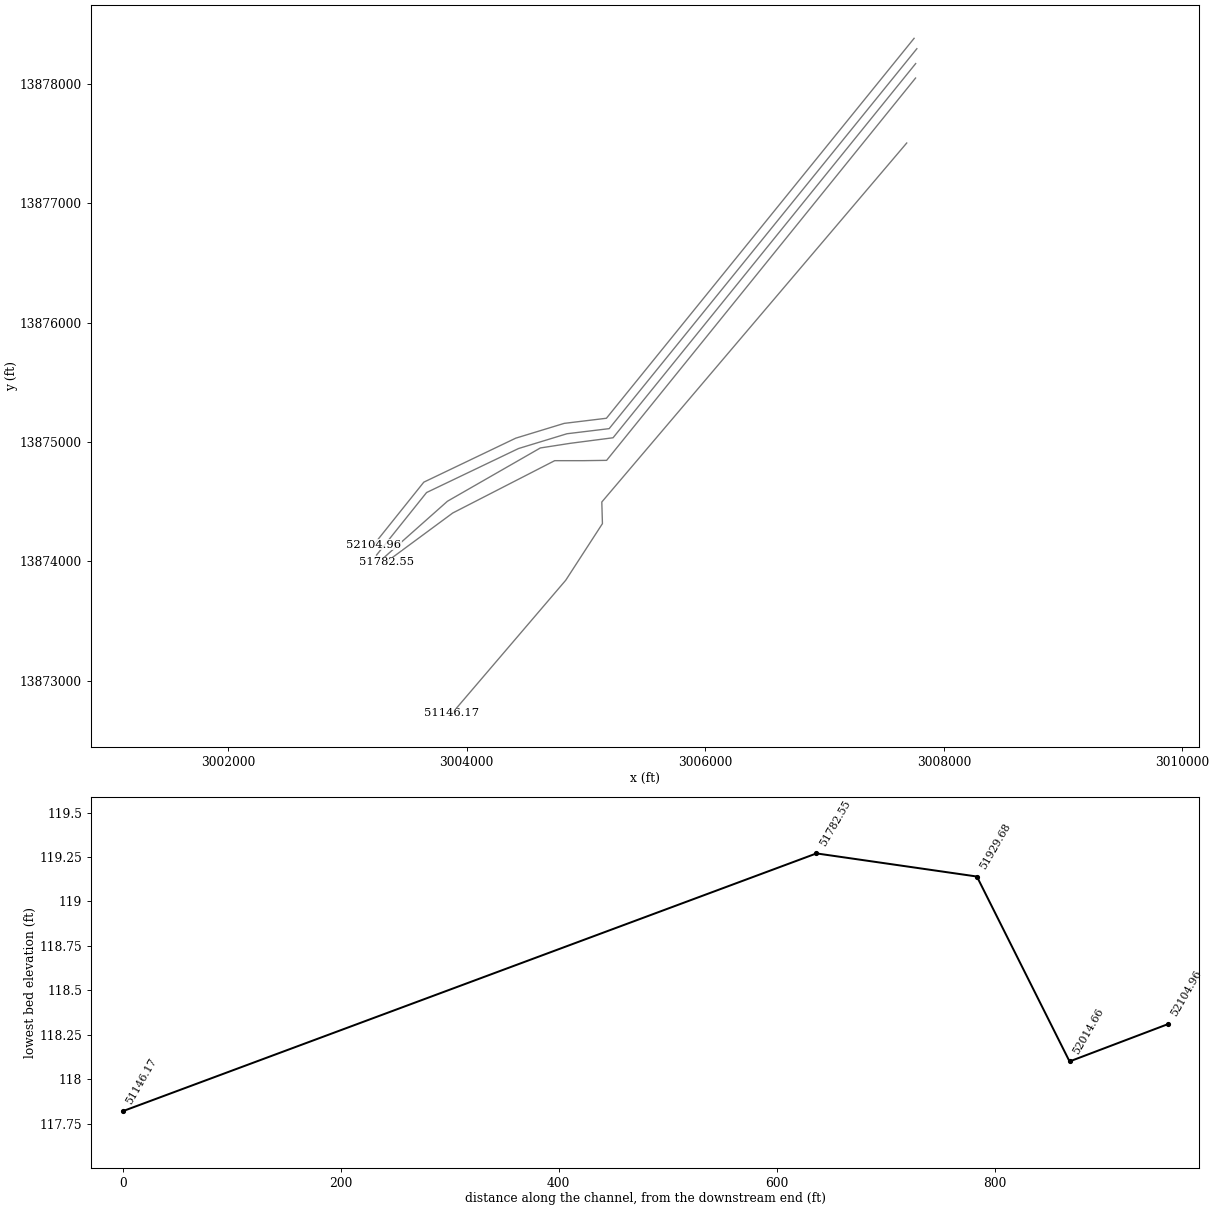
HEC-RAS study U102-00-00.prj: U102-00-00 (Update)

--- U102-00-00.g01 (geometry) --- (continued)

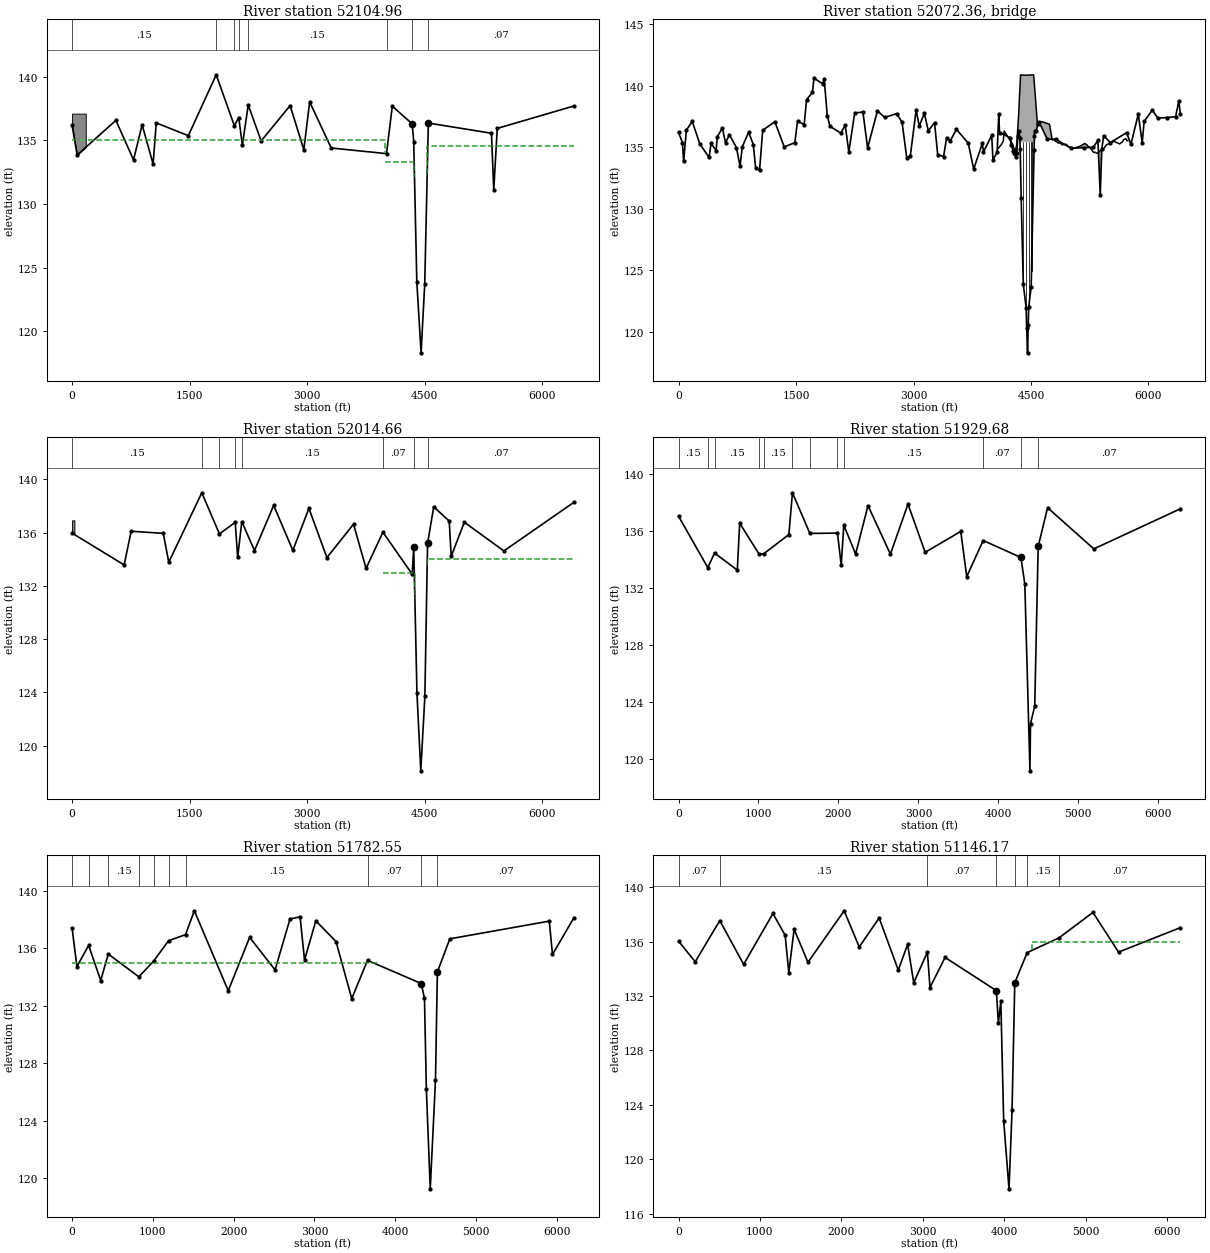
Type RM Length L Ch R = 1 ,52104.96,89.87,90.3,90.39
BEGIN DESCRIPTION:
Upstream Section (WEST LITTLE YORK)
END DESCRIPTION:
XS GIS Cut Line= 6
3007750.1913733613878383.56295633005170.8471226113875198.6080402
3004816.9777516113875155.76232533004410.9398497813875031.8347517
3003640.0316146913874662.88962343003220.92090435 13874139.140999
#Sta/Elev= 30
       0  136.19   64.97  133.84  559.78  136.56   784.7  133.46  894.65  136.21
  1034.6  133.13 1074.58  136.36 1484.42  135.36 1840.29  140.14 2071.92  136.14
  2128.3  136.78 2174.16  134.61 2249.18  137.77 2414.07  134.94 2783.93  137.72
 2958.87  134.26 3033.84  138.01 3308.73  134.39 4014.69  133.95 4088.44  137.67
 4342.53  136.29 4362.17  134.89 4401.71  123.88 4456.12  118.31 4502.62  123.69
 4548.89  136.35 5354.34  135.55 5384.08  131.11 5428.69  135.93 6406.79  137.69
#Mann= 8 ,-1 , 0
       0     .15       0 1840.29     .07       0 2071.92     .15       0
  2128.3     .07       0 2249.18     .15       0 4014.69     .07       0
 4342.53     .04       0 4548.89     .07       0
#XS Ineff= 3 ,-1
       0 3998.48     135 3998.48    4372  133.27 4534.14 6406.79  134.57
Permanent Ineff=
       F       F       F
#Block Obstruct= 2 , 0
       0  174.93  137.09               0
Bank Sta=4342.53,4548.89
XS Rating Curve= 0 ,0
Exp/Cntr=0.5,0.3

Type RM Length L Ch R = 3 ,52072.36,,,
BEGIN DESCRIPTION:
WEST LITTLE YORK
U02_700
END DESCRIPTION:
Node Name=WEST LITTLE YORK
Bridge Culvert--1,0,-1,-1, 0
Deck Dist Width WeirC Skew NumUp NumDn MinLoCord MaxHiCord MaxSubmerge Is_Ogee
20,32,2.6,0, 50, 50, , , 0.98, 0, 0,0,,
 4083.45 4122.71 4146.97 4156.68 4259.05 4298.34 4317.98 4342.53 4352.35 4367.09
    4372 4445.65 4534.14 4553.81 4583.31 4617.72 4642.47  4736.5 4771.15    4786
 4850.34 4855.29 4904.71 4924.45 4939.26 4949.13 4978.74 5052.77 5131.79 5186.15
 5220.75 5230.63 5245.46 5299.82 5319.65 5334.52  5359.3 5384.08 5413.82 5418.78
 5463.39 5552.61 5562.52 5567.48 5631.91 5666.61 5681.48 5711.22 5726.09    5736
  134.92  135.21  135.51136.3141135.3119134.6418135.2086137.6486138.9985 140.859
140.8547140.8358140.8717139.2603136.7644137.0089137.0612136.8594  135.59  135.61
  135.33   135.4  135.17  135.25  135.16  135.24  135.04  134.91  135.09   135.3
  135.15  135.03  135.02  134.57  134.59  134.51  134.53  134.73  134.84   134.8
  135.19  135.44  135.55  135.45  135.26  135.43   135.6  135.69  135.53  135.52
       0       0       0       0       0       0       0       0       0       0
135.3959135.4019  135.38       0       0       0       0       0       0       0
       0       0       0       0       0       0       0       0       0       0
       0       0       0       0       0       0       0       0       0       0
       0       0       0       0       0       0       0       0       0       0
 4083.45 4122.71 4146.97 4156.68  4185.8 4214.92 4259.05 4283.61 4317.98 4342.53
    4372 4376.91 4504.64 4534.14 4553.81 4642.47 4696.91  4736.5 4771.15    4786
 4850.34 4855.29 4904.71 4924.45 4939.26 4949.13 4978.74 5052.77 5131.79 5186.15
 5220.75 5230.63 5245.46 5299.82 5319.65 5334.52  5359.3 5384.08 5413.82 5418.78
 5463.39 5552.61 5562.52 5567.48 5631.91 5666.61 5681.48 5711.22 5726.09    5736
  134.92  135.21  135.51  135.45 134.218134.2014134.9044134.9676134.7903137.0208
140.2379140.4592  140.45140.5419140.3464138.9986138.5333138.0969  135.59  135.61
  135.33   135.4  135.17  135.25  135.16  135.24  135.04  134.91  135.09   135.3
  135.15  135.03  135.02  134.57  134.59  134.51  134.53  134.73  134.84   134.8
  135.19  135.44  135.55  135.45  135.26  135.43   135.6  135.69  135.53  135.52
       0       0       0       0       0       0       0       0       0       0
       0135.9983  135.95 135.976       0       0       0       0       0       0
       0       0       0       0       0       0       0       0       0       0
       0       0       0       0       0       0       0       0       0       0
       0       0       0       0       0       0       0       0       0       0
Pier Skew, UpSta & Num, DnSta & Num=  ,4400.12, 2 ,4408.11, 2 , 0 , 0 , 0 ,,
     1.4     1.4
     115     136
     1.4     1.4
     115     136
Pier Skew, UpSta & Num, DnSta & Num=  ,4434.77, 2 ,4442.25, 2 , 0 , 0 , 0 ,,
     1.4     1.4
     115     136
     1.4     1.4
     115     136
Pier Skew, UpSta & Num, DnSta & Num=  ,4472.26, 2 ,4471.42, 2 , 0 , 0 , 0 ,,
     1.4     1.4
     115     136
     1.4     1.4
     115     136
Pier Skew, UpSta & Num, DnSta & Num=  ,4506.81, 2 ,4505.57, 2 , 0 , 0 , 0 ,,
     1.4     1.4
     115     136
     1.4     1.4
     115     136
Abutment Skew #Up #Dn= , 2 , 2
 4366.82 4401.05
   135.2  123.29
 4374.95 4407.77
  135.83  123.38
Abutment Skew #Up #Dn= , 2 , 2
 4505.71 4540.28
  123.49   135.2
 4505.59 4538.78
  123.34  135.82
BR Coef=-1 , 1 , 1 ,0.9, 0 ,,,0.8,-1,1.2,0,
WSPro=,,,, 1 ,,,, 0 ,,,, 0 ,,,,-1 ,-1 ,-1 , 0 , 0 , 0 , 0 , 0
BR U #Sta/Elev= 110
       0  136.19   49.98  135.37   64.97  133.84   99.96  136.38  174.93  137.09
   269.9  135.29  389.85  134.16  414.84   135.3  479.81  134.72  494.81  135.84
  559.78  136.56  599.77  135.36  649.75  136.01  739.71  134.96   784.7  133.46
  814.68  135.04  894.65  136.21  954.63  135.21  984.62   133.3  1034.6  133.13
 1074.58  136.36 1229.52  137.07 1349.48  135.02 1484.42  135.36 1519.41  137.12
 1604.38  136.83 1634.37  138.84 1709.34  139.45 1729.33  140.59 1840.29  140.14
 1859.28  140.55 1899.26  137.53 1934.25  136.69 2071.92  136.14  2128.3  136.78
 2174.16  134.61 2249.18  137.77 2354.09  137.85 2414.07  134.94 2539.02  137.93
 2633.99  137.41 2783.93  137.72  2853.9  137.03 2913.88  134.13 2958.87  134.26
 3033.84  138.01 3073.82  136.71  3138.8  137.74 3188.78  136.33 3268.75  136.98
 3308.73  134.39 3383.71  134.24 3423.69  135.78 3468.68   135.5 3548.65  136.44
 3698.59  135.33 3768.56  133.22 3878.52   135.3 3893.52  134.62 3998.48  135.95
 4014.69  133.95 4068.45  134.61 4088.44  137.67 4098.44  136.18  4234.5  135.76
 4249.23  135.14 4273.78  134.68 4278.69  134.51 4298.34  134.44 4308.16  134.21
 4317.98  134.49 4332.71  135.94 4342.53  136.29 4357.26  135.78 4362.17  134.89
 4374.91  130.88 4401.71  123.88 4438.13  121.97 4444.82  120.34 4456.12  118.31
 4464.66  120.55 4471.03  122.02 4502.62  123.69 4539.06  134.73 4543.97  135.94
 4548.89  136.35 4568.56  136.33 4588.22   136.9 4602.97  137.05 4706.81  135.65
 4815.69  135.65 5013.29   134.9 5171.33  134.96 5294.88  134.98 5354.34  135.55
 5384.08  131.11 5403.91  134.86 5428.69  135.93 5512.95  135.37 5721.13  136.17
 5775.75  135.22 5870.16  137.68 5919.85  135.34 5944.69  137.09 6049.04     138
  6118.6  137.36 6232.88   137.4 6347.16  137.47 6386.91  138.75 6406.79  137.69
BR U #Mann= 10
       0     .15 1840.29     .07 2071.92     .15  2128.3     .07 2249.18     .15
 4014.69     .07 4342.53     .04 4362.17    .015 4539.06     .04 4548.89     .07
BR D #Sta/Elev= 138
       0  135.96   29.99  136.92   94.96  134.17  124.95  136.22   264.9  136.54
  344.87   135.6  389.85  133.88  444.83  135.22  569.78   135.5  664.74  133.57
  704.73  135.43  754.71   136.1  874.66  134.78  904.65  133.61  934.64  136.26
  1024.6  135.26 1164.55  135.94 1234.52  133.77  1284.5  133.96 1409.45  136.47
 1449.44  135.14 1484.42  138.22 1514.41  138.67 1594.38  137.42 1624.37  139.37
 1656.46  138.99 1694.34  138.78 1724.33  137.02 1834.29  136.52 1869.27  134.83
 1881.43   135.9 1939.25  137.16 1969.24  135.53 2029.21  137.47 2082.95  136.77
 2114.18  134.13 2167.42  136.82 2184.15  137.52 2279.12  137.05  2329.1  134.65
 2389.08  136.46 2574.01  138.04 2698.96  136.63 2758.94  137.03 2818.92  134.66
 2843.91  134.74 2903.89  137.37 2943.87  136.73 3023.84  137.82 3053.83  136.97
 3168.79  136.65 3223.77  134.31 3253.76  134.12 3303.74  135.79 3383.71  134.15
 3453.68  136.32 3473.67  135.67 3593.63  136.63 3753.57  133.31 3818.54  133.55
 3843.54  134.74 3968.67  136.03 4003.48  134.51 4088.44   135.9 4142.12  134.25
 4229.59  133.75 4239.41   134.2 4254.14  134.56 4268.87  134.81 4293.43  134.91
 4303.25  134.72 4317.98  134.65 4322.89  134.49 4332.71  133.79 4342.53  132.87
 4347.44   133.3 4357.26  134.67 4362.17   134.9 4367.09   134.8    4372  133.96
 4403.58  123.92 4437.62  121.88 4447.39  119.49 4452.44   118.1  4460.9  119.13
 4466.68  121.65 4504.33  123.69 4532.25  133.05 4539.06  135.19 4543.97  136.45
 4548.89  137.02 4553.81  137.11 4573.47  136.97 4588.22     137 4598.06  136.91
 4602.97  137.05 4617.72  137.94 4632.57  137.92 4642.47  137.81 4652.37  137.91
 4667.21  137.76 4677.11  137.42 4691.96  137.48 4701.86  137.42 4716.71  137.07
 4731.56  137.16 4741.45  136.99 4751.35  137.14  4776.1  136.84 4781.05  136.92
 4790.95  136.72 4800.84  137.01 4805.79  136.86 4815.69  136.86 4825.59  136.47
 4830.54  135.66 4835.49   134.5 4840.44  134.21 4850.34  136.11 5008.36  136.78
 5121.91  136.17 5215.81  136.74 5319.65  136.52 5379.13  135.56 5512.95  134.62
 5557.56  135.25 5701.31  135.85    5736  135.41 5860.22   137.6 5934.75  136.64
 5949.66  135.26 5984.44  138.18 6103.69  137.22 6168.29  138.41 6247.79  138.22
 6257.72  137.11 6376.97  137.18 6406.79  138.27
BR D #Mann= 10
       0     .15 1656.46     .07 1881.43     .15 2082.95     .07 2167.42     .15
 3968.67     .07 4362.17     .04    4372    .015 4539.06     .04 4553.81     .07
BC Design=,, 0 ,, 0 ,,,,,,
BC Use User HTab Curves=0
BC User HTab FreeFlow(D)= 0

Type RM Length L Ch R = 1 ,52014.66,86.1,84.99,73.86
BEGIN DESCRIPTION:
Downstream Section (WEST LITTLE YORK)
END DESCRIPTION:
XS GIS Cut Line= 6
3007773.3825999513878296.5995476 3005194.038349213875111.6446314
 3004840.168978213875068.79891663004434.1310763713874944.8713429
3003663.2228412813874575.92621473003244.1121309413874052.1775903
#Sta/Elev= 30
       0  135.96  664.74  133.57  754.71   136.1 1164.55  135.94 1234.52  133.77
 1656.46  138.99 1881.43   135.9 2082.95  136.77 2114.18  134.13 2167.42  136.82
  2329.1  134.65 2574.01  138.04 2818.92  134.66 3023.84  137.82 3253.76  134.12
 3593.63  136.63 3753.57  133.31 3968.67  136.03 4342.53  132.87 4362.17   134.9
 4403.58  123.92 4452.44   118.1 4504.33  123.69 4539.06  135.19 4617.72  137.94
 4815.69  136.86 4840.44  134.21 5008.36  136.78 5512.95  134.62 6406.79  138.27
#Mann= 8 ,-1 , 0
       0     .15       0 1656.46     .07       0 1881.43     .15       0
 2082.95     .07       0 2167.42     .15       0 3968.67     .07       0
 4362.17     .04       0 4539.06     .07       0
#XS Ineff= 3 ,-1
       0 3968.67     135 3968.67 4376.91     133 4534.14 6406.79     134
Permanent Ineff=
       F       F       F
#Block Obstruct= 2 , 0
       0   29.99  136.92               0
Bank Sta=4362.17,4539.06
XS Rating Curve= 0 ,0
Exp/Cntr=0.5,0.3

Type RM Length L Ch R = 1 ,51929.68,153.1,147.12,131.66
XS GIS Cut Line= 6
3007763.4944963613878172.0692849 3005226.624898213875035.1503619
3004869.3759407713874988.81219993004617.0939650213874949.7020419
 3003838.493488113874503.16717383003294.03493136 13874019.960135
#Sta/Elev= 30
       0  137.06  366.07  133.44  450.48  134.47  734.88  133.27  764.88  136.57
  1005.8  134.41 1064.18  134.41 1379.78  135.77 1424.56  138.71 1642.69  135.85
 1987.52  135.87 2034.67  133.62  2066.7  136.43 2214.64   134.4 2369.62  137.81
 2649.57  134.39 2869.54  137.91  3084.5  134.52 3529.43  135.99 3604.42  132.81
 3809.91  135.35 4281.09  134.16 4330.43  132.31 4394.79  119.14 4401.77  122.46
 4454.69   123.7 4497.69  134.93 4615.51  137.66 5193.41  134.76 6275.41  137.58
#Mann= 12 ,-1 , 0
       0     .15       0  366.07     .07       0  450.48     .15       0
  1005.8     .07       0 1064.18     .15       0 1424.56     .07       0
 1642.69     .15       0 1987.52     .07       0  2066.7     .15       0
 3809.91     .07       0 4281.09     .04       0 4497.69     .07       0
#XS Ineff= 3 ,-1
       0 3809.51     135 3809.51 4130.76     133 4564.71 6275.41     134
Permanent Ineff=
       F       F       F
Bank Sta=4281.09,4497.69
XS Rating Curve= 0 ,0
Exp/Cntr=0.3,0.1

Type RM Length L Ch R = 1 ,51782.55,440.94,636.38,677.58
XS GIS Cut Line= 6
 3007762.501716213878050.65154873005172.72671203 13874845.753759
 3004976.796657713874843.14319993004737.4254172713874843.1431999
3003882.7306043713874404.48397233003324.6608543513873992.7374204
#Sta/Elev= 30
       0  137.41   59.93  134.73  204.79   136.2  354.61  133.76  447.79   135.6
  826.46  134.02 1008.13   135.1 1194.68  136.53 1404.02  136.95 1513.34  138.61
 1932.88  133.05 2197.59  136.76 2512.25   134.5 2697.05  138.04 2821.91  138.19
 2876.85  135.19  3016.7  137.91 3266.43  136.47 3461.22   132.5  3656.4  135.16
 4321.44  133.55 4361.34  132.51 4384.59  126.19 4432.68  119.27 4497.67  126.84
 4520.92  134.35 4675.29  136.66 5905.67  137.89 5945.58  135.57 6210.02  138.12
#Mann= 10 ,-1 , 0
       0     .15       0  204.79     .07       0  447.79     .15       0
  826.46     .07       0 1008.13     .15       0 1194.68     .07       0
 1404.02     .15       0  3656.4     .07       0 4321.44     .04       0
 4520.92     .07       0
#XS Ineff= 3 ,-1
       0 3775.88     135 3775.88 4005.63     133 4665.04 6210.02   136.5
Permanent Ineff=
       F       F       F
Bank Sta=4321.44,4520.92
XS Rating Curve= 0 ,0
Exp/Cntr=0.4,0.2

Type RM Length L Ch R = 1 ,51146.17,152.52,147.28,150.43
BEGIN DESCRIPTION:
Upstream Section (16" PIPELINE)
END DESCRIPTION:
XS GIS Cut Line= 6
3007688.4034391913877506.08866143005132.3324358613874496.6225675
3005135.3501463513874391.86030993005137.5551944413874315.3115784
3004830.1293001213873840.99002053003876.5068635213872724.6907439
#Sta/Elev= 30
       0  136.03  204.92  134.51  506.68  137.54  799.69  134.32 1159.55  138.06
  1309.5  136.46 1354.48  133.71 1419.45   136.9 1589.39  134.47 2034.22  138.26
 2219.15   135.6 2464.05  137.73 2698.96   133.9 2813.92  135.79 2888.89  132.97
 3056.41  135.22 3088.81  132.62 3273.74  134.83  3903.5  132.39 3928.49  130.01
 3958.47  131.61  3993.4  122.84  4059.1  117.82 4096.37  123.61 4129.87  132.97
 4282.51  135.19  4671.1  136.26 5089.61  138.14 5404.21  135.22 6163.25  137.02
#Mann= 7 ,-1 , 0
       0     .07       0  506.68     .15       0 3056.41     .07       0
  3903.5     .04       0 4129.87     .07       0 4282.51     .15       0
  4671.1     .07       0
#XS Ineff= 2 ,-1
       0 3273.74     134 4338.12 6163.25     136
Permanent Ineff=
       F       F
Bank Sta=3903.5,4129.87
XS Rating Curve= 0 ,0
Exp/Cntr=0.4,0.2