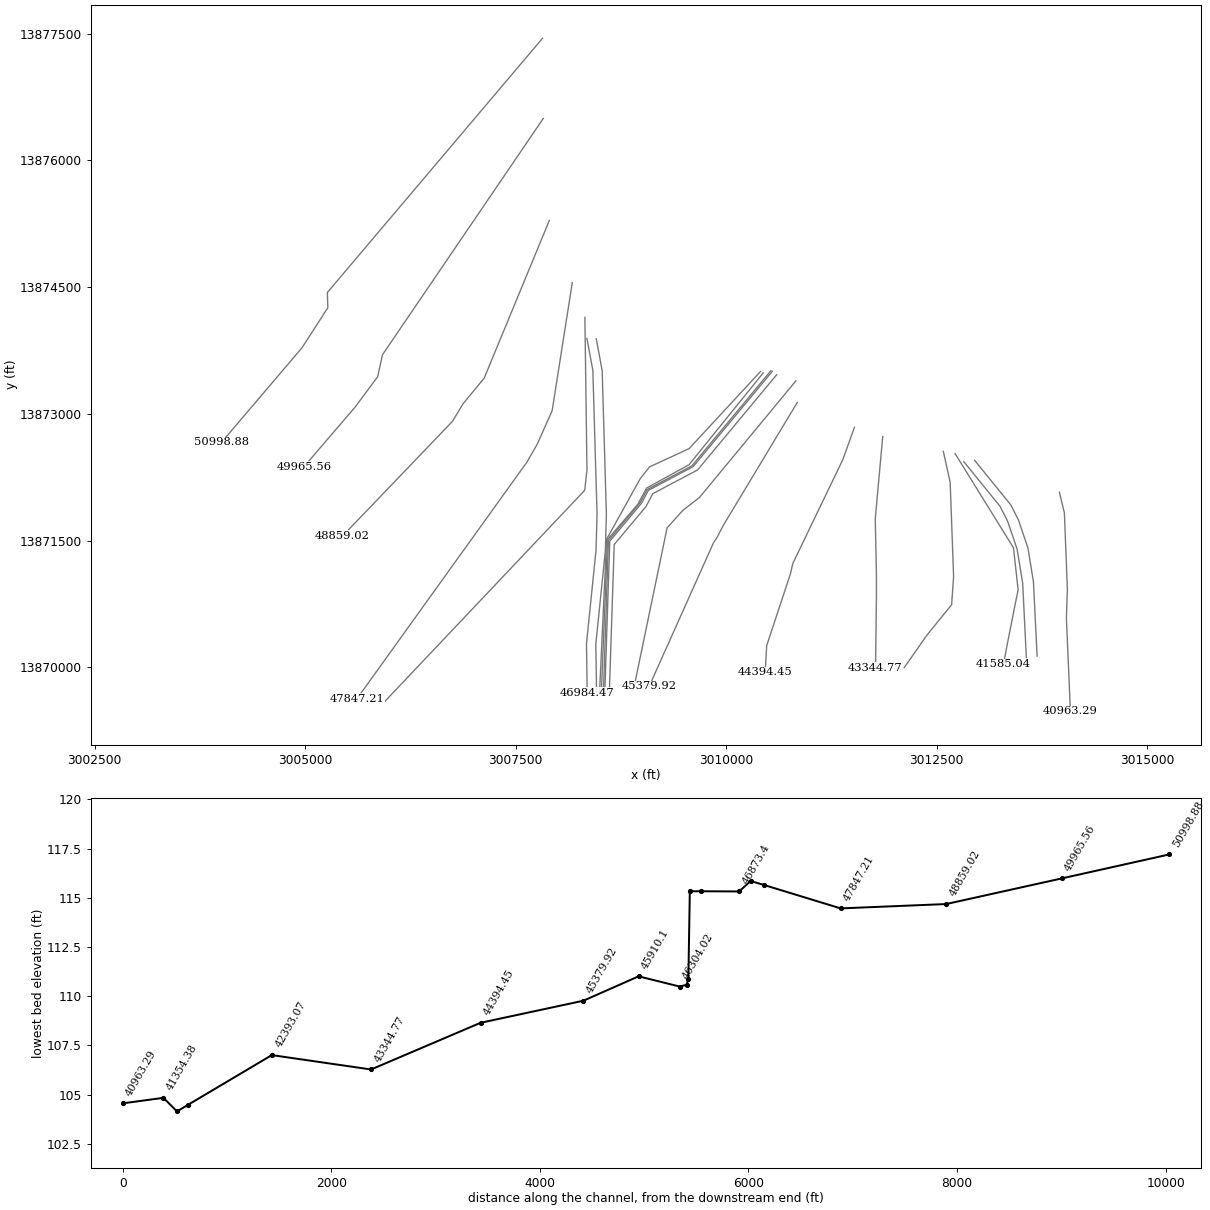
HEC-RAS study U102-00-00.prj: U102-00-00 (Update)

--- U102-00-00.g01 (geometry) --- (continued)

Type RM Length L Ch R = 3 ,51047.25,,,
BEGIN DESCRIPTION:
16" PIPELINE
END DESCRIPTION:
Node Name=16" PIPELINE
Bridge Culvert--1,0,-1,-1, 0
Deck Dist Width WeirC Skew NumUp NumDn MinLoCord MaxHiCord MaxSubmerge Is_Ogee
99,1.33,2.6,0, 25, 25, , , 0.98, 0, 0,0,,
 3938.49 3958.47 3963.46 3968.45 3973.44 3978.43 3988.41 3998.39 4008.37 4023.34
 4033.33 4038.32 4053.29 4062.86 4072.43 4082.01 4086.79 4096.37 4105.94 4110.73
 4115.51  4120.3 4134.83 4139.79  4149.7
  132.18  133.54  134.63  135.69  135.69  135.69   135.7   135.7  135.71  135.71
  135.72  135.72  135.72  135.73  135.73  135.74  135.74  135.74  135.75  135.75
  135.75  135.16  133.27  133.11  133.21
       0  132.21   133.3  134.36  134.36  134.36  134.36  134.37  134.37  134.38
  134.38  134.38  134.39  134.39   134.4   134.4   134.4  134.41  134.41  134.41
  134.42  133.83       0       0       0
 3938.49 3958.47 3963.46 3968.45 3973.44 3978.43 3988.41 3998.39 4008.37 4023.34
 4033.33 4038.32 4053.29 4062.86 4072.43 4082.01 4086.79 4096.37 4105.94 4110.73
 4115.51  4120.3 4134.83 4139.79  4149.7
  132.18  133.54  134.63  135.69  135.69  135.69   135.7   135.7  135.71  135.71
  135.72  135.72  135.72  135.73  135.73  135.74  135.74  135.74  135.75  135.75
  135.75  135.16  133.27  133.11  133.21
       0  132.21   133.3  134.36  134.36  134.36  134.36  134.37  134.37  134.38
  134.38  134.38  134.39  134.39   134.4   134.4   134.4  134.41  134.41  134.41
  134.42  133.83       0       0       0
Pier Skew, UpSta & Num, DnSta & Num=  ,4019.11, 2 ,4019.11, 2 , 0 , 0 , 0 ,,
       1       1
     115     135
       1       1
     115     135
Pier Skew, UpSta & Num, DnSta & Num=  ,4069.11, 2 ,4069.11, 2 , 0 , 0 , 0 ,,
       1       1
     115     135
       1       1
     115     135
BR Coef=-1 , 1 , 1 ,0.9, 0 ,,,0.8,-1,1.2,0,
WSPro=,,,, 1 ,,,, 0 ,,,, 0 ,,,,-1 ,-1 ,-1 , 0 , 0 , 0 , 0 , 0
BC Design=,, 0 ,, 0 ,,,,,,
BC Use User HTab Curves=0
BC User HTab FreeFlow(D)= 0

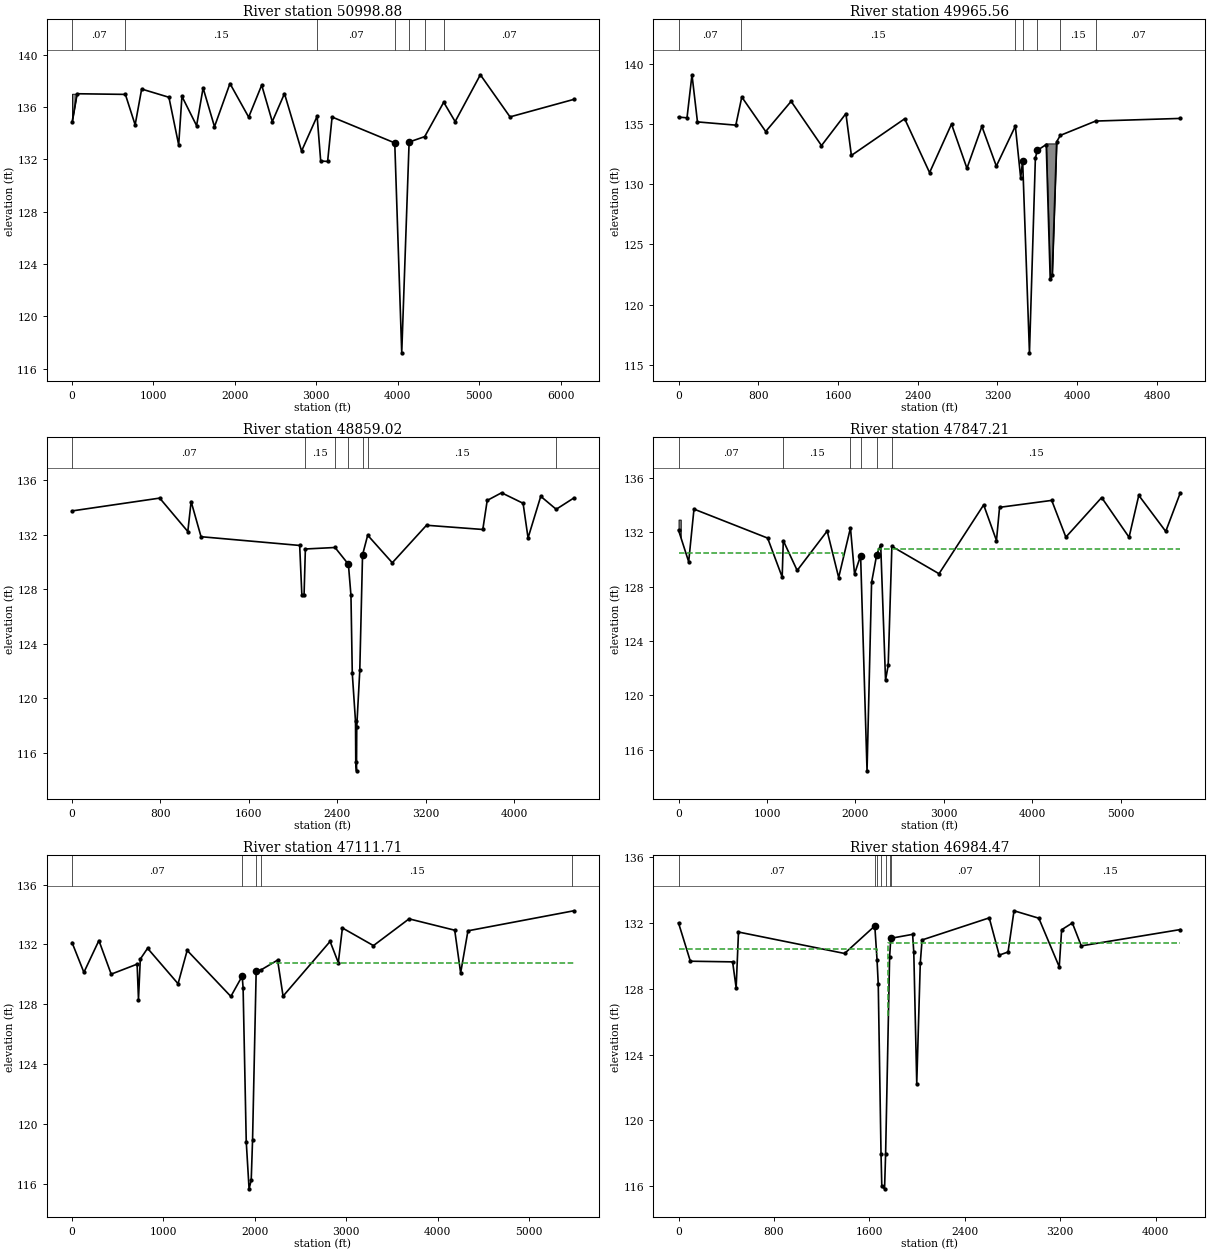
Type RM Length L Ch R = 1 ,50998.88,1037.35,1033.33,1010.29
BEGIN DESCRIPTION:
Downstream Section (16" PIPELINE)
END DESCRIPTION:
XS GIS Cut Line= 6
3007820.9914286113877446.87814993005264.92042528 13874437.412056
3005267.9381357713874332.64979833005270.1431838613874256.1010669
3004962.71728952 13873781.7795093004009.0948529413872665.4802324
#Sta/Elev= 30
       0  134.83   59.98  137.01  654.75  136.96   774.7  134.63  854.67  137.37
 1189.54  136.74  1309.5   133.1 1349.48  136.81 1529.41  134.57 1609.38  137.45
 1749.33  134.49 1939.25  137.79 2169.17  135.22  2329.1  137.67 2459.05  134.88
    2609  137.02 2818.92  132.63 3009.87  135.29 3053.83  131.87 3138.79  131.83
 3193.77  135.23 3963.46  133.25 4049.13   117.2 4139.79  133.32 4331.22  133.73
 4564.82  136.36  4705.1  134.88 5014.71  138.46 5379.24  135.24 6163.25  136.58
#Mann= 7 ,-1 , 0
       0     .07       0  654.75     .15       0 3009.87     .07       0
 3963.46     .04       0 4139.79     .07       0 4331.22     .15       0
 4564.82     .07       0
#XS Ineff= 1 ,-1
       0 3288.74     134
Permanent Ineff=
       F
#Block Obstruct= 2 , 0
       0   59.98  137.01               0
Bank Sta=3963.46,4139.79
XS Rating Curve= 0 ,0
Exp/Cntr=0.4,0.2

Type RM Length L Ch R = 1 ,49965.56,1157.84,1106.54,1089.21
XS GIS Cut Line= 5
3007829.69547944 13876498.0496673005919.0969384513873699.8518514
3005862.3014483613873440.32809223005594.0877459513873080.3294684
3004986.4629769513872374.4302896
#Sta/Elev= 30
       0  135.59   84.96  135.53  134.93  139.11   189.9  135.19   574.7  134.92
  634.67  137.26  874.55  134.39 1129.42   136.9 1434.26  133.22 1679.14  135.88
 1734.11   132.4 2268.84  135.45 2518.71  130.97  2738.6  135.01 2893.52  131.33
 3043.45  134.82 3188.37  131.51 3379.18  134.84 3432.55  130.53 3452.23  131.95
 3520.73  115.98 3580.14  132.19 3599.82  132.82 3688.85  133.31 3728.76  122.15
 3748.71  122.43 3793.61  133.54 3830.72  134.07 4184.65  135.26 5034.29  135.48
#Mann= 7 ,-1 , 0
       0     .07       0  622.69     .15       0 3379.18     .07       0
 3452.23     .04       0 3599.82     .07       0 3830.72     .15       0
 4184.65     .07       0
#XS Ineff= 1 ,-1
       0 3379.18   132.5
Permanent Ineff=
       F
#Block Obstruct= 1 ,-1
 3683.87 3798.59   133.4
Bank Sta=3452.23,3599.82
XS Rating Curve= 0 ,0
Exp/Cntr=0.3,0.1

Type RM Length L Ch R = 1 ,48859.02,1006.35,1011.81,1009.78
Node Name=R
XS GIS Cut Line= 5
3007901.3403492713875290.45201663007127.8300852813873424.0499095
3006874.93557794 13873117.9894983006750.0998696113872911.5601209
 3005444.738635213871554.3584389
#Sta/Elev= 30
       0  133.73  793.17  134.67 1047.59  132.22 1077.52  134.42 1167.31  131.84
 2060.04   131.2 2079.89  127.56 2099.75  127.57 2111.62  130.94 2380.11  131.05
 2501.05  129.82 2524.22  127.54 2536.21  121.82 2565.31  118.31 2567.72  115.33
 2574.38  114.68 2576.64  117.91 2604.13  122.05 2629.06  130.51 2675.59  131.95
 2898.35  129.93 3208.03  132.68 3717.51  132.37 3757.47   134.5 3887.33  135.06
 4082.13  134.29 4127.09  131.75 4241.97   134.8 4381.83  133.85 4541.67  134.68
#Mann= 7 ,-1 , 0
       0     .07       0 2111.62     .15       0 2380.11     .07       0
 2501.05     .04       0 2629.06     .07       0 2675.59     .15       0
 4381.83     .07       0
#XS Ineff= 1 ,-1
       0 2380.11   130.4
Permanent Ineff=
       F
Bank Sta=2501.05,2629.06
XS Rating Curve= 0 ,0
Exp/Cntr=0.3,0.1

Type RM Length L Ch R = 1 ,47847.21,704.43,735.5,752.72
Node Name=Q
XS GIS Cut Line= 5
3008173.7295682713874554.49581143007934.5499285313873037.8699076
3007757.4167526113872641.37332533007634.7598456913872429.0200754
3005613.5768801913869624.7776524
#Sta/Elev= 30
       0  132.15  114.65  129.83  174.47   133.7 1006.96  131.57 1171.47   128.7
 1184.04  131.38 1340.96  129.19 1680.13  132.09 1809.91  128.67 1943.26  132.32
 1989.26  128.93 2057.92  130.28 2130.56  114.46 2181.95  128.31 2239.85  130.34
  2284.8  131.09 2339.75  121.13 2369.72  122.21 2411.37  130.96 2944.17  128.95
  3448.7  134.01 3593.56  131.39 3628.52  133.83 4217.96  134.34 4377.81  131.64
 4782.43  134.55 5092.14  131.63 5202.04  134.71 5506.75  132.06  5671.6   134.9
#Mann= 6 ,-1 , 0
       0     .07       0 1184.04     .15       0 1943.26     .07       0
 2057.92     .04       0 2239.85     .12       0 2411.37     .15       0
#XS Ineff= 2 ,-1
       0 1859.82   130.5 2254.83  5671.6  130.79
Permanent Ineff=
       F       F
#Block Obstruct= 2 , 0
       0   24.92  132.93               0
Bank Sta=2057.92,2239.85
XS Rating Curve= 0 ,0
Exp/Cntr=0.3,0.1

Type RM Length L Ch R = 1 ,47111.71,119.95,127.23,133.79
Node Name=P
XS GIS Cut Line= 5
 3008323.421526113874142.94643763008335.3499799413873272.0298724
3008348.1698361913872336.03994643008321.4599158613872095.6700204
 3005951.2533702  13869600.65795
#Sta/Elev= 30
       0  132.12  129.41  130.13  293.65  132.26  428.03  130.01  711.73  130.68
  726.66  128.31  746.57  131.02   826.2  131.74 1159.79  129.37 1259.37   131.6
 1737.37  128.52 1861.37  129.88 1871.24   129.1 1905.79   118.8 1936.68  115.65
 1960.08  116.22 1974.89  118.94 2014.37   130.2  2068.9   130.3 2248.72  130.95
 2308.65  128.54 2823.12   132.2 2913.02  130.78 2957.98   133.1 3297.62  131.92
 3687.21  133.71 4186.69  132.95 4251.62  130.09 4331.54  132.91 5490.31  134.25
#Mann= 5 ,-1 , 0
       0     .07       0 1861.37     .04       0 2014.37     .07       0
  2068.9     .15       0  5467.7     .07       0
#XS Ineff= 2 ,-1
       0 1434.49   130.4 2162.62 5490.31  130.79
Permanent Ineff=
       F       F
Bank Sta=1861.37,2014.37
XS Rating Curve= 0 ,0
Exp/Cntr=0.5,0.3

Type RM Length L Ch R = 1 ,46984.47,113.66,111.08,112.05
BEGIN DESCRIPTION:
Upstream Section (FRY ROAD)
END DESCRIPTION:
XS GIS Cut Line= 6
3008347.4683940313873893.59851113008417.8855760213873516.0828619
3008467.7083110213871815.32018733008455.5485584413871385.2091709
3008342.3125644513870281.74812333008351.0123501913869701.3303209
#Sta/Elev= 30
       0  131.98   99.08  129.66  453.47  129.62     483  128.04  502.69  131.43
 1391.95  130.13 1645.46   131.8 1664.05  129.76 1674.37  128.26 1697.67  117.95
 1704.17     116 1727.19  115.85 1736.04  117.96 1769.47  129.89 1779.37  131.05
 1962.43  131.29 1972.33  130.19 1997.07  122.24 2026.75  129.55  2041.6  130.95
 2604.94  132.29 2688.46  130.03 2762.69  130.22 2812.58  132.72 3020.29  132.27
  3191.8  129.32 3211.75  131.57 3301.57  131.98 3376.41  130.59 4206.86  131.58
#Mann= 8 ,-1 , 0
       0     .07       0 1645.46    .024       0 1664.05    .015       0
 1697.67     .04       0 1736.04    .015       0 1769.47     .04       0
 1779.37     .07       0 3020.29     .15       0
#XS Ineff= 2 ,-1
       0 1660.82   130.4 1759.58 4206.86  130.79
Permanent Ineff=
       F       F
Bank Sta=1645.46,1779.37
XS Rating Curve= 0 ,0
Exp/Cntr=0.5,0.3

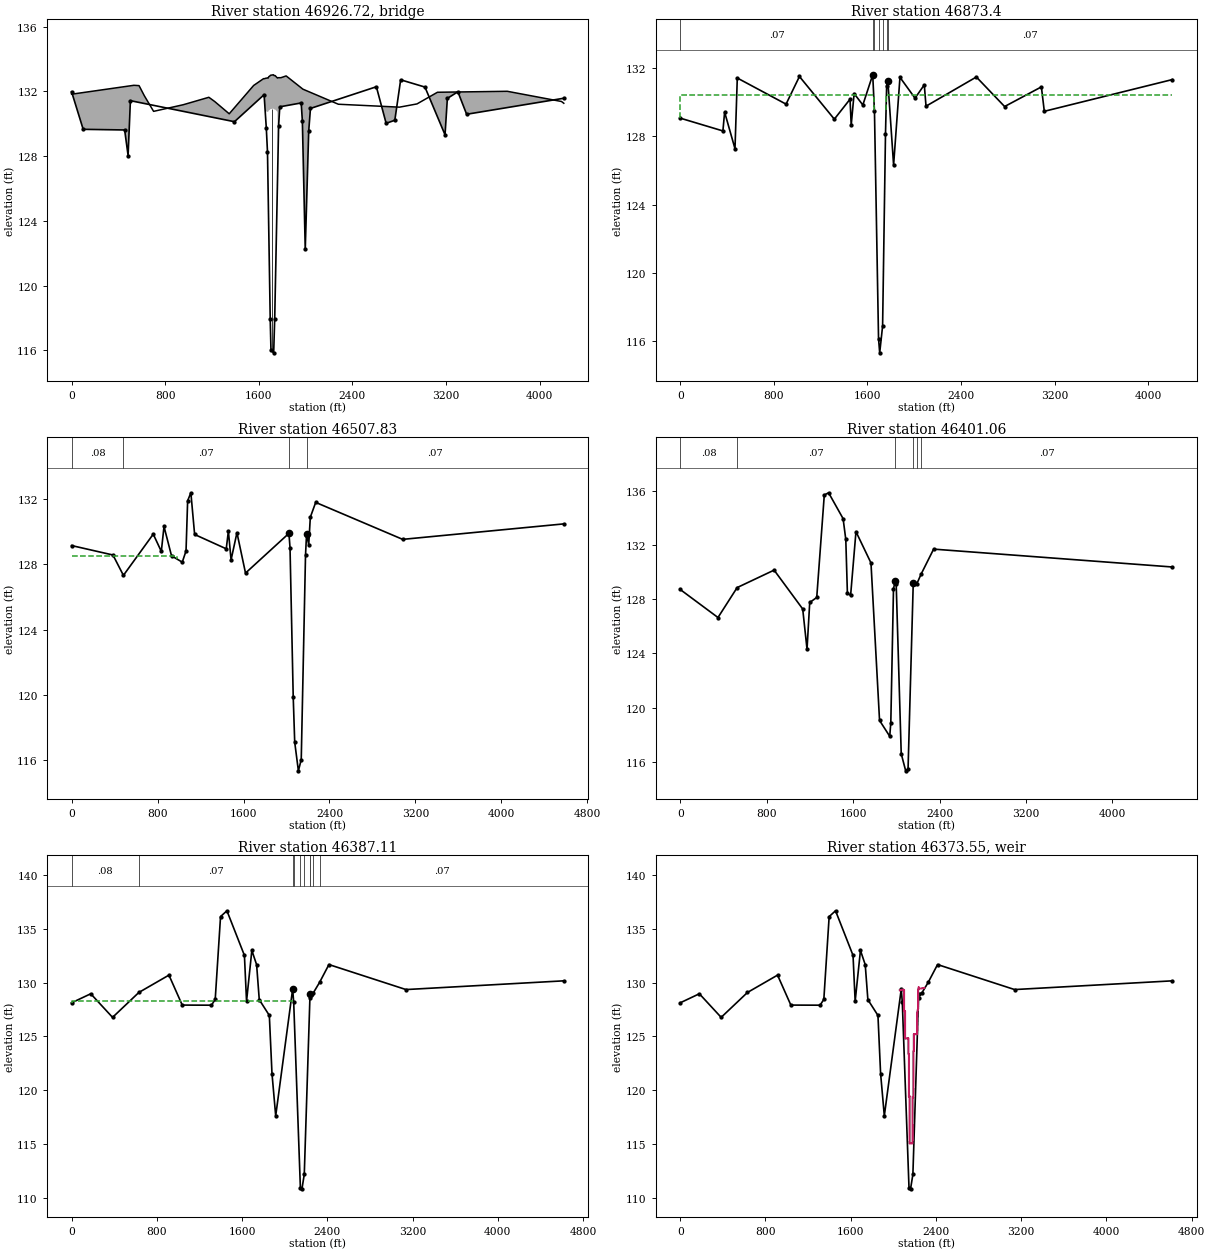
Type RM Length L Ch R = 3 ,46926.72,,,
BEGIN DESCRIPTION:
FRY ROAD
END DESCRIPTION:
Node Name=FRY ROAD
Bridge Culvert--1,0,-1,-1, 0
Deck Dist Width WeirC Skew NumUp NumDn MinLoCord MaxHiCord MaxSubmerge Is_Ogee
20,76,2.6,0, 40, 40, , , 0.98, 0, 0,0,,
       0  532.23  576.63  621.36   700.9  954.43  1173.2 1222.91 1347.21 1555.99
 1640.49 1650.43 1660.37 1665.34 1670.31 1675.28 1680.25 1685.22 1695.17 1700.14
 1724.94 1729.89 1734.84 1739.79 1749.68 1759.58 1764.53 1769.47 1774.42 1779.37
 1789.27 1833.79 1977.28 2279.93  2802.6 2952.29 3126.93 3723.97 4187.11 4206.86
  131.83  132.38  132.36  131.74  130.77  131.18  131.64  131.38  130.62  132.37
  132.79  132.79  132.82  132.82  132.83  132.83  132.83  132.91  132.96     133
  133.03  132.98  132.98  132.98   132.9  132.83  132.85  132.85  132.85  132.85
  132.85  132.96  132.14  131.21  131.03  131.23  131.95  132.01  131.38  131.27
       0       0       0       0       0       0       0       0       0       0
       0       0  130.77  130.77  130.74  130.74  130.74  130.82  130.87  130.91
  130.94  130.89  130.89  130.89  130.81  130.74       0       0       0       0
       0       0       0       0       0       0       0       0       0       0
       0  532.23  576.63  621.36   700.9  954.43  1173.2 1222.91 1347.21 1555.99
 1640.49 1650.43 1660.37 1665.34 1670.31 1675.28 1680.25 1685.22 1695.17 1700.14
 1724.94 1729.89 1734.84 1739.79 1749.68 1759.58 1764.53 1769.47 1774.42 1779.37
 1789.27 1833.79 1977.28 2279.93  2802.6 2952.29 3126.93 3723.97 4187.11 4206.86
  131.83  132.38  132.36  131.74  130.77  131.18  131.64  131.38  130.62  132.37
  132.79  132.79  132.82  132.82  132.83  132.83  132.83  132.91  132.96     133
  133.03  132.98  132.98  132.98   132.9  132.83  132.85  132.85  132.85  132.85
  132.85  132.96  132.14  131.21  131.03  131.23  131.95  132.01  131.38  131.27
       0       0       0       0       0       0       0       0       0       0
       0       0  130.71  130.71  130.68  130.68  130.68  130.76  130.81  130.85
  130.88  130.83  130.83  130.83  130.75  130.68       0       0       0       0
       0       0       0       0       0       0       0       0       0       0
Pier Skew, UpSta & Num, DnSta & Num=  ,1710.48, 2 ,1710.48, 2 , 0 , 0 , 0 ,,
     1.4     1.4
  114.91  131.99
     1.4     1.4
  114.85  131.93
BR Coef=-1 , 1 , 1 ,0.9, 0 ,,,0.8,-1,1.2,0,
WSPro=,,,, 1 ,,,, 0 ,,,, 0 ,,,,-1 ,-1 ,-1 , 0 , 0 , 0 , 0 , 0
BC Design=,, 0 ,, 0 ,,,,,,
BC Use User HTab Curves=0
BC User HTab FreeFlow(D)= 0

Type RM Length L Ch R = 1 ,46873.4 ,393.67,365.57,341.6
BEGIN DESCRIPTION:
Downstream Section (FRY ROAD)
END DESCRIPTION:
XS GIS Cut Line= 6
3008458.4327390313873888.66676243008528.8499210313873511.1511133
3008578.6726560313871810.38843873008566.5129034413871380.2774223
3008453.2769094413870276.81637463008461.9766951913869696.3985722
#Sta/Elev= 30
       0  129.07  364.96  128.32  379.66  129.42  468.24  127.28  487.93  131.42
  904.71  129.89 1019.07  131.51 1317.38  129.01  1451.6  130.18 1461.54  128.66
 1486.39  130.51 1560.96  129.84 1645.46  131.61 1660.37  129.46 1695.17  116.15
 1705.11  115.32 1729.89  116.89 1754.63  128.15 1764.53  130.97 1774.42  131.27
  1823.9  126.32 1878.32  131.46 2006.96  130.24 2086.13  131.02 2101.04  129.77
 2531.25  131.48 2772.67  129.75 3087.01   130.9 3111.96  129.47 4206.86  131.33
#Mann= 7 ,-1 , 0
       0     .07       0 1645.46     .04       0 1660.37    .015       0
 1695.17     .04       0 1729.89    .015       0 1764.53     .04       0
 1774.42     .07       0
#XS Ineff= 2 ,-1
       0 1660.37   130.4 1759.58 4206.86   130.4
Permanent Ineff=
       F       F
Bank Sta=1645.46,1774.42
XS Rating Curve= 0 ,0
Exp/Cntr=0.5,0.3

Type RM Length L Ch R = 1 ,46507.83,111.95,106.77,101.47
XS GIS Cut Line= 6
3010408.6801508713873501.36012243009561.3101264413872589.3199517
 3009090.810083213872372.63009633008981.9799202813872235.3498591
3008581.9475838513871517.93036223008497.4418473513869700.7788128
#Sta/Elev= 30
       0  129.16  384.98  128.58  482.23  127.33  759.96  129.86  834.95   128.8
  859.95  130.33  929.95  128.53 1029.94  128.14 1064.94  128.83 1079.94  131.91
 1109.94   132.4 1144.94  129.84 1439.18  128.96 1459.11  130.05 1484.01  128.28
  1538.8  129.95 1618.49  127.47 2022.65  129.91  2032.6  129.03 2062.43  119.86
 2076.29  117.09 2110.52  115.33 2137.02  116.02  2176.8  128.56 2186.74  129.89
 2206.63  129.21 2221.55   130.9 2271.51  131.81 3080.97  129.54 4580.25  130.49
#Mann= 4 ,-1 , 0
       0     .08       0  482.23     .07       0 2022.65     .04       0
 2186.74     .07       0
#XS Ineff= 2 ,-1
       0  984.19   128.5 2353.27 4580.25  130.16
Permanent Ineff=
       F       F
Bank Sta=2022.65,2186.74
XS Rating Curve= 0 ,0
Exp/Cntr=0.3,0.1

Type RM Length L Ch R = 1 ,46401.06,13.52,13.95,14.74
XS GIS Cut Line= 6
3010441.1699152713873485.14001043009560.6198391213872398.6900836
3009055.94991669 13872122.2198363008952.8700703513871931.0000741
 3008592.072891713871513.05110693008518.8676575313869702.5642423
#Sta/Elev= 30
       0  128.72  349.62  126.65  526.96  128.86  869.05  130.15 1133.77  127.28
 1173.72  124.31  1198.7  127.76 1263.62  128.13 1333.55   135.7 1373.51  135.86
 1507.61  133.95 1532.42  132.42  1547.3  128.47 1577.06  128.28 1626.67  132.99
 1765.57  130.68 1844.94  119.05 1939.19  117.88 1949.11  118.88 1973.92  128.76
  1988.9  129.35 1998.89  129.12 2045.59  116.59  2086.8  115.33 2108.75  115.47
  2156.9  129.22 2188.18  129.11 2229.96  129.86 2345.35   131.7 4555.27  130.38
#Mann= 6 ,-1 , 0
       0     .08       0  526.96     .07       0  1988.9     .04       0
  2156.9     .07       0 2188.18     .15       0 2229.96     .07       0
#XS Ineff= 2 ,-1
       0  1988.9   128.5 2353.32 4555.27  130.38
Permanent Ineff=
       F       F
Bank Sta=1988.9,2156.9
XS Rating Curve= 0 ,0
Exp/Cntr=0.5,0.3

Type RM Length L Ch R = 1 ,46387.11,17.79,17.8,17.79
BEGIN DESCRIPTION:
Upstream Section (WEIR DS FRY RD)
END DESCRIPTION:
XS GIS Cut Line= 6
3010532.9489311913873511.57401273009593.3454954513872384.1822386
3009060.9984630213872103.25990023008981.1583996113871952.1899924
3008603.0036441113871501.49076253008544.0825021113869712.4297081
#Sta/Elev= 30
       0  128.12  179.71  128.96  384.37  126.77  631.03  129.08  913.51  130.69
  1038.3  127.91 1312.86   127.9  1347.8  128.44 1397.72  136.12 1457.62  136.66
 1621.82  132.52 1641.71  128.26 1691.46  132.98 1736.23  131.66  1761.1  128.41
 1855.62  126.95 1880.49  121.56 1915.32  117.63 2074.44   129.4 2084.28  128.15
  2147.1  110.93  2161.7  110.86 2183.48   112.2 2236.37  128.58  2240.4  128.92
 2269.86  129.07 2326.81  130.01  2414.9  131.67 3137.86  129.35 4618.75  130.16
#Mann= 10 ,-1 , 0
       0     .08       0  631.03     .07       0 2074.44     .04       0
 2084.28    .015       0  2147.1     .04       0 2183.48    .015       0
 2236.37     .04       0  2240.4     .07       0 2269.86     .15       0
 2326.81     .07       0
#XS Ineff= 2 ,-1
       0 2074.44  128.32 2438.45 4618.75  130.16
Permanent Ineff=
       F       F
Bank Sta=2074.44,2240.4
XS Rating Curve= 0 ,0
Exp/Cntr=0.5,0.3

Type RM Length L Ch R = 5 ,46373.55,,,
BEGIN DESCRIPTION:
WEIR DS FRY RD
END DESCRIPTION:
Node Name=WEIR DS FRY RD
IW Pilot Flow=0
#Inline Weir SE= 25
  2060.7  129.29  2091.1  129.36  2100.7   129.3  2100.9  127.32  2109.5  127.35
  2109.6   124.8  2140.9  124.84    2141  123.39  2146.1   123.4  2146.3  119.39
  2152.9  119.47    2153  115.07  2180.2  115.07  2180.3  119.38  2187.6  119.35
  2187.7  123.58  2192.3  123.61  2192.4  125.22  2223.6   125.2  2223.8  127.19
  2232.4  127.59  2232.5  129.27  2238.9  129.58  2241.8  129.43 2290.26   129.5
IW Dist,WD,Coef,Skew,MaxSub,Min_El,Is_Ogee,SpillHt,DesHd
13.5,2,2.6,0,0.98,, 0 ,,,0,0,

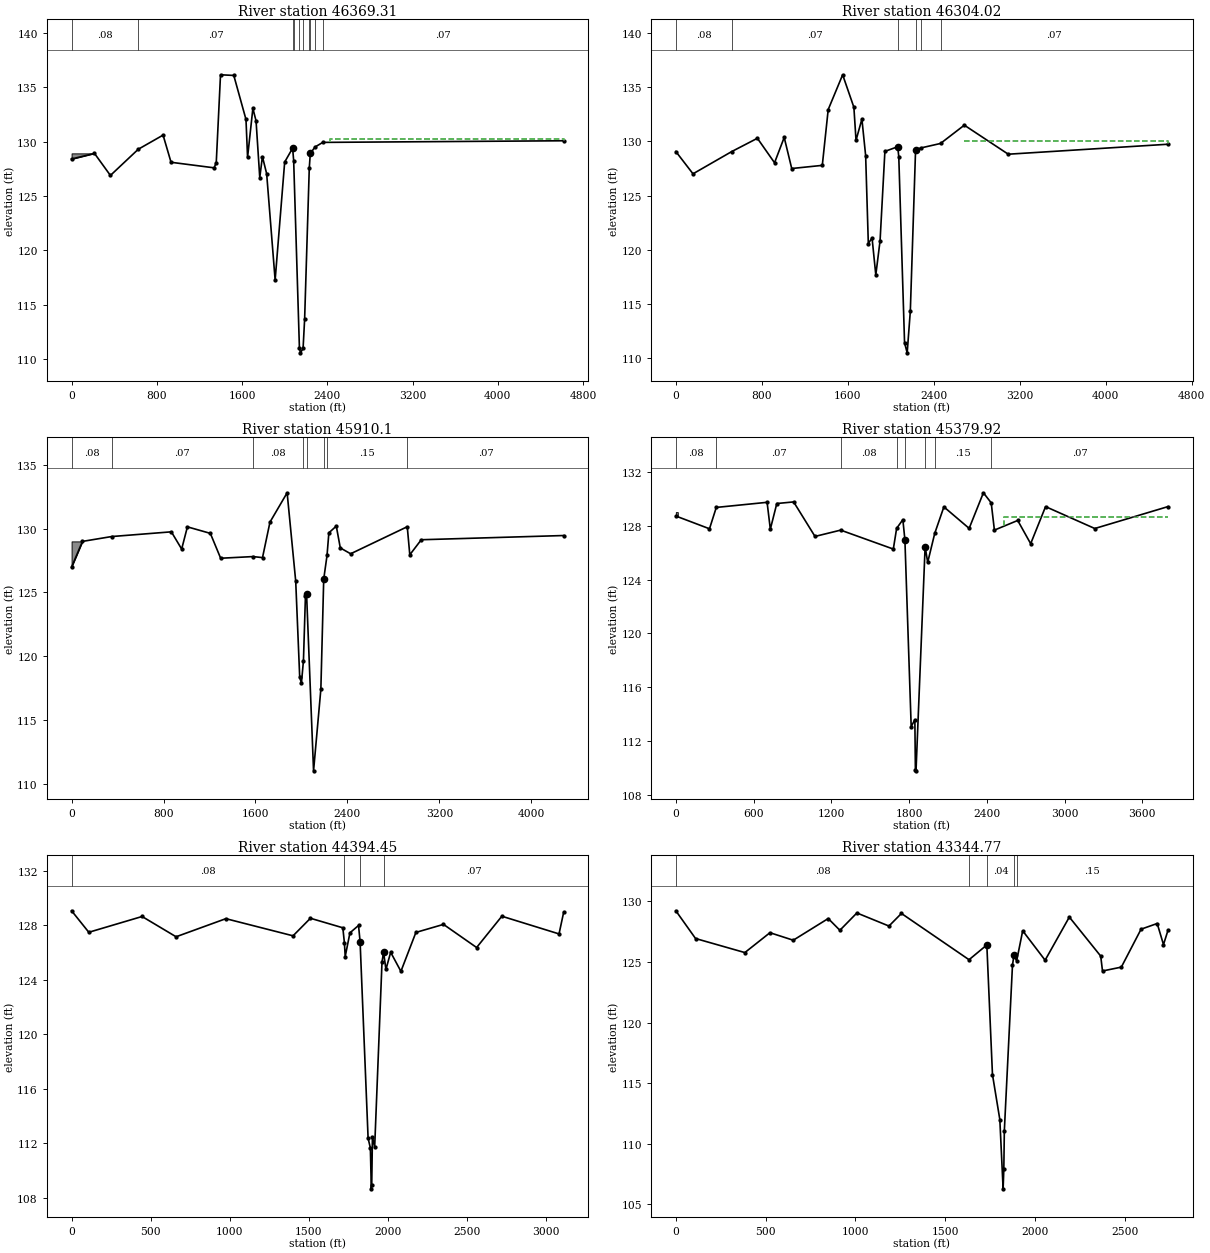
Type RM Length L Ch R = 1 ,46369.31,65.22,65.3,65.22
BEGIN DESCRIPTION:
Downstream Section (WEIR DS FRY RD)
END DESCRIPTION:
Node Name=O
XS GIS Cut Line= 6
3010548.8006055213873503.49397643009609.1971697813872376.1022023
3009076.8501373513872095.17986393008997.01007394 13871944.109956
3008618.8553184413871493.41072623008559.9341764513869704.3496718
#Sta/Elev= 30
       0  128.41  214.65  128.93  364.41   126.9  625.96  129.31   858.6  130.61
  933.48  128.11 1337.82   127.6 1357.78  128.08 1397.72  136.16 1522.33   136.1
 1636.74  132.05 1651.66  128.57 1701.41  133.07 1731.26  131.92 1766.08   126.7
 1790.95  128.63 1830.75  127.06 1910.34  117.28 1999.88  128.13 2074.44  129.41
 2084.28  128.26 2138.37  110.99  2148.2  110.58 2172.57  110.99  2187.1  113.67
 2230.71  127.56  2240.4  128.93 2285.27  129.52 2357.45  129.94 4618.75  130.09
#Mann= 10 ,-1 , 0
       0     .08       0  625.96     .07       0 2074.44     .04       0
 2084.28    .015       0 2138.37     .04       0 2172.57    .015       0
 2230.71     .04       0  2240.4     .07       0 2285.27     .15       0
 2357.45     .07       0
#XS Ineff= 2 ,-1
       0 2074.44  128.22 2429.86 4618.75  130.24
Permanent Ineff=
       F       F
#Block Obstruct= 2 , 0
       0  214.65  128.93               0
Bank Sta=2074.44,2240.4
XS Rating Curve= 0 ,0
Exp/Cntr=0.5,0.3

Type RM Length L Ch R = 1 ,46304.02,410.07,393.92,369.86
XS GIS Cut Line= 6
3010601.7525993613873464.1193832 3009662.149163613872336.7276091
3009129.8021311913872055.80527073009049.9620677813871904.7353629
3008671.80731228 13871454.036133 3008613.956706213869704.8001302
#Sta/Elev= 30
       0  129.07  159.74  127.01  519.36  129.06  758.76  130.29   918.5  128.03
 1008.35  130.37 1078.24   127.5 1362.78  127.79 1417.69  132.94 1552.17  136.15
 1656.64  133.15 1676.54   130.1 1731.26  132.06 1766.08  128.69 1790.95  120.58
 1825.77  121.09  1860.6  117.68 1900.39  120.85 1945.16  129.08 2064.55  129.51
 2074.41  128.58 2128.11  111.42 2152.52  110.49 2181.82  114.35 2230.64  129.24
 2285.27  129.41 2462.54  129.81 2684.13   131.5    3093  128.82 4578.92  129.74
#Mann= 6 ,-1 , 0
       0     .08       0  519.36     .07       0 2064.55     .04       0
 2230.64     .07       0 2285.27     .15       0 2462.54     .07       0
#XS Ineff= 2 ,-1
       0 2064.55  128.12 2684.13 4578.92     130
Permanent Ineff=
       F       F
Bank Sta=2064.55,2230.64
XS Rating Curve= 0 ,0
Exp/Cntr=0.3,0.1

Type RM Length L Ch R = 1 ,45910.1 ,524.22,530.18,541.28
Node Name=N
XS GIS Cut Line= 5
3010829.8472875213873391.62937073009683.1756963613872009.5711112
3009486.3499745313871857.63998463009299.79293294 13871650.913692
3008900.42037211 13869733.228551
#Sta/Elev= 30
       0  126.98   94.78  128.99  348.35  129.37  867.98  129.74  957.77  128.39
 1007.65  130.13 1207.19  129.62 1296.98  127.67 1577.63   127.8 1661.13  127.72
 1725.98   130.5 1875.38   132.8 1949.97  125.87 1984.78  118.35  1999.7  117.88
 2017.34  119.65 2034.51  124.68 2044.46  124.89 2105.19  111.01 2168.77  117.41
 2193.63  126.03 2222.46  127.89 2238.38  129.66 2303.02  130.19  2337.9  128.48
 2427.85  128.02 2920.48  130.14 2942.55  127.94 3042.49  129.12 4281.76  129.45
#Mann= 8 ,-1 , 0
       0     .08       0  348.35     .07       0 1577.63     .08       0
 2017.34     .07       0 2044.46     .04       0 2193.63     .07       0
 2222.46     .15       0 2920.48     .07       0
#XS Ineff= 2 ,-1
       0 2044.46  124.89 2303.02 4281.76   128.7
Permanent Ineff=
       F       F
#Block Obstruct= 2 , 0
       0   94.78  128.99               0
Bank Sta=2044.46,2193.63
XS Rating Curve= 0 ,0
Exp/Cntr=0.3,0.1

Type RM Length L Ch R = 1 ,45379.92,973.98,985.47,984.21
XS GIS Cut Line= 5
3010846.6605741113873136.06623353009968.3798503613871682.4198626
3009898.6798585213871548.38994693009850.4201125213871473.3198871
3009087.8907976913869777.6730159
#Sta/Elev= 30
       0  128.74  259.75  127.79  312.24  129.38  704.32  129.76   729.3  127.76
  779.25  129.67  909.13  129.79 1073.97  127.22 1272.08  127.69 1678.39  126.28
 1703.99  127.82 1751.98  128.47 1767.77  126.97 1816.28  113.06 1844.57  113.58
 1848.77  109.83 1853.52  109.77 1923.81  126.46 1943.68  125.29 1998.06  127.45
 2068.63  129.42 2263.55  127.82  2373.5  130.47 2433.87  129.72 2458.46  127.69
 2638.39  128.41 2738.34  126.68 2853.29  129.44 3233.13  127.81 3797.89  129.44
#Mann= 8 ,-1 , 0
       0     .08       0  312.24     .07       0 1272.08     .08       0
 1703.99     .07       0 1767.77     .04       0 1923.81     .07       0
 1998.06     .15       0 2433.87     .07       0
#XS Ineff= 1 ,-1
 2533.43 3797.89  128.64
Permanent Ineff=
       F
#Block Obstruct= 2 , 0
       0   14.99  129.03               0
Bank Sta=1767.77,1923.81
XS Rating Curve= 0 ,0
Exp/Cntr=0.3,0.1

Type RM Length L Ch R = 1 ,44394.45,1021.81,1049.68,1065.08
XS GIS Cut Line= 6
 3011525.129689613872842.22561383011387.7198594413872460.3398947
3010794.0501150313871232.05002843010761.8900743613871098.0099422
3010482.4431266913870256.56313433010464.7666528713869940.6405378
#Sta/Elev= 30
       0  129.08  108.89   127.5  445.83  128.66  660.71  127.17  975.53   128.5
  1400.3  127.24 1510.24  128.53 1715.12  127.83 1725.31   126.7 1730.12  125.72
  1760.1  127.46  1814.4     128 1824.25  126.82 1874.91  112.37 1889.22  111.65
 1895.26  108.65 1897.88  108.96  1902.3  112.47 1916.48  111.73 1962.75   125.3
 1972.72  126.03 1987.67  124.77 2017.57  126.03 2082.38  124.63 2177.12  127.49
 2351.64  128.08 2561.07  126.38 2720.63  128.68 3082.18  127.38 3111.84  128.99
#Mann= 4 ,-1 , 0
       0     .08       0 1725.31     .07       0 1824.25     .04       0
 1972.72     .07       0
Bank Sta=1824.25,1972.72
XS Rating Curve= 0 ,0
Exp/Cntr=0.3,0.1

Type RM Length L Ch R = 1 ,43344.77,947.22,951.7,928.07
Node Name=M
XS GIS Cut Line= 6
3011861.0102514513872732.94400833011772.2446809413871758.0502888
3011785.9398635313871098.00994223011785.9398635313870915.7199524
3011785.9398635313870824.58004293011775.5727582713869995.2575545
#Sta/Elev= 30
       0  129.23  109.88  126.94  384.58  125.78  524.42  127.42  654.28   126.8
  849.07  128.59     914  127.62 1008.71  129.05  1187.4  127.97  1256.9  129.01
 1633.59  125.19 1732.72  126.41 1764.13  115.71 1805.12     112 1823.46  106.28
 1827.35  107.88 1830.25  111.07 1875.68  124.76 1883.76  125.54 1898.92   125.1
 1932.52  127.58 2057.43  125.15 2192.33  128.71  2367.2  125.49 2377.19  124.26
 2482.11  124.58 2592.03  127.71 2681.96  128.18 2716.93  126.44 2741.91  127.61
#Mann= 5 ,-1 , 0
       0     .08       0 1633.59     .07       0 1732.72     .04       0
 1883.76     .07       0 1898.92     .15       0
Bank Sta=1732.72,1883.76
XS Rating Curve= 0 ,0
Exp/Cntr=0.3,0.1

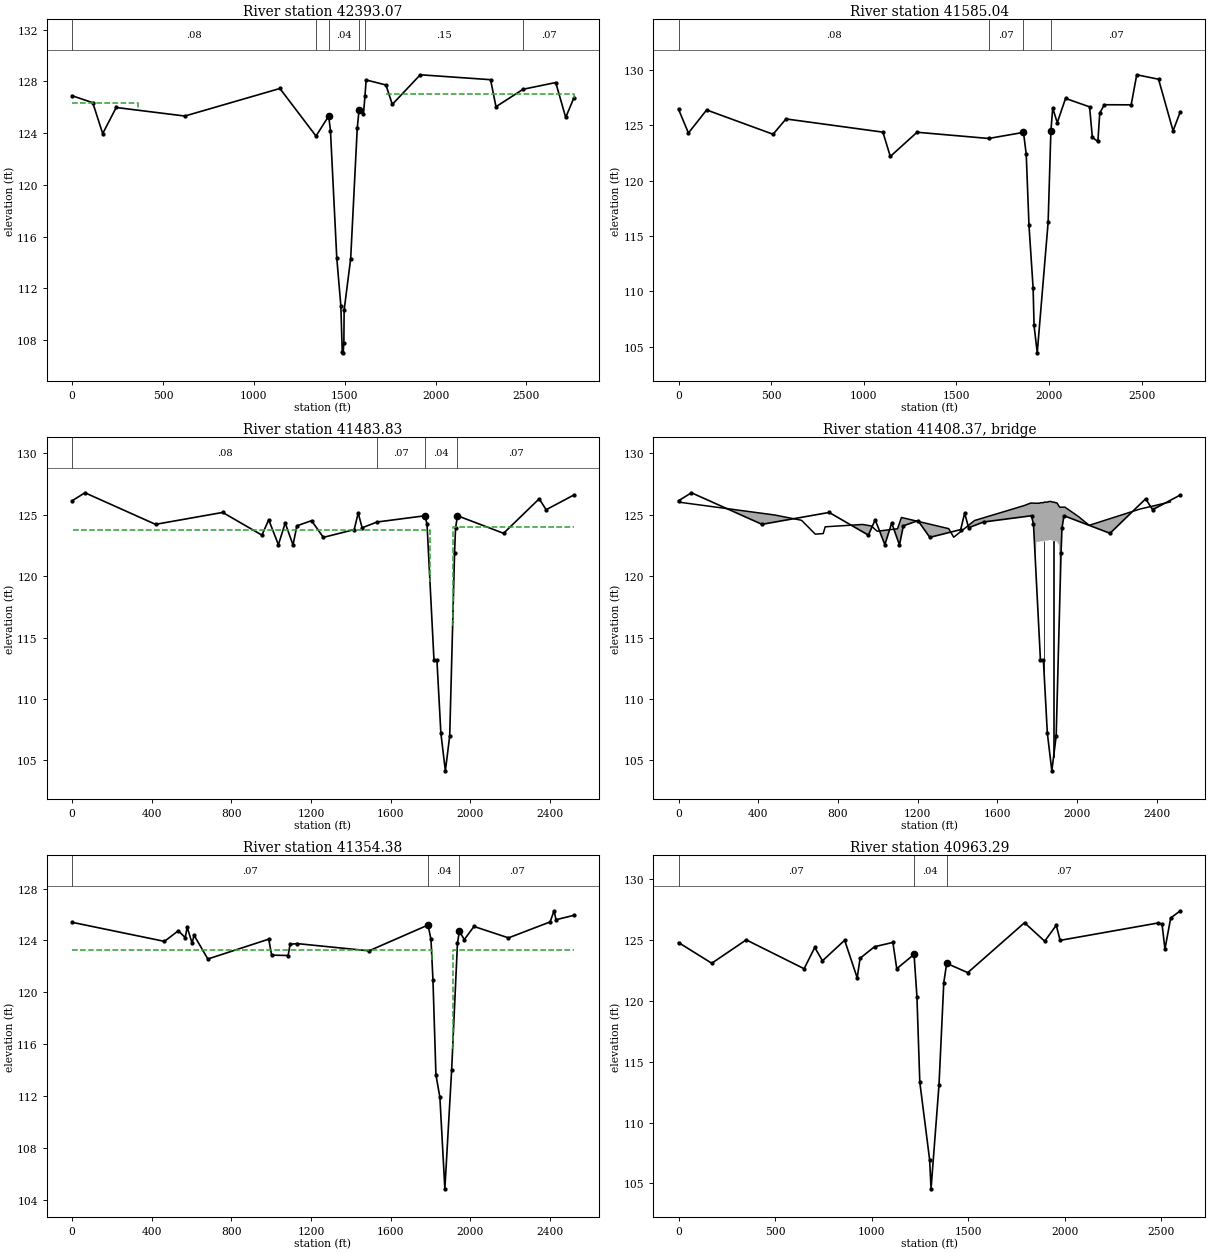
Type RM Length L Ch R = 1 ,42393.07,840.18,808.02,791.27
XS GIS Cut Line= 6
3012580.3893901113872557.43714143012661.8613400313872189.8053308
3012702.7700508513871076.57002443012679.2392580213870741.5821774
3012388.0820319513870384.22757713012116.1826413613869996.9045328
#Sta/Elev= 30
       0  126.89  113.96  126.35  168.46  123.96  242.78  125.98  620.55  125.32
 1143.41  127.45 1342.09  123.77 1411.83  125.32 1421.67  124.17  1456.2  114.37
 1478.75  110.64 1486.28  107.11 1491.33  107.01 1495.34  107.79 1496.77   110.3
 1532.78   114.3 1568.92  124.37 1578.72  125.77 1603.21   125.5 1611.31  126.84
  1617.9  128.11 1726.89  127.72 1761.75  126.22 1915.71  128.51 2302.38  128.13
 2332.27  126.04 2481.28  127.39 2661.04  127.91 2715.84  125.21 2760.67  126.72
#Mann= 6 ,-1 , 0
       0     .08       0 1342.09     .07       0 1411.83     .04       0
 1578.72     .07       0 1611.31     .15       0 2481.28     .07       0
#XS Ineff= 2 ,-1
       0  361.69  126.35 1726.89 2760.67     127
Permanent Ineff=
       F       F
Bank Sta=1411.83,1578.72
XS Rating Curve= 0 ,0
Exp/Cntr=0.3,0.1

Type RM Length L Ch R = 1 ,41585.04,75.25,101.22,110.6
Node Name=L
XS GIS Cut Line= 6
3012720.8825474413872529.3906096 3013413.890019713871414.7799779
3013469.1500797713870917.42008033013418.9100227813870671.2499689
3013335.5558587813870250.24129653013295.71210644 13870038.535027
#Sta/Elev= 30
       0  126.42   53.41  124.28  151.65  126.36  510.36  124.17  580.11  125.55
 1103.23  124.36 1143.09  122.17 1287.57  124.35 1674.06  123.79 1862.17  124.34
 1876.95  122.36 1891.73  115.97  1914.1   110.3 1919.11  106.96 1936.34  104.47
 1995.18  116.25 2009.96  124.43 2019.81  126.54 2044.45  125.21  2089.1   127.4
 2218.85  126.64 2233.83  123.89 2263.77  123.52 2273.75  126.08  2298.7  126.83
 2443.42  126.82 2473.37  129.53 2591.25  129.13 2669.58  124.48 2708.75   126.2
#Mann= 4 ,-1 , 0
       0     .08       0 1674.06     .07       0 1862.17     .04       0
 2009.96     .07       0
#XS Ineff= 2 ,-1
       0 1639.35  123.72  2089.1 2708.75     125
Permanent Ineff=
       F       F
Bank Sta=1862.17,2009.96
XS Rating Curve= 0 ,0
Exp/Cntr=0.5,0.3

Type RM Length L Ch R = 1 ,41483.83,129.19,129.45,128.52
BEGIN DESCRIPTION:
Upstream Section (GREENHOUSE ROAD)
END DESCRIPTION:
XS GIS Cut Line= 6
3012824.1628526913872434.38915923013253.9871242813871906.6441517
3013344.4026258613871729.92337653013457.4863891913871397.4479916
3013522.9911794413870996.93140423013566.6744910313870117.0233871
#Sta/Elev= 30
       0  126.14   64.82  126.79  418.83  124.22  756.07  125.19  953.13  123.34
  987.18  124.59 1035.84  122.56    1070  124.33 1109.12  122.54 1128.68   124.1
 1202.03  124.52 1261.36  123.16 1416.34  123.79 1436.34  125.14 1456.16  123.94
 1531.22  124.41 1771.96  124.92 1781.89  124.22 1816.65  113.21 1831.54  113.18
  1851.4  107.22 1873.93  104.15 1895.74  106.99 1920.13  121.88 1925.01  123.91
 1934.77  124.92 2166.02  123.49 2344.99   126.3 2379.79  125.41 2518.99  126.61
#Mann= 4 ,-1 , 0
       0     .08       0 1531.22     .07       0 1771.96     .04       0
 1934.77     .07       0
#XS Ineff= 2 ,-1
     2.9 1796.79  123.72 1910.37 2518.99  124.01
Permanent Ineff=
       F       F
Bank Sta=1771.96,1934.77
XS Rating Curve= 0 ,0
Exp/Cntr=0.5,0.3

Type RM Length L Ch R = 3 ,41408.37,,,
BEGIN DESCRIPTION:
GREENHOUSE ROAD
END DESCRIPTION:
Node Name=GREENHOUSE ROAD
Bridge Culvert--1,0,-1,-1, 0
Deck Dist Width WeirC Skew NumUp NumDn MinLoCord MaxHiCord MaxSubmerge Is_Ogee
32,90,2.6,0, 55, 55, , , 0.98, 0, 0,0,,
       0  483.65  617.43   686.6   726.3  736.22  923.93  967.72  996.92 1099.34
  1118.9 1356.35 1381.34 1485.63 1737.21    1767 1771.96 1776.93 1781.89 1786.86
 1791.82 1796.79 1801.75 1806.72 1811.68 1816.65 1821.61 1826.57 1831.54  1836.5
 1841.47 1846.43  1851.4 1856.36 1861.33 1866.29 1871.26 1876.22  1881.1 1885.98
 1890.86 1895.74 1900.62  1905.5 1910.37 1915.25 1920.13 1925.01 1929.89 1934.77
 1939.65 2007.95 2061.61 2315.16 2469.28
  126.03  124.98  124.55  123.42  123.47  124.02  124.21  124.09  123.66  123.86
  124.78  123.87  123.17  124.53  125.76  125.95  125.95  125.95  125.95  125.94
  125.94  125.94  125.94  125.94  125.94  125.98  125.98  125.98  125.98  126.03
  126.03  126.03  126.03  126.06  126.08  126.08  126.08  126.03  126.03  126.03
  125.98  125.98  125.95  125.81  125.69  125.61  125.61  125.62  125.62  125.62
  125.62  124.85  124.14  125.46  126.05
       0       0       0       0       0       0       0       0       0       0
       0       0       0       0       0       0       0       0       0       0
       0   122.8   122.8   122.8   122.8  122.84  122.84  122.84  122.84  122.89
  122.89  122.89  122.89  122.92  122.94  122.94  122.94  122.89  122.89  122.89
  122.84  122.84  122.81  122.67  122.55       0       0       0       0       0
       0       0       0       0       0
       0  483.65  617.43   686.6   726.3  736.22  923.93  967.72  996.92 1099.34
  1118.9 1356.35 1381.34 1485.63 1737.21    1767 1771.96 1776.93 1781.89 1786.86
 1791.82 1796.79 1801.75 1806.72 1811.68 1816.65 1821.61 1826.57 1831.54  1836.5
 1841.47 1846.43  1851.4 1856.36 1861.33 1866.29 1871.26 1876.22  1881.1 1885.98
 1890.86 1895.74 1900.62  1905.5 1910.37 1915.25 1920.13 1925.01 1929.89 1934.77
 1939.65 2007.95 2061.61 2315.16 2469.28
  126.03  124.98  124.55  123.42  123.47  124.02  124.21  124.09  123.66  123.86
  124.78  123.87  123.17  124.53  125.76  125.95  125.95  125.95  125.95  125.94
  125.94  125.94  125.94  125.94  125.94  125.98  125.98  125.98  125.98  126.03
  126.03  126.03  126.03  126.06  126.08  126.08  126.08  126.03  126.03  126.03
  125.98  125.98  125.95  125.81  125.69  125.61  125.61  125.62  125.62  125.62
  125.62  124.85  124.14  125.46  126.05
       0       0       0       0       0       0       0       0       0       0
       0       0       0       0       0       0       0       0       0       0
       0  122.69  122.69  122.69  122.69  122.73  122.73  122.73  122.73  122.78
  122.78  122.78  122.78  122.81  122.83  122.83  122.83  122.78  122.78  122.78
  122.73  122.73   122.7  122.56  122.44       0       0       0       0       0
       0       0       0       0       0
Pier Skew, UpSta & Num, DnSta & Num=  ,1834.83, 2 ,1834.83, 2 , 0 , 0 , 0 ,,
     1.4     1.4
     100   123.9
     1.4     1.4
     100   123.9
Pier Skew, UpSta & Num, DnSta & Num=  ,1882.73, 2 ,1882.73, 2 , 0 , 0 , 0 ,,
     1.4     1.4
     100   123.9
     1.4     1.4
     100   123.9
BR Coef=-1 , 1 , 1 ,0.9, 0 ,,,0.8,-1,1.2,0,
WSPro=,,,, 1 ,,,, 0 ,,,, 0 ,,,,-1 ,-1 ,-1 , 0 , 0 , 0 , 0 , 0
BC Design=,, 0 ,, 0 ,,,,,,
BC Use User HTab Curves=0
BC User HTab FreeFlow(D)= 0

Type RM Length L Ch R = 1 ,41354.38,400.11,391.09,382.33
BEGIN DESCRIPTION:
Downstream Section (GREENHOUSE ROAD)
END DESCRIPTION:
XS GIS Cut Line= 6
3012952.0280825213872450.85106853013381.85235411 13871923.106061
3013472.2678556913871746.38528593013585.3516190213871413.9099009
3013650.8564092813871013.39331353013694.5397208613870133.4852964
#Sta/Elev= 30
       0   125.4  463.71  123.93  533.47  124.75  568.04  124.22  577.92  125.02
  602.61  123.79  612.49   124.4  681.63  122.57  987.18   124.1 1001.78  122.87
 1084.67  122.84 1094.45   123.7 1128.68  123.76 1490.54   123.2 1786.86  125.19
 1801.75  124.08 1811.68  120.95 1826.57  113.64 1846.43   111.9 1871.42  104.84
  1905.5  114.02 1934.77  123.82 1944.53   124.7 1968.92  124.07 2017.71  125.08
 2190.87   124.2 2399.68  125.43 2419.56  126.29 2429.51   125.6 2518.99  125.94
#Mann= 3 ,-1 , 0
       0     .07       0 1786.86     .04       0 1944.53     .07       0
#XS Ineff= 2 ,-1
       0 1806.72   123.3 1910.37 2518.99   123.3
Permanent Ineff=
       F       F
Bank Sta=1786.86,1944.53
XS Rating Curve= 0 ,0
Exp/Cntr=0.5,0.3

Type RM Length L Ch R = 1 ,40963.29,674.43,644.29,613.11
XS GIS Cut Line= 5
3013959.1100578613872072.73010563014018.5200440313871829.1498841
3014054.1699071113870920.1999304 3014042.290009613870587.5201495
3014089.8099276913869482.5200629
#Sta/Elev= 30
       0  124.79  172.06  123.09  350.68  125.01  650.57  122.64  705.54  124.39
  745.53  123.29  860.48  124.98  925.46  121.89  940.45   123.5 1015.42  124.45
 1110.39   124.8 1130.38  122.64 1219.99  123.82  1234.9  120.34  1249.8  113.32
 1300.78  106.93    1308  104.56 1349.17  113.08 1374.02  121.49 1388.92  123.08
 1498.24  122.32 1792.19  126.42 1896.81   124.9  1956.6  126.21 1976.52  124.97
 2484.69   126.4 2504.62   126.3 2519.57  124.25 2549.46  126.81 2599.28   127.4
#Mann= 3 ,-1 , 0
       0     .07       0 1219.99     .04       0 1388.92     .07       0
#XS Ineff= 2 ,-1
       0  875.07   123.3 1792.19 2599.28  126.42
Permanent Ineff=
       F       F
Bank Sta=1219.99,1388.92
XS Rating Curve= 0 ,0
Exp/Cntr=0.3,0.1