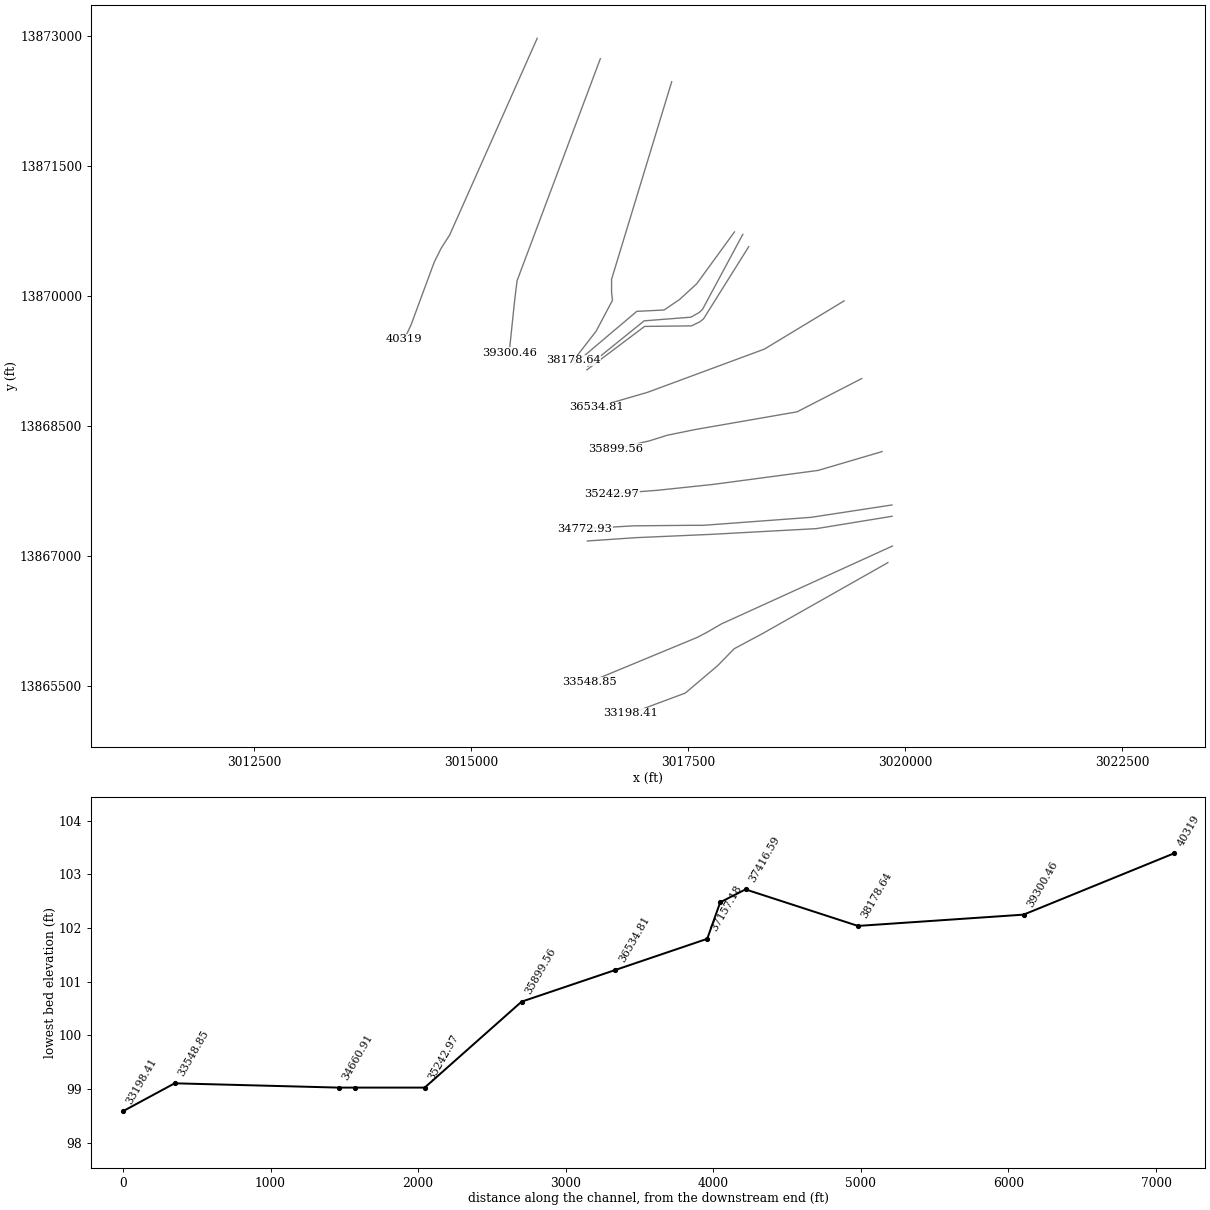
HEC-RAS study U102-00-00.prj: U102-00-00 (Update)

--- U102-00-00.g01 (geometry) --- (continued)

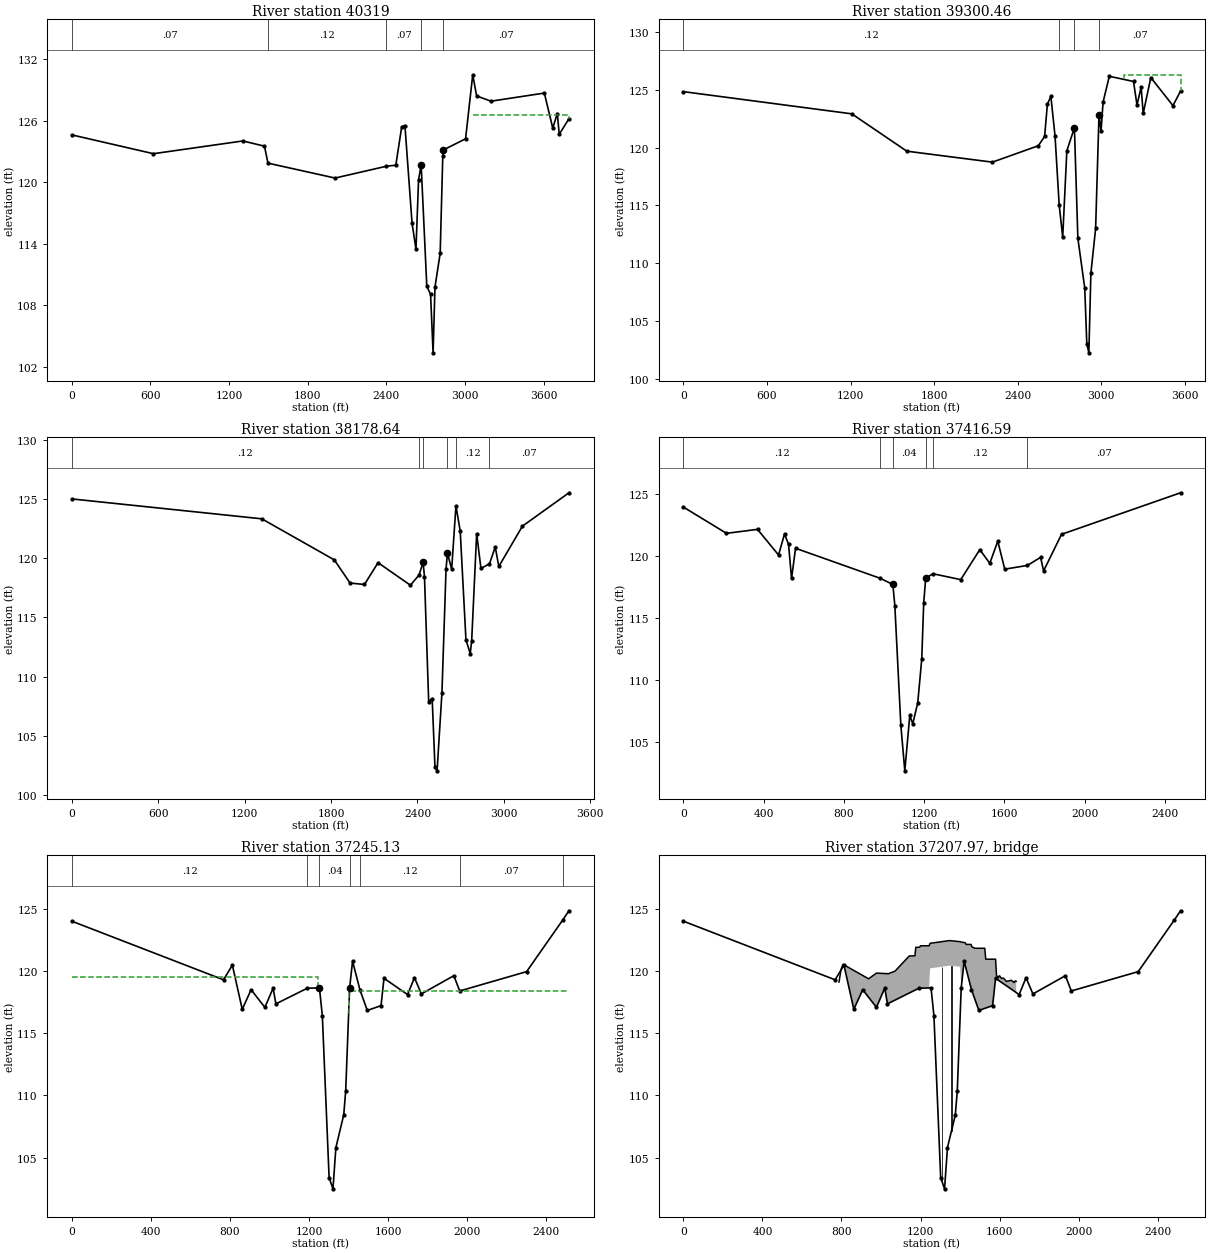
Type RM Length L Ch R = 1 ,40319   ,977.77,1018.54,1038.23
XS GIS Cut Line= 6
 3015759.867611213872969.51407323014750.8801278613870701.2600795
3014654.3701502813870551.13997293014573.9500355313870390.2899009
3014307.2901357713869667.89994153014230.0845815213869501.9649059
#Sta/Elev= 30
       0   124.6  622.86  122.77 1305.59  124.01 1470.17   123.5 1496.85  121.85
 2008.77   120.4 2400.78  121.55 2472.57  121.65 2517.25  125.38 2542.03  125.51
 2596.56  115.99 2626.31  113.48 2646.14  120.24 2665.81  121.69 2708.98  109.86
 2737.75  109.09 2756.94  103.39 2771.33  109.79 2811.01  113.08 2830.95  122.57
 2835.93  123.14 3004.86  124.22  3059.5  130.45 3089.31  128.39 3198.61  127.88
 3605.98  128.67 3670.31  125.26 3704.93  126.68 3719.77  124.66 3793.97  126.18
#Mann= 5 ,-1 , 0
       0     .07       0 1496.85     .12       0 2400.78     .07       0
 2665.81     .04       0 2835.93     .07       0
#XS Ineff= 2 ,-1
       0 2665.81     120  3059.5 3793.67   126.5
Permanent Ineff=
       F       F
Bank Sta=2665.81,2835.93
XS Rating Curve= 0 ,0
Exp/Cntr=0.3,0.1

Type RM Length L Ch R = 1 ,39300.46,1120.02,1121.82,1129.71
XS GIS Cut Line= 6
 3016487.244109213872734.75207553016422.5447635213872562.1015022
3015528.31000344 13870175.8300283015506.8599151113870004.2601612
3015496.1401202813869907.74985553015437.1599232713869344.7900234
#Sta/Elev= 30
       0  124.85  1208.7  122.93 1603.44   119.7 2218.03  118.75 2547.82  120.17
 2592.79  120.97 2612.77  123.76 2637.76  124.45 2667.74  121.01 2697.19  115.08
  2722.7  112.25 2752.45  119.74  2806.8  121.72  2831.5  112.16  2880.9  107.86
 2895.72  103.04 2910.45  102.25 2925.02  109.14 2959.01  113.01 2983.28  122.85
 2997.85  121.44 3012.63  123.95 3057.32  126.18 3231.11  125.73 3255.93  123.69
 3285.72  125.23 3300.62  122.96 3355.24  126.07 3514.13  123.64 3568.74   124.9
#Mann= 4 ,-1 , 0
       0     .12       0 2697.19     .07       0  2806.8     .04       0
 2983.28     .07       0
#XS Ineff= 2 ,-1
       0  2806.8  119.75 3161.59 3568.74  126.31
Permanent Ineff=
       F       F
Bank Sta=2806.8,2983.28
XS Rating Curve= 0 ,0
Exp/Cntr=0.3,0.1

Type RM Length L Ch R = 1 ,38178.64,818.28,762.05,670.37
XS GIS Cut Line= 6
3017309.38780612 13872469.4041813016616.6998870213870191.9100484
3016616.6998870213870036.43004443016627.4200099413869950.6398616
3016439.9489281913869595.42633323016178.2247141213869257.1392801
#Sta/Elev= 30
       0  125.02 1318.92  123.34  1822.3  119.87 1931.95  117.91 2031.63  117.79
 2126.32  119.63  2350.6  117.73 2410.48  118.58 2438.81  119.66 2448.53  118.46
 2477.68   107.9 2501.97  108.14 2521.41  102.33 2535.98  102.04 2569.61  108.59
 2598.43  119.14 2608.03  120.43 2637.32  119.09 2667.07  124.44 2696.82  122.29
 2736.49  113.11 2766.24  111.95 2776.16  113.02 2810.87  122.08 2840.62  119.15
 2899.72  119.53  2939.8  120.96 2964.59  119.31 3128.53  122.72 3451.81  125.54
#Mann= 6 ,-1 , 0
       0     .12       0 2410.48     .07       0 2438.81     .04       0
 2608.03     .07       0 2667.07     .12       0 2899.72     .07       0
#XS Ineff= 1 ,-1
 2667.07 3451.81   119.5
Permanent Ineff=
       F
Bank Sta=2438.81,2608.03
XS Rating Curve= 0 ,0
Exp/Cntr=0.3,0.1

Type RM Length L Ch R = 1 ,37416.59,201.76,171.46,120.65
Node Name=K
XS GIS Cut Line= 6
3018032.2899036113870737.7800196 3017597.850155713870140.4199938
3017402.0798779413869960.75007763017221.5900814413869837.8599034
3016907.3899224413869822.35009193016189.1019889413869214.5629217
#Sta/Elev= 30
       0  123.92   214.6  121.81  369.32  122.13  474.12  120.07  504.07  121.76
  524.03  120.92     539  118.18  558.96  120.61  982.04  118.19 1044.05   117.7
 1053.98  115.98 1083.75   106.4  1103.6  102.72 1128.42  107.17  1143.3   106.5
 1168.12  108.19 1187.97  111.69 1197.89  116.23 1207.82  118.21 1244.37  118.56
  1382.5  118.09 1477.37   120.5  1527.3   119.4 1567.08  121.18 1601.83  118.93
 1714.63  119.23 1780.56  119.88 1795.45  118.79 1884.82  121.73 2478.22  125.07
#Mann= 6 ,-1 , 0
       0     .12       0  982.04     .07       0 1044.05     .04       0
 1207.82     .07       0 1244.37     .12       0 1714.63     .07       0
#XS Ineff= 2 ,-1
       0  634.03   119.5 1572.04 2478.22   119.5
Permanent Ineff=
       F       F
Bank Sta=1044.05,1207.82
XS Rating Curve= 0 ,0
Exp/Cntr=0.5,0.3

Type RM Length L Ch R = 1 ,37245.13,98.67,87.94,84.77
BEGIN DESCRIPTION:
Upstream Section (OLD GREENHOUSE)
END DESCRIPTION:
XS GIS Cut Line= 6
3018128.3002102813870709.62325183017663.8142626113869844.4051659
3017626.8743758613869809.82649493017531.6058656113869755.1297539
 3016992.254910213869713.01139993016345.1597476913869190.3428258
#Sta/Elev= 30
       0  124.04  767.67  119.32  812.53   120.5  862.38  116.94  907.24  118.52
  977.03   117.1 1018.81  118.65 1032.61  117.38 1191.45  118.64 1253.17  118.67
 1267.83  116.41 1302.03  103.38 1321.57  102.48 1336.31   105.8 1376.05  108.44
 1385.98  110.37 1405.84  118.66 1420.74  120.82  1457.9  118.52 1495.27  116.85
 1564.86  117.24 1579.77  119.44  1699.1  118.13 1733.97  119.49 1768.83  118.18
 1933.21  119.65 1963.03  118.42  2301.8  119.98 2484.03  124.13 2515.98  124.88
#Mann= 7 ,-1 , 0
       0     .12       0 1191.45     .07       0 1253.17     .04       0
 1405.84     .07       0  1457.9     .12       0 1963.03     .07       0
 2484.03     .15       0
#XS Ineff= 2 ,-1
       0 1248.28  119.53 1400.88 2515.98  118.38
Permanent Ineff=
       F       F
Bank Sta=1253.17,1405.84
XS Rating Curve= 0 ,0
Exp/Cntr=0.5,0.3

Type RM Length L Ch R = 3 ,37207.97,,,
BEGIN DESCRIPTION:
OLD GREENHOUSE
END DESCRIPTION:
Node Name=OLD GREENHOUSE
Bridge Culvert--1,0,-1,-1, 0
Deck Dist Width WeirC Skew NumUp NumDn MinLoCord MaxHiCord MaxSubmerge Is_Ogee
20,35,2.6,0, 35, 35, , , 0.98, 0, 0,0,,
   787.6  797.57  807.54  937.15  977.03 1037.41    1071 1142.93 1171.44  1176.2
 1195.21 1199.96  1243.4 1248.28 1346.25 1400.88 1405.85 1425.71 1430.68 1455.51
 1460.48 1475.39 1525.09 1530.06 1579.77 1584.74 1594.69 1599.66  1609.6 1619.54
 1634.45 1659.31 1674.22 1679.19 1684.16
  119.14  120.15  120.57   119.4  119.86  119.81  120.02  121.24  121.25  121.94
  121.94  122.06  122.06  122.26  122.48  122.39  122.36  122.31  122.17  122.17
  121.97  121.86  121.86  120.98  120.98  119.65  119.52  119.65  119.43  119.46
  119.19  119.28   119.1  119.23   119.2
       0       0       0       0       0       0       0       0       0       0
       0       0       0  120.24  120.46  120.37       0       0       0       0
       0       0       0       0       0       0       0       0       0       0
       0       0       0       0       0
   787.6  797.57  807.54  937.15  977.03 1037.41    1071 1142.93 1171.44  1176.2
 1195.21 1199.96  1243.4 1248.28 1346.25 1400.88 1405.85 1425.71 1430.68 1455.51
 1460.48 1475.39 1525.09 1530.06 1579.77 1584.74 1594.69 1599.66  1609.6 1619.54
 1634.45 1659.31 1674.22 1679.19 1684.16
  119.14  120.15  120.57   119.4  119.86  119.81  120.02  121.24  121.25  121.94
  121.94  122.06  122.06  122.26  122.48  122.39  122.36  122.31  122.17  122.17
  121.97  121.86  121.86  120.98  120.98  119.65  119.52  119.65  119.43  119.46
  119.19  119.28   119.1  119.23   119.2
       0       0       0       0       0       0       0       0       0       0
       0       0       0  120.15  120.37  120.28       0       0       0       0
       0       0       0       0       0       0       0       0       0       0
       0       0       0       0       0
Pier Skew, UpSta & Num, DnSta & Num=  ,1309.07, 2 ,1309.07, 2 , 0 , 0 , 0 ,,
     1.4     1.4
     100  121.43
     1.4     1.4
     100  121.34
Pier Skew, UpSta & Num, DnSta & Num=  ,1356.67, 2 ,1356.67, 2 , 0 , 0 , 0 ,,
     1.4     1.4
     100  121.43
     1.4     1.4
     100  121.34
Abutment Skew #Up #Dn= , 2 , 2
 1244.37 1264.67
  120.24  118.47
 1244.37 1264.67
  120.15  118.38
BR Coef=-1 , 1 , 1 ,0.9, 0 ,,,0.8,-1,1.2,0,
WSPro=,,,, 1 ,,,, 0 ,,,, 0 ,,,,-1 ,-1 ,-1 , 0 , 0 , 0 , 0 , 0
BC Design=,, 0 ,, 0 ,,,,,,
BC Use User HTab Curves=0
BC User HTab FreeFlow(D)= 0

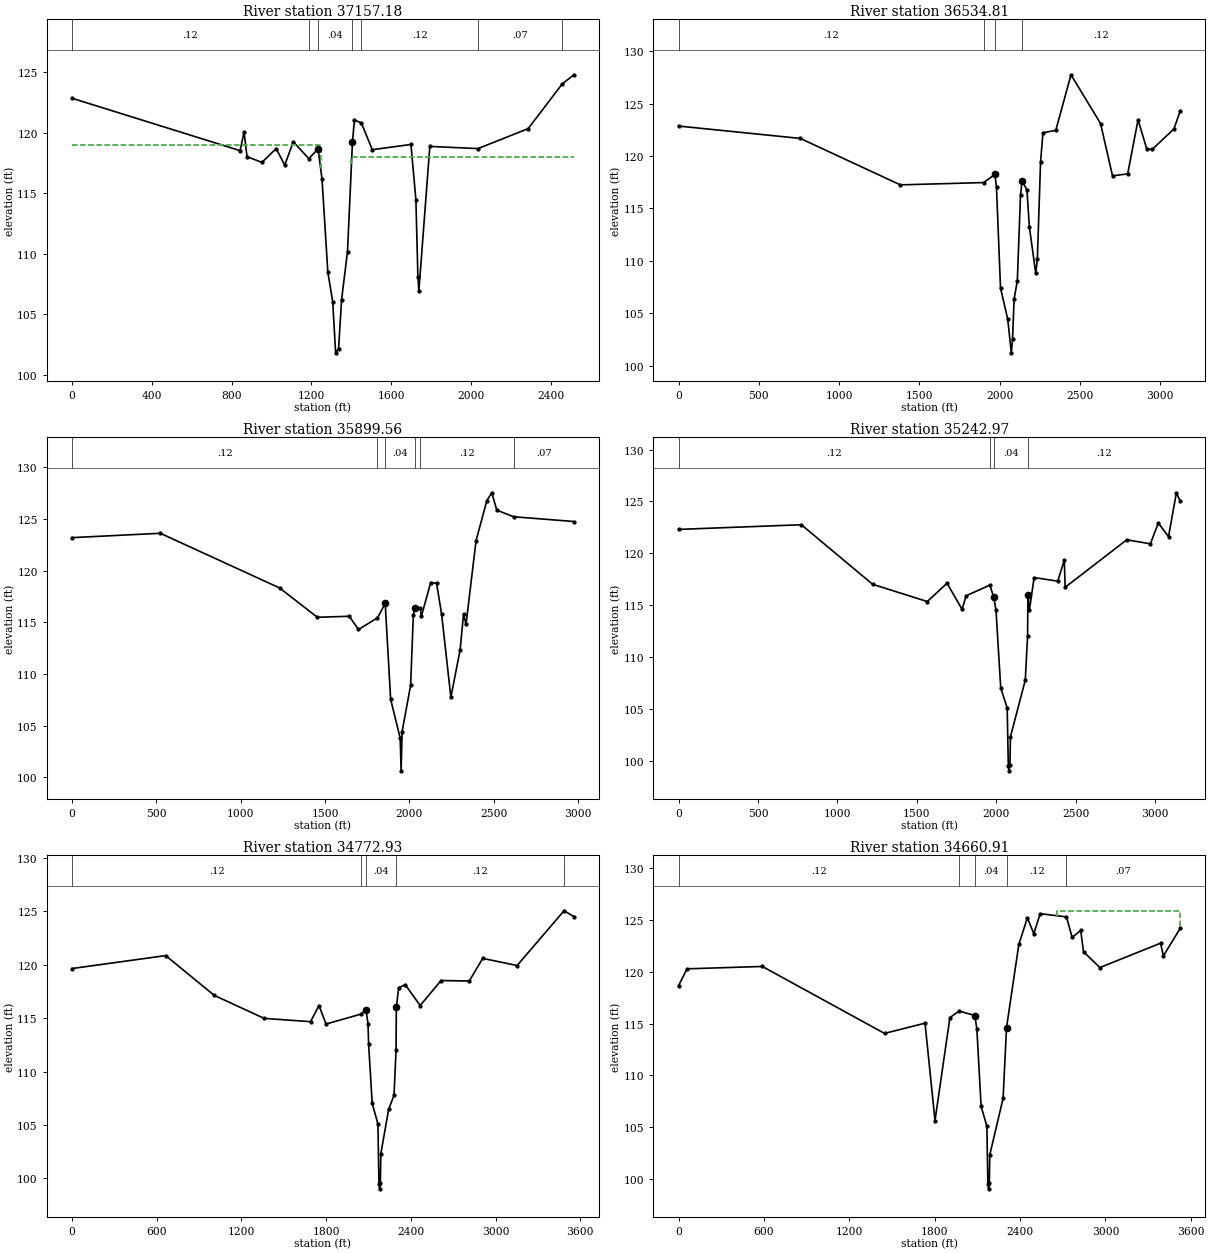
Type RM Length L Ch R = 1 ,37157.18,615.28,622.37,651.62
BEGIN DESCRIPTION:
Downstream Section (OLD GREENHOUSE)
END DESCRIPTION:
XS GIS Cut Line= 6
3018196.4667406113870567.72589783017675.6419948613869735.2052531
3017636.4908264413869703.15151143017537.8056563613869654.8911093
3016996.84906112 13869648.6224213016332.4737494413869148.1024247
#Sta/Elev= 30
       0  122.84  842.44  118.51  862.38  120.05  877.33  118.01   952.1  117.54
 1023.41  118.68  1066.2  117.31 1109.36  119.24 1186.94  117.85 1233.62  118.66
 1253.17  116.17 1282.48  108.46 1306.91  106.02 1321.57   101.8 1336.31  102.14
 1351.21  106.18 1381.01  110.17 1405.84  119.21 1415.78  121.05 1450.74  120.79
 1505.21  118.59  1699.1  119.02    1724  114.44 1733.97  108.08 1738.95  106.93
 1793.74  118.86 2035.39  118.68 2286.85  120.33 2457.62  124.02 2515.98  124.78
#Mann= 7 ,-1 , 0
       0     .12       0 1186.94     .07       0 1233.62     .04       0
 1405.84     .07       0 1450.74     .12       0 2035.39     .07       0
 2457.62     .15       0
#XS Ineff= 2 ,-1
       0 1248.28     119 1400.88 2515.98     118
Permanent Ineff=
       F       F
Bank Sta=1233.62,1405.84
XS Rating Curve= 0 ,0
Exp/Cntr=0.5,0.3

Type RM Length L Ch R = 1 ,36534.81,631.1,635.26,605.75
XS GIS Cut Line= 4
3019295.3447921913869942.69040243018377.5359322713869387.2581144
3017029.6498485213868888.26009663016437.7048381913868716.6128021
#Sta/Elev= 30
       0  122.85  758.44  121.67  1382.2  117.24 1900.42  117.46 1971.09  118.23
 1981.07  116.99 2006.02  107.41 2050.94  104.44 2073.39  101.22 2080.88  102.51
 2090.86  106.36 2110.82  108.09 2130.78   116.3 2140.77  117.59 2170.71  116.77
 2185.68  113.26 2225.61  108.79 2235.59  110.14 2255.55  119.42 2270.52  122.21
 2350.37  122.44 2445.19  127.74 2629.35  123.09 2703.91   118.1 2798.34  118.29
 2862.96  123.44 2917.63  120.65 2952.42  120.64 3086.62  122.58 3126.39  124.32
#Mann= 4 ,-1 , 0
       0     .12       0 1900.42     .07       0 1971.09     .04       0
 2140.77     .12       0
#XS Ineff= 1 ,-1
 2140.77 2445.19     115
Permanent Ineff=
       F
Bank Sta=1971.09,2140.77
XS Rating Curve= 0 ,0
Exp/Cntr=0.3,0.1

Type RM Length L Ch R = 1 ,35899.56,671.2,656.58,762.76
XS GIS Cut Line= 6
3019498.3073127713869047.57309823018753.8337361113868664.0325267
3017581.7799778613868460.13004743017258.9738649413868394.1797199
3017052.3466535213868329.39736923016660.1551806913868236.3476865
#Sta/Elev= 30
       0   123.2  523.41  123.62 1230.85  118.33 1454.94  115.49 1644.17  115.59
 1698.94  114.31 1811.58  115.43 1857.35  116.83 1889.59  107.56 1946.23  103.79
 1951.67  100.63 1957.44  104.41 2008.08  108.91 2024.11  115.69 2032.23  116.37
 2064.88  116.39 2072.16   115.6 2127.07  118.85 2162.02  118.79 2191.97  115.78
 2246.88  107.75  2301.8  112.35 2321.76  115.77 2336.74  114.82 2396.08  122.89
 2460.06  126.78 2489.59  127.54 2519.12  125.86 2618.89  125.22 2976.34  124.76
#Mann= 6 ,-1 , 0
       0     .12       0 1811.58     .07       0 1857.35     .04       0
 2032.23     .07       0 2064.88     .12       0 2618.89     .07       0
#XS Ineff= 1 ,-1
 2152.03 2489.59   114.5
Permanent Ineff=
       F
Bank Sta=1857.35,2032.23
XS Rating Curve= 0 ,0
Exp/Cntr=0.3,0.1

Type RM Length L Ch R = 1 ,35242.97,474.73,470.04,459.47
XS GIS Cut Line= 5
3019733.0906358113868205.60988713018996.1114667213867988.5958854
3017785.1739279613867827.13754693017144.54889688 13867759.429349
 3016620.677569313867719.0646003
#Sta/Elev= 30
       0   122.3  773.25  122.75 1222.02  117.01 1566.08  115.35 1690.74  117.11
 1785.48  114.59 1810.41   115.9    1960  116.93 1984.53  115.78 1999.04  114.49
 2028.84  107.01 2069.39  105.09 2076.45    99.5  2081.5   99.03 2086.45   99.58
 2089.97  102.32  2183.3  107.77 2197.87  112.04 2199.66 116.007 2209.65  114.56
 2238.86  117.66 2387.68  117.31 2428.91  119.34 2434.37  116.72 2822.48   121.3
 2971.18  120.91 3020.75  122.92 3085.19   121.6 3134.75  125.83 3159.54     125
#Mann= 4 ,-1 , 0
       0     .12       0    1960     .07       0 1984.53     .04       0
 2199.66     .12       0
Bank Sta=1984.53,2199.66
XS Rating Curve= 0 ,0
Exp/Cntr=0.3,0.1

Type RM Length L Ch R = 1 ,34772.93,125.18,112.03,185.84
Node Name=J
XS GIS Cut Line= 6
3019846.9867335313867590.40508083018915.5847249513867447.9460481
3017672.9300580313867355.64997293017517.4398834413867355.6499729
3016872.4900578613867349.71002413016307.5426969413867317.5421094
#Sta/Elev= 30
       0  119.63  663.05  120.84 1006.99  117.12 1360.68  114.97 1689.47  114.66
 1749.25  116.17 1799.06  114.44 2047.35  115.37 2081.87  115.78 2096.38  114.49
 2100.62  112.57 2126.18  107.01 2166.73  105.09 2173.79    99.5 2178.84   99.03
 2183.79   99.58 2187.31  102.32 2242.65  106.47 2280.64  107.77 2295.21  112.04
    2297 116.007 2314.04  117.84 2360.04  118.12 2466.04  116.17 2613.79  118.51
 2813.78  118.46 2908.77  120.58 3152.57  119.91 3485.13  125.03 3554.62  124.49
#Mann= 5 ,-1 , 0
       0     .12       0 2047.35     .07       0 2081.87     .04       0
    2297     .12       0 3485.13     .07       0
Bank Sta=2081.87,2297
XS Rating Curve= 0 ,0
Exp/Cntr=0.3,0.1

Type RM Length L Ch R = 1 ,34660.91,1083.02,1112.06,1140.83
XS GIS Cut Line= 5
3019848.5418484713867459.95028913018977.0140639713867317.5890253
3017765.2087448113867251.61671633016897.1530662213867213.4222389
3016338.1253128813867175.2277615
#Sta/Elev= 30
       0  118.66   59.87  120.29  588.72  120.52 1447.43  114.05  1732.1  115.04
 1802.02  105.62  1906.9  115.58 1971.82  116.21  2081.7  115.78 2096.21  114.49
 2126.01  107.01 2166.56  105.09 2173.62    99.5 2178.67   99.03 2183.62   99.58
 2187.14  102.32 2280.47  107.77 2304.76  114.62  2391.3  122.66 2451.23  125.22
 2496.17  123.69 2541.11  125.62 2725.88  125.31 2765.83  123.32 2825.75     124
 2845.72  121.94 2960.58  120.41 3387.06  122.77  3406.9  121.54 3525.91  124.22
#Mann= 5 ,-1 , 0
       0     .12       0 1971.82     .07       0  2081.7     .04       0
 2304.76     .12       0 2725.88     .07       0
#XS Ineff= 2 ,-1
  1732.1  1906.9  115.04 2655.97 3525.91   125.9
Permanent Ineff=
       T       F
Bank Sta=2081.7,2304.76
XS Rating Curve= 0 ,0
Exp/Cntr=0.3,0.1

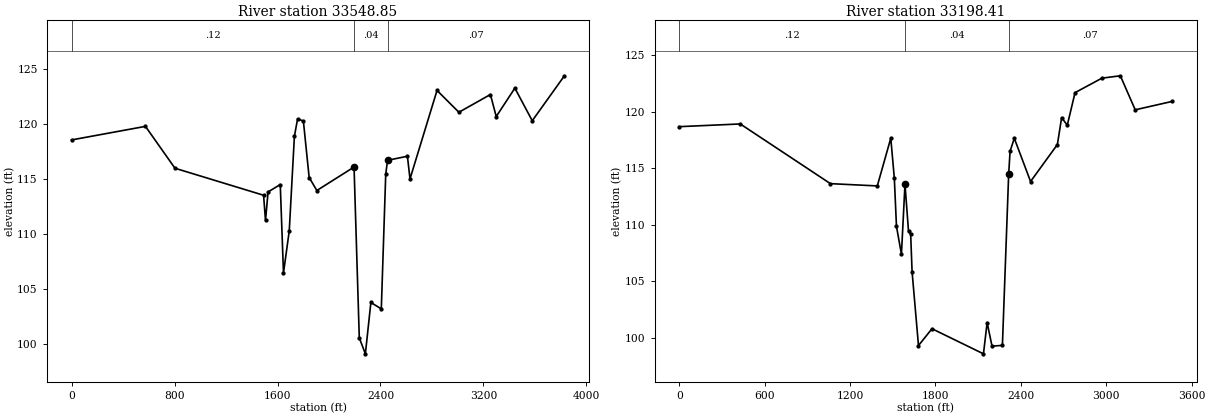
Type RM Length L Ch R = 1 ,33548.85,570.14,350.44,418.38
Node Name=I
XS GIS Cut Line= 5
3019852.1911194513867116.82531933017882.0300335313866219.0000152
3017715.8200641113866122.4900376 3017603.230066213866063.5200112
3016360.7801232813865548.4898733
#Sta/Elev= 30
       0  118.52   573.7  119.75  803.18  115.95 1491.62   113.5 1506.58  111.21
 1526.54   113.8 1621.32  114.47 1646.27  106.44 1691.17  110.27 1731.08  118.84
 1756.02  120.43 1800.92  120.23 1845.82  115.11 1905.68  113.93 2194.66  116.06
 2235.41  100.56 2282.69   99.11 2325.34  103.77 2406.43  103.19 2440.85  115.41
 2455.06  116.67 2609.39  117.04 2629.39  114.98 2839.39  123.01 3009.38  121.03
 3254.38  122.64 3299.38  120.64 3444.38  123.22 3579.38  120.26 3829.38  124.34
#Mann= 3 ,-1 , 0
       0     .12       0 2194.66     .04       0 2455.06     .07       0
#XS Ineff= 1 ,-1
       0    1766   113.7
Permanent Ineff=
       F
Bank Sta=2194.66,2455.06
XS Rating Curve= 0 ,0
Exp/Cntr=0.3,0.1

Type RM Length L Ch R = 1 ,33198.41,340.76,337.44,334.17
XS GIS Cut Line= 6
3019799.4271173613866925.01205463018362.6895052813866111.7423557
3018028.3361713613865932.55701853017840.6761136113865739.5370633
3017465.9869023613865421.87037593016836.9215594413865187.8626418
#Sta/Elev= 30
       0  118.68  428.95  118.92 1062.39  113.64 1391.58  113.44 1486.35  117.66
 1511.29  114.11 1526.25  109.87 1561.17   107.4  1586.1  113.59 1611.04  109.41
 1626.01  109.17 1635.98  105.85 1680.89   99.32 1775.73  100.81  2137.4   98.59
 2163.08  101.35 2197.51   99.27 2270.46   99.34 2314.43  114.45 2324.36  116.51
 2354.13  117.65 2468.26  113.83 2656.81   117.1 2686.58  119.48 2726.28  118.81
 2780.86  121.69 2969.76  122.97 3099.03  123.18 3203.43  120.17 3461.96  120.91
#Mann= 3 ,-1 , 0
       0     .12       0  1586.1     .04       0 2314.43     .07       0
#XS Ineff= 1 ,-1
 1486.35  1586.1  113.59
Permanent Ineff=
       F
Bank Sta=1586.1,2314.43
XS Rating Curve= 0 ,0
Exp/Cntr=0.3,0.1