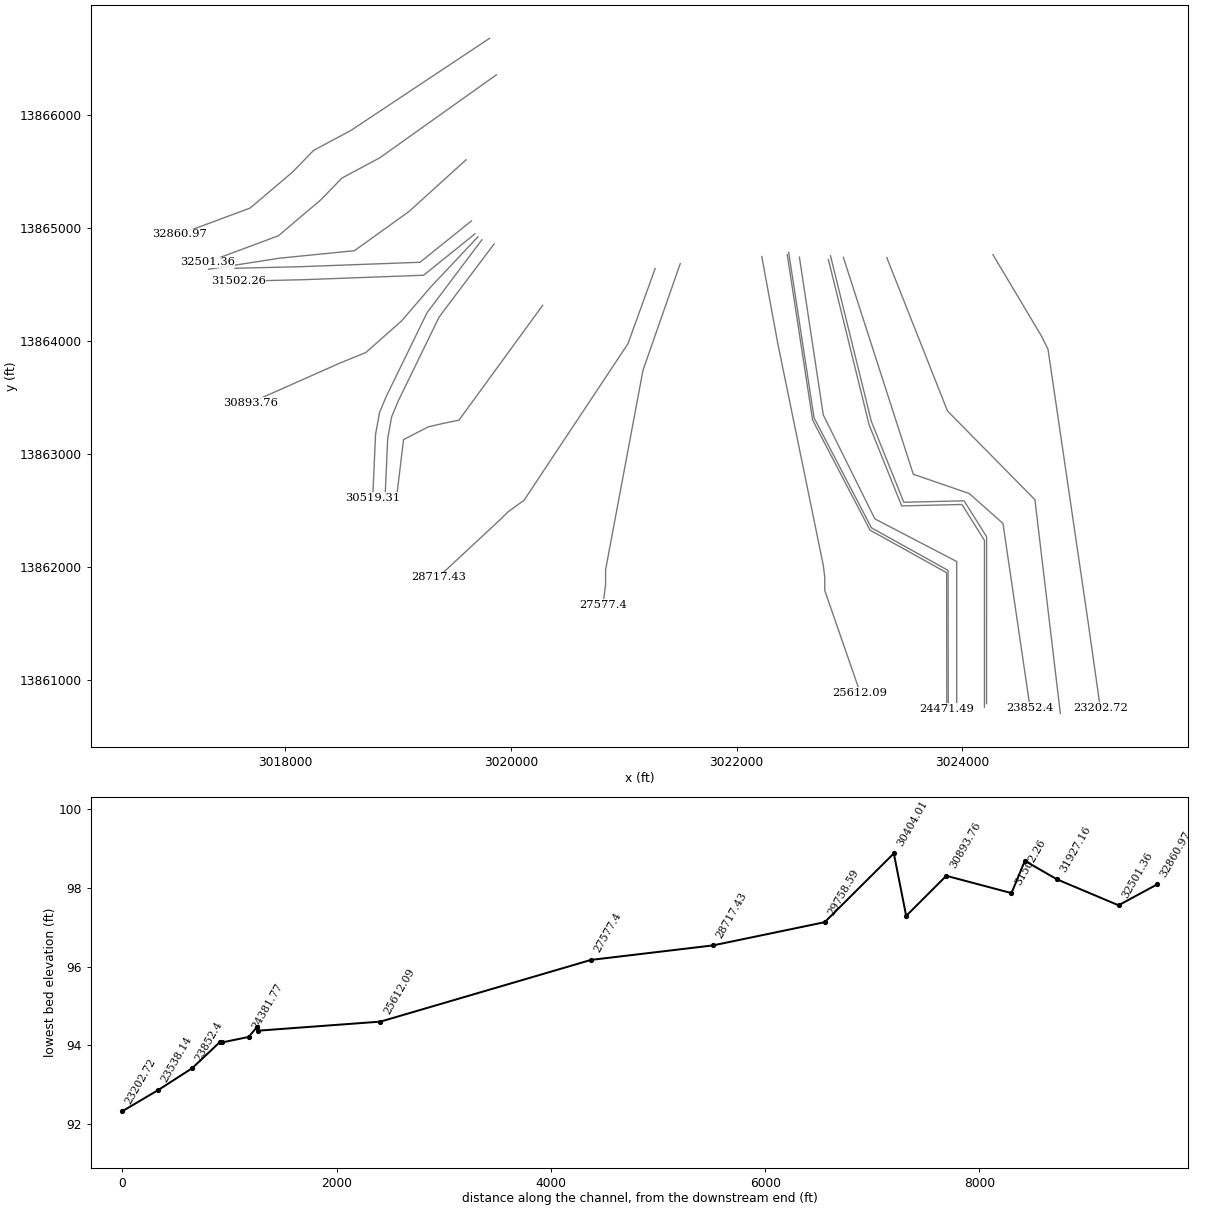
HEC-RAS study U102-00-00.prj: U102-00-00 (Update)

--- U102-00-00.g01 (geometry) --- (continued)

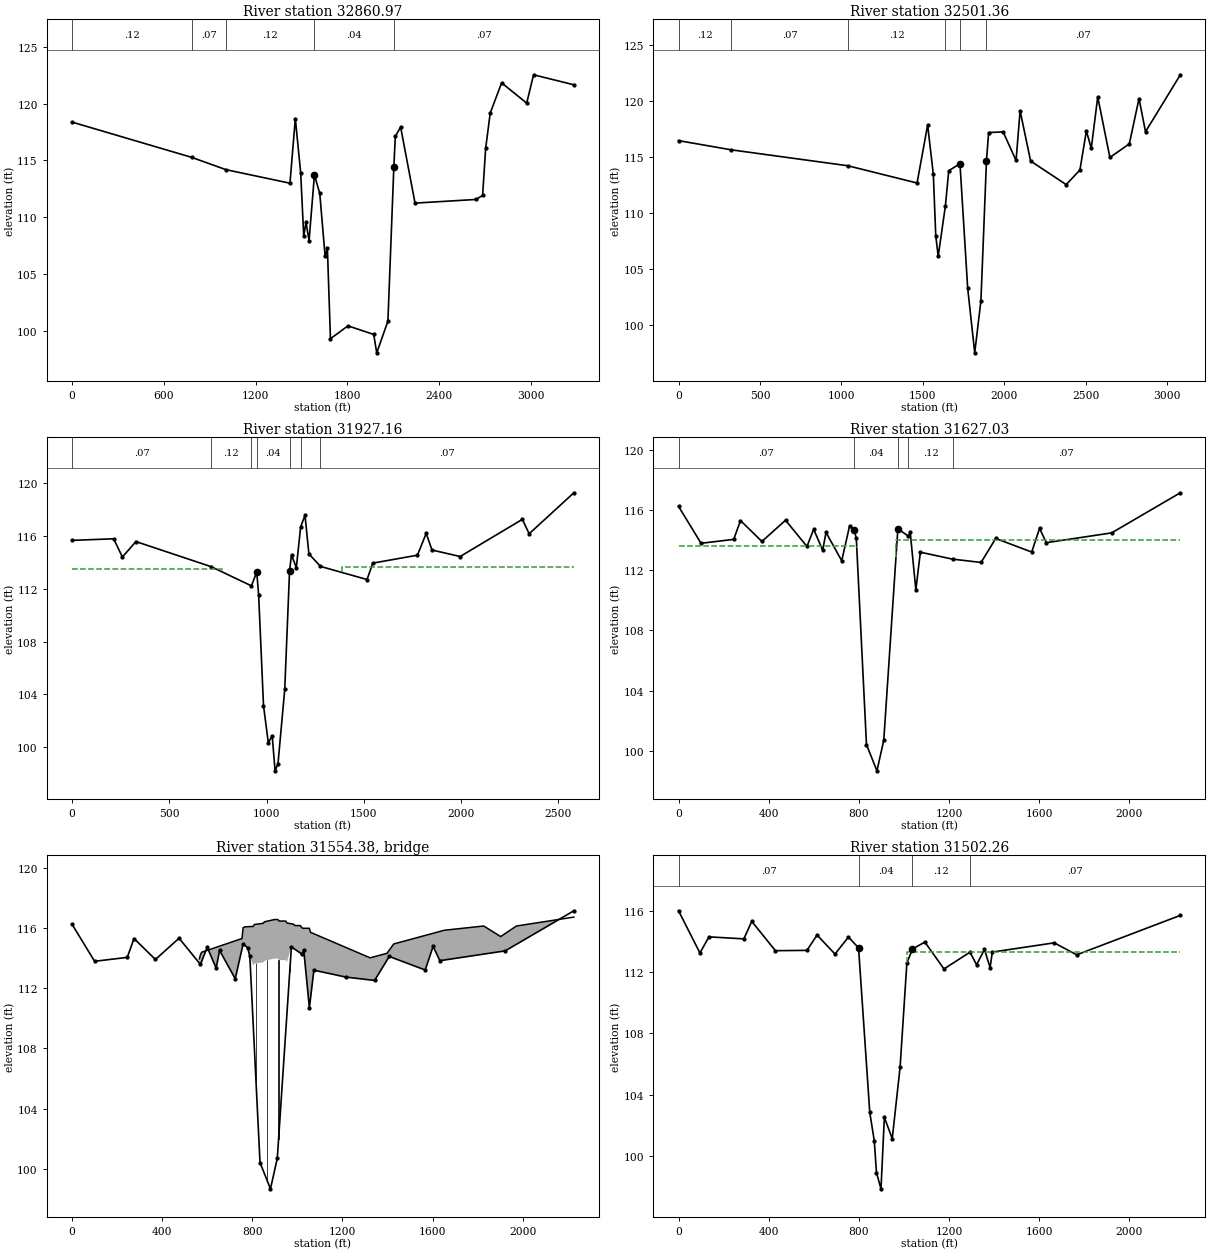
Type RM Length L Ch R = 1 ,32860.97,444.21,359.61,350.64
Node Name=H
XS GIS Cut Line= 6
3019811.6938251113866679.68052433018587.7205512813865866.2536734
3018253.3672173613865687.06833633018065.7071596113865494.0483811
3017691.0179483613865176.38169363017061.9526054413864942.3739595
#Sta/Elev= 30
       0  118.37  782.41  115.27 1006.22  114.19 1424.63     113 1459.62  118.68
 1494.57  113.92 1514.54  108.37 1529.51  109.55 1549.48  107.96 1584.42  113.71
 1619.36  112.11  1654.3  106.58 1669.27  107.29 1689.24   99.33 1804.04  100.46
 1971.92   99.71 1991.87   98.09 2064.88  100.87 2103.68  114.43 2113.37  117.11
 2147.99  117.94 2242.27  111.25 2639.29  111.57 2684.03  111.92 2703.92  116.06
 2733.75  119.16 2808.32  121.82 2972.39  120.04 3017.13  122.53 3280.63  121.65
#Mann= 5 ,-1 , 0
       0     .12       0  782.41     .07       0 1006.22     .12       0
 1584.42     .04       0 2103.68     .07       0
#XS Ineff= 2 ,-1
       0 1584.42   113.6 2147.99 2876.78   113.6
Permanent Ineff=
       F       F
Bank Sta=1584.42,2103.68
XS Rating Curve= 0 ,0
Exp/Cntr=0.3,0.1

Type RM Length L Ch R = 1 ,32501.36,588.24,574.2,557.43
Node Name=G
XS GIS Cut Line= 6
3019873.0076788713866357.01647143018838.3233965313865620.7653193
3018503.9700626113865441.57998213018316.3100048613865248.5600269
3017941.6207936113864930.89333943017312.5554506913864696.8856054
#Sta/Elev= 30
       0  116.48  323.17  115.66 1039.23  114.24 1464.56   112.7 1529.44  117.87
 1564.38  113.48 1579.36  107.98 1594.33  106.18 1638.64  110.68 1659.07   113.8
 1727.93  114.42  1775.4  103.31 1818.52   97.56  1856.6  102.21 1890.68  114.68
 1903.95   117.2 1992.93  117.26 2072.32  114.71 2097.13  119.14 2161.63  114.66
 2379.96  112.56 2464.42  113.86 2504.19  117.35 2534.02  115.78  2573.8  120.38
 2648.37  114.98 2767.69  116.19 2827.35  120.23 2867.13  117.27 3080.91  122.35
#Mann= 6 ,-1 , 0
       0     .12       0  323.17     .07       0 1039.23     .12       0
 1638.64     .07       0 1727.93     .04       0 1890.68     .07       0
#XS Ineff= 2 ,-1
       0 1727.93   113.5 2097.13 3080.91   113.5
Permanent Ineff=
       F       F
Bank Sta=1727.93,1890.68
XS Rating Curve= 0 ,0
Exp/Cntr=0.3,0.1

Type RM Length L Ch R = 1 ,31927.16,323.5,300.13,236.24
XS GIS Cut Line= 5
3019603.7765900213865603.65216453019098.8501064513865146.0900875
3018614.9399850213864798.55010023017955.0499006113864732.5600747
3017322.96356636 13864634.435599
#Sta/Elev= 30
       0  115.65  213.87  115.77  258.64  114.39  328.27  115.56  713.58  113.67
  922.25  112.21  949.51  113.26  959.44  111.49  984.26  103.16 1009.09  100.33
 1028.95  100.88 1043.84   98.22 1058.73   98.75 1093.49  104.39 1118.31  113.36
 1128.24  114.55 1153.07  113.59 1175.26  116.67 1197.75  117.55 1217.61  114.63
 1277.32  113.68 1516.53  112.69 1546.45  113.93 1775.82  114.53 1820.69  116.18
 1850.61  114.92 1995.33  114.43 2315.16  117.24 2350.14  116.15 2580.02  119.25
#Mann= 7 ,-1 , 0
       0     .07       0  713.58     .12       0  922.25     .07       0
  949.51     .04       0 1118.31     .07       0 1175.26     .12       0
 1277.32     .07       0
#XS Ineff= 2 ,-1
       0  770.77  113.52  1386.9 2580.02  113.61
Permanent Ineff=
       F       F
Bank Sta=949.51,1118.31
XS Rating Curve= 0 ,0
Exp/Cntr=0.5,0.3

Type RM Length L Ch R = 1 ,31627.03,116.56,124.77,184.79
BEGIN DESCRIPTION:
Upstream Section (CLAY ROAD)
END DESCRIPTION:
XS GIS Cut Line= 5
3019651.7886331113865062.80941423019196.0808831213864696.1070636
3018887.6592558613864684.67368753018129.4028983613864656.5651479
3017554.7859373513864642.8840729
#Sta/Elev= 30
       0  116.23   99.99  113.78  244.97  114.04  274.97  115.29  369.95   113.9
  474.94  115.31  569.93  113.57  599.86  114.71  639.69  113.32  654.62   114.5
  724.31  112.62  759.16  114.93  779.07  114.68  789.02  114.11  834.16  100.43
   880.6   98.69   910.9  100.72  973.43  114.74 1020.46  114.25 1028.34   114.5
  1053.3  110.69 1073.27  113.19 1215.97  112.73 1342.84  112.51 1407.73   114.1
 1567.48   113.2 1602.42  114.77 1632.37  113.82 1922.24  114.47 2227.12  117.13
#Mann= 5 ,-1 , 0
       0     .07       0  779.07     .04       0  973.43     .07       0
 1020.46     .12       0 1215.97     .07       0
#XS Ineff= 2 ,-1
       0  791.07  113.61   965.2 2227.12  114.01
Permanent Ineff=
       F       F
Bank Sta=779.07,973.43
XS Rating Curve= 0 ,0
Exp/Cntr=0.5,0.3

Type RM Length L Ch R = 3 ,31554.38,,,
BEGIN DESCRIPTION:
CLAY ROAD
END DESCRIPTION:
Node Name=CLAY ROAD
Bridge Culvert--1,0,-1,-1, 0
Deck Dist Width WeirC Skew NumUp NumDn MinLoCord MaxHiCord MaxSubmerge Is_Ogee
38,66,2.6,0, 31, 31, , , 0.98, 0, 0,0,,
  564.93  569.93  574.93  754.18  759.16  764.13  769.11  803.96  808.94  848.76
  853.74  898.55  913.53  918.52  948.47  953.47  983.42  988.41 1013.37 1018.36
 1023.35  1053.3  1058.3 1322.87 1397.75  1427.7 1652.34 1827.28 1902.25 1972.22
 2227.12
  113.94  114.22  114.38  115.29  116.01  116.04  116.07  116.09  116.22   116.3
   116.4  116.55  116.55  116.45  116.45  116.32  116.24  116.15  116.15  116.03
  115.97  115.97   115.7  114.01  114.31  114.93  115.84  116.12  115.42  116.12
  116.71
       0       0       0       0       0       0  113.48   113.5  113.63  113.71
  113.81  113.96  113.96  113.86  113.86  113.73  113.65  113.56  113.56       0
       0       0       0       0       0       0       0       0       0       0
       0
  564.93  569.93  574.93  754.18  759.16  764.13  769.11  803.96  808.94  848.76
  853.74  898.55  913.53  918.52  948.47  953.47  983.42  988.41 1013.37 1018.36
 1023.35  1053.3  1058.3 1322.87 1397.75  1427.7 1652.34 1827.28 1902.25 1972.22
 2227.12
  113.94  114.22  114.38  115.29  116.01  116.04  116.07  116.09  116.22   116.3
   116.4  116.55  116.55  116.45  116.45  116.32  116.24  116.15  116.15  116.03
  115.97  115.97   115.7  114.01  114.31  114.93  115.84  116.12  115.42  116.12
  116.71
       0       0       0       0       0       0  113.39  113.41  113.54  113.62
  113.72  113.87  113.87  113.77  113.77  113.64  113.56  113.47  113.47       0
       0       0       0       0       0       0       0       0       0       0
       0
Pier Skew, UpSta & Num, DnSta & Num=  ,816.4, 2 ,816.4, 2 , 0 , 0 , 0 ,,
     1.4     1.4
      95   114.8
     1.4     1.4
      95   114.8
Pier Skew, UpSta & Num, DnSta & Num=  ,866.5, 2 ,866.5, 2 , 0 , 0 , 0 ,,
     1.4     1.4
      95   114.8
     1.4     1.4
      95   114.8
Pier Skew, UpSta & Num, DnSta & Num=  ,916.6, 2 ,916.6, 2 , 0 , 0 , 0 ,,
     1.4     1.4
      95   114.8
     1.4     1.4
      95   114.8
Pier Skew, UpSta & Num, DnSta & Num=  ,965.9, 2 ,966.9, 2 , 0 , 0 , 0 ,,
     1.4     1.4
      95   114.8
     1.4     1.4
      95   114.8
BR Coef=-1 , 1 , 1 ,0.9, 0 ,,,0.8,-1,1.2,0,
WSPro=,,,, 1 ,,,, 0 ,,,, 0 ,,,,-1 ,-1 ,-1 , 0 , 0 , 0 , 0 , 0
BC Design=,, 0 ,, 0 ,,,,,,
BC Use User HTab Curves=0
BC User HTab FreeFlow(D)= 0

Type RM Length L Ch R = 1 ,31502.26,529.45,608.5,684.36
BEGIN DESCRIPTION:
Downstream Section (CLAY ROAD)
END DESCRIPTION:
Node Name=F
XS GIS Cut Line= 5
3019683.0159328613864947.79159963019227.30818287 13864581.089249
3018918.8865556113864569.65587293018160.6301981113864541.5473334
 3017586.013237113864527.8662584
#Sta/Elev= 30
       0  115.99   94.99  113.24  134.98  114.29  289.96  114.16  324.96   115.3
  429.95  113.39  569.93  113.41   614.8  114.41  694.44  113.17  754.18  114.28
  798.98  113.57  848.76  102.85  868.67  101.01  878.63   98.92  898.55   97.87
  913.53  102.53  948.47  101.14  983.42  105.81 1013.37  112.58 1038.33   113.5
 1093.24  113.95  1178.1   112.2 1293.48  113.29 1322.87  112.47 1357.81  113.47
 1382.77  112.29 1392.76   113.3 1667.34   113.9  1767.3  113.12 2227.12  115.69
#Mann= 4 ,-1 , 0
       0     .07       0  798.98     .04       0 1038.33     .12       0
 1293.48     .07       0
#XS Ineff= 2 ,-1
       0  799.87   113.3 1013.37 2227.12   113.3
Permanent Ineff=
       F       F
Bank Sta=798.98,1038.33
XS Rating Curve= 0 ,0
Exp/Cntr=0.5,0.3

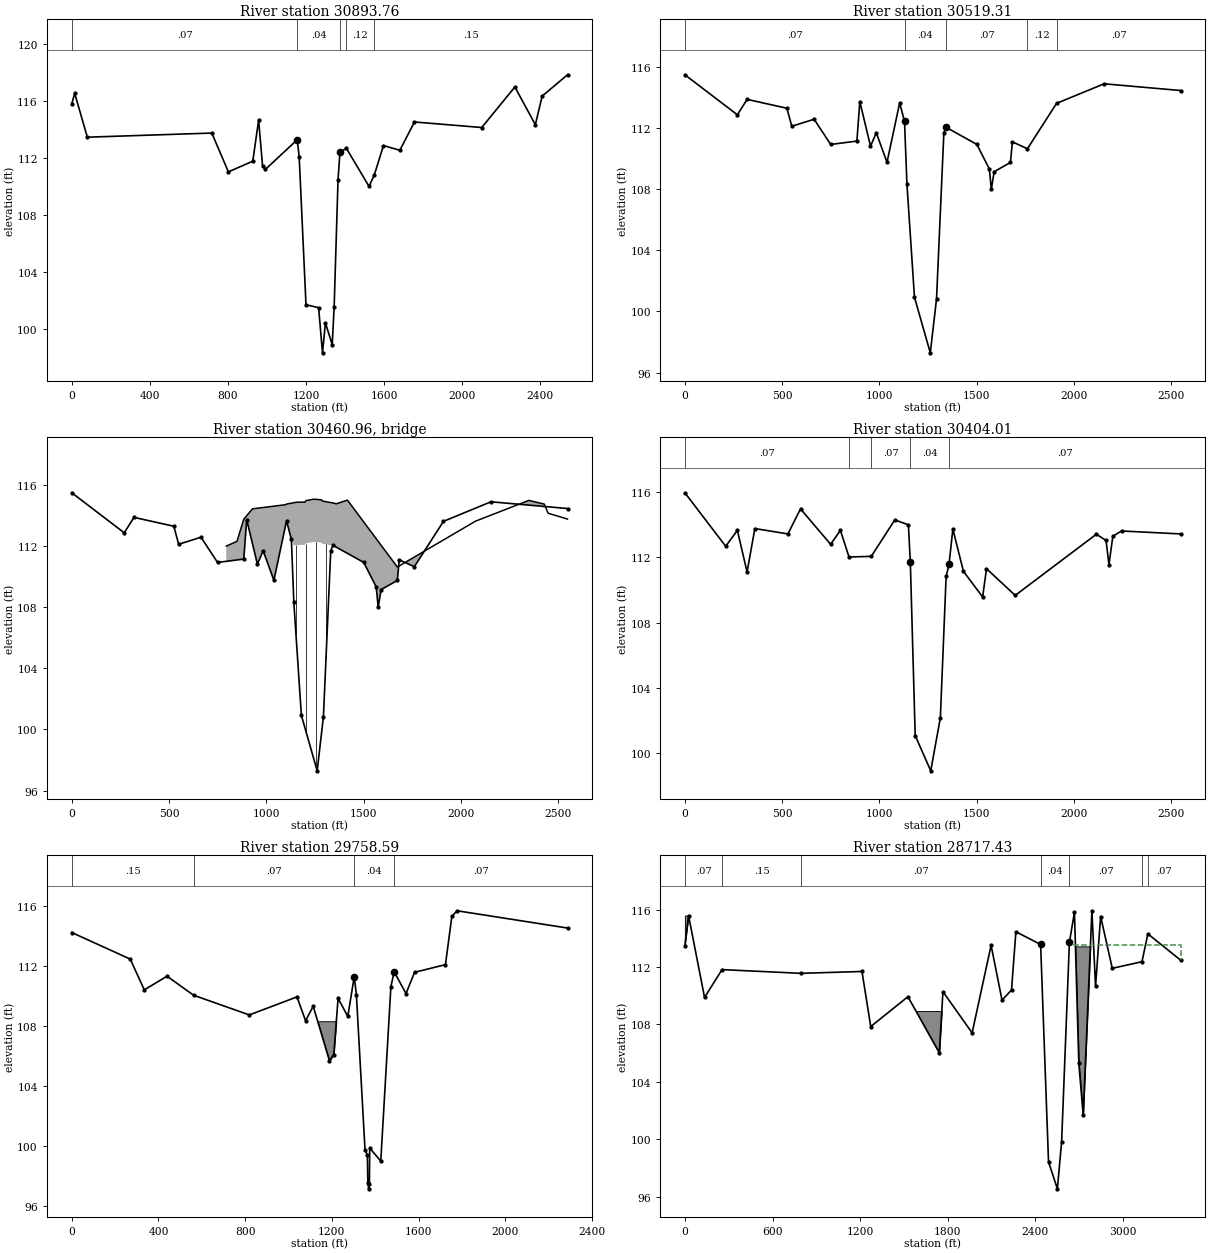
Type RM Length L Ch R = 1 ,30893.76,233.07,374.45,310.2
XS GIS Cut Line= 6
3019708.9856971913864921.31593083019295.9100797813864482.6701545
3019031.8098861913864175.88992823018716.1199007813863896.7100403
3018482.7801443613863801.41987663017697.6639324413863453.0888803
#Sta/Elev= 30
       0  115.82   14.94  116.57   79.67  113.48  717.47  113.77  802.43  111.04
  927.37  111.79  957.35  114.68  977.34  111.48  992.34  111.22 1155.21   113.3
 1165.16  112.09 1199.99  101.69 1264.66  101.49 1284.57   98.31 1299.49  100.42
 1334.32   98.89 1344.27  101.54 1364.17  110.49 1374.12  112.43 1407.28  112.69
 1522.75  110.02 1549.93  110.82 1596.88  112.89  1680.9  112.56  1755.8  114.55
 2100.37  114.16 2270.15  117.01 2375.02  114.36 2409.98  116.37 2539.81  117.87
#Mann= 5 ,-1 , 0
       0     .07       0 1155.21     .04       0 1374.12     .07       0
 1407.28     .12       0 1549.93     .15       0
#XS Ineff= 2 ,-1
       0  957.35   113.3 1413.92 2539.81   111.5
Permanent Ineff=
       F       F
Bank Sta=1155.21,1374.12
XS Rating Curve= 0 ,0
Exp/Cntr=0.5,0.3

Type RM Length L Ch R = 1 ,30519.31,113.09,115.3,114.65
BEGIN DESCRIPTION:
Upstream Section (BARKER CYPRESS)
END DESCRIPTION:
XS GIS Cut Line= 6
3019744.3744059513864895.33107463019257.9442764413864248.8448348
3018894.4532055313863502.81745543018836.6570612813863362.8817117
3018802.0751094413863171.5189054 3018776.782837213862609.7644515
#Sta/Elev= 30
       0  115.49  269.68  112.87  319.62  113.88  524.38   113.3  549.35  112.12
  664.22  112.58  749.12  110.93  883.96  111.15  898.95  113.74  953.89  110.82
  983.85  111.69 1038.79  109.76 1103.72  113.65 1128.69  112.44 1141.17  108.34
 1179.94  100.93 1261.21   97.29 1293.25  100.82 1330.98   111.7 1342.58  112.05
 1500.66  110.93 1564.88  109.32 1574.76  107.99 1589.58  109.15 1673.17  109.75
 1682.93   111.1  1760.5  110.65 1910.22  113.62 2154.46   114.9 2547.74  114.46
#Mann= 5 ,-1 , 0
       0     .07       0 1128.69     .04       0 1342.58     .07       0
  1760.5     .12       0 1910.22     .07       0
#XS Ineff= 2 ,-1
       0 1108.72  111.28 1342.58 2547.74  110.15
Permanent Ineff=
       F       F
Bank Sta=1128.69,1342.58
XS Rating Curve= 0 ,0
Exp/Cntr=0.5,0.3

Type RM Length L Ch R = 3 ,30460.96,,,
BEGIN DESCRIPTION:
BARKER CYPRESS
END DESCRIPTION:
Node Name=BARKER CYPRESS
Bridge Culvert--1,0,-1,-1, 0
Deck Dist Width WeirC Skew NumUp NumDn MinLoCord MaxHiCord MaxSubmerge Is_Ogee
8,94,2.6,0, 21, 21, , , 0.98, 0, 0,0,,
  794.07     849  883.96  928.92 1098.73 1103.72 1153.67 1198.62 1203.61 1243.57
  1283.3 1288.24 1352.46  1357.4 1416.68 1673.17 2074.64 2348.77 2428.36 2448.26
 2547.74
     112  112.31  113.76  114.44  114.71  114.75  114.87  114.88  114.98  115.07
  115.03  114.95   114.8  114.76  115.01  110.63  113.63  114.99  114.75  114.15
  113.77
       0       0       0       0       0  111.95  112.07  112.08  112.18  112.27
  112.23  112.15     112       0       0       0       0       0       0       0
       0
  794.07     849  883.96  928.92 1098.73 1103.72 1153.67 1198.62 1203.61 1243.57
  1283.3 1288.24 1352.46  1357.4 1416.68 1673.17 2074.64 2348.77 2428.36 2448.26
 2547.74
     112  112.31  113.76  114.44  114.71  114.75  114.87  114.88  114.98  115.07
  115.03  114.95   114.8  114.76  115.01  110.63  113.63  114.99  114.75  114.15
  113.77
       0       0       0       0       0  111.86  111.98  111.99  112.09  112.18
  112.14  112.06  111.91       0       0       0       0       0       0       0
       0
Pier Skew, UpSta & Num, DnSta & Num=  ,1152.01, 2 ,1152.01, 2 , 0 , 0 , 0 ,,
     1.4     1.4
      95  113.25
     1.4     1.4
      95  113.25
Pier Skew, UpSta & Num, DnSta & Num=  ,1202.71, 2 ,1202.71, 2 , 0 , 0 , 0 ,,
     1.4     1.4
      95  113.25
     1.4     1.4
      95  113.25
Pier Skew, UpSta & Num, DnSta & Num=  ,1255.11, 2 ,1255.11, 2 , 0 , 0 , 0 ,,
     1.4     1.4
      95  113.25
     1.4     1.4
      95  113.25
Pier Skew, UpSta & Num, DnSta & Num=  ,1306.41, 2 ,1306.41, 2 , 0 , 0 , 0 ,,
     1.4     1.4
      95  113.25
     1.4     1.4
      95  113.25
Abutment Skew #Up #Dn= , 2 , 2
 1102.61 1104.21
  111.95  111.35
 1102.61 1104.21
  111.86  111.26
BR Coef=-1 , 1 , 1 ,0.9, 0 ,,,0.8,-1,1.2,0,
WSPro=,,,, 1 ,,,, 0 ,,,, 0 ,,,,-1 ,-1 ,-1 , 0 , 0 , 0 , 0 , 0
BC Design=,, 0 ,, 0 ,,,,,,
BC Use User HTab Curves=0
BC User HTab FreeFlow(D)= 0

Type RM Length L Ch R = 1 ,30404.01,646.12,645.42,551.5
BEGIN DESCRIPTION:
Downstream Section (BARKER CYPRESS)
END DESCRIPTION:
XS GIS Cut Line= 6
 3019851.957852213864858.14676583019365.5277226913864211.6605259
3019002.0366517813863465.63314663018944.2405075313863325.6974028
3018909.6585556913863134.33459663018884.3662834513862572.5801427
#Sta/Elev= 30
       0  115.98  209.75  112.69  269.68  113.67  319.62  111.11  359.58  113.78
  529.38  113.45   594.3  114.99  749.12  112.81  799.06  113.67  843.66  112.03
  957.85  112.07 1078.75  114.31 1148.67  114.01 1158.66   111.7 1183.63  101.05
 1263.54   98.88 1312.94  102.15 1342.58  110.84  1357.4  111.57 1377.16  113.75
  1431.5  111.15  1530.3  109.57 1550.06  111.31 1697.59  109.67 2114.55  113.43
 2164.43  113.05  2179.4  111.56 2199.35  113.31 2244.25  113.63 2547.74  113.45
#Mann= 5 ,-1 , 0
       0     .07       0  843.66     .15       0  957.85     .07       0
 1158.66     .04       0  1357.4     .07       0
#XS Ineff= 2 ,-1
       0 1158.66  111.28 1352.46 2547.74  109.97
Permanent Ineff=
       F       F
Bank Sta=1158.66,1357.4
XS Rating Curve= 0 ,0
Exp/Cntr=0.5,0.3

Type RM Length L Ch R = 1 ,29758.59,865.22,1041.17,1104.94
XS GIS Cut Line= 6
3020281.9665066213864314.19476973019540.6999445313863296.9999537
 3019409.500075713863270.75984873019268.5282447813863237.9298619
3019050.1097183713863125.18533673018989.5163356113862624.7037261
#Sta/Elev= 30
       0  114.21  269.71  112.44  334.64  110.39  439.52   111.3  562.18  110.03
  819.11  108.72 1038.87  109.92 1078.83  108.33 1113.79   109.3 1188.71  105.67
 1208.69  106.08 1228.67  109.82  1273.5  108.62 1303.23  111.28 1313.15  110.06
  1352.9   99.73 1363.78   99.39 1365.89   97.54 1369.98   97.13  1373.2   97.48
 1374.58   99.85 1425.57   98.98 1472.29   110.6 1487.27   111.6 1542.09  110.14
 1581.42  111.56 1723.99  112.07 1753.48  115.29 1778.06  115.66 2287.11  114.51
#Mann= 4 ,-1 , 0
       0     .15       0  562.18     .07       0 1303.23     .04       0
 1487.27     .07       0
#Block Obstruct= 1 ,-1
 1113.79 1238.66   108.3
Bank Sta=1303.23,1487.27
XS Rating Curve= 0 ,0
Exp/Cntr=0.3,0.1

Type RM Length L Ch R = 1 ,28717.43,699.79,1140.03,1182.09
XS GIS Cut Line= 6
3021278.6600512713864640.32010173021037.7599425313863974.3801606
3020117.9599448613862588.54008453019973.6400235313862483.5799926
3019908.0499316213862417.98005823019357.0198656913861906.3199923
#Sta/Elev= 30
       0   113.5   24.94  115.59  134.65  109.88   254.4  111.82  794.39  111.56
 1212.66  111.69  1272.6  107.85 1527.34  109.93 1742.12  106.02  1767.1  110.28
  1966.9  107.41 2096.76  113.51 2171.69  109.69 2236.62   110.4 2266.59  114.46
 2435.92  113.57 2490.07   98.42 2550.62   96.54 2579.78   99.82 2632.93  113.71
  2667.6  115.82 2697.48  105.29 2727.35  101.69 2787.11  115.92 2812.01  110.67
 2846.87  115.52 2926.54  111.91 3129.84  112.37 3170.19  114.31 3394.64  112.48
#Mann= 7 ,-1 , 0
       0     .07       0   254.4     .15       0  794.39     .07       0
 2435.92     .04       0 2632.93     .07       0 3129.84     .15       0
 3170.19     .07       0
#XS Ineff= 2 , 0
       0                 2657.64       0  113.54
Permanent Ineff=
       F       F
#Block Obstruct= 3 ,-1
       0   24.94  115.59 1527.34 1807.06  108.93 2657.64 2792.09  113.44
Bank Sta=2435.92,2632.93
XS Rating Curve= 0 ,0
Exp/Cntr=0.3,0.1

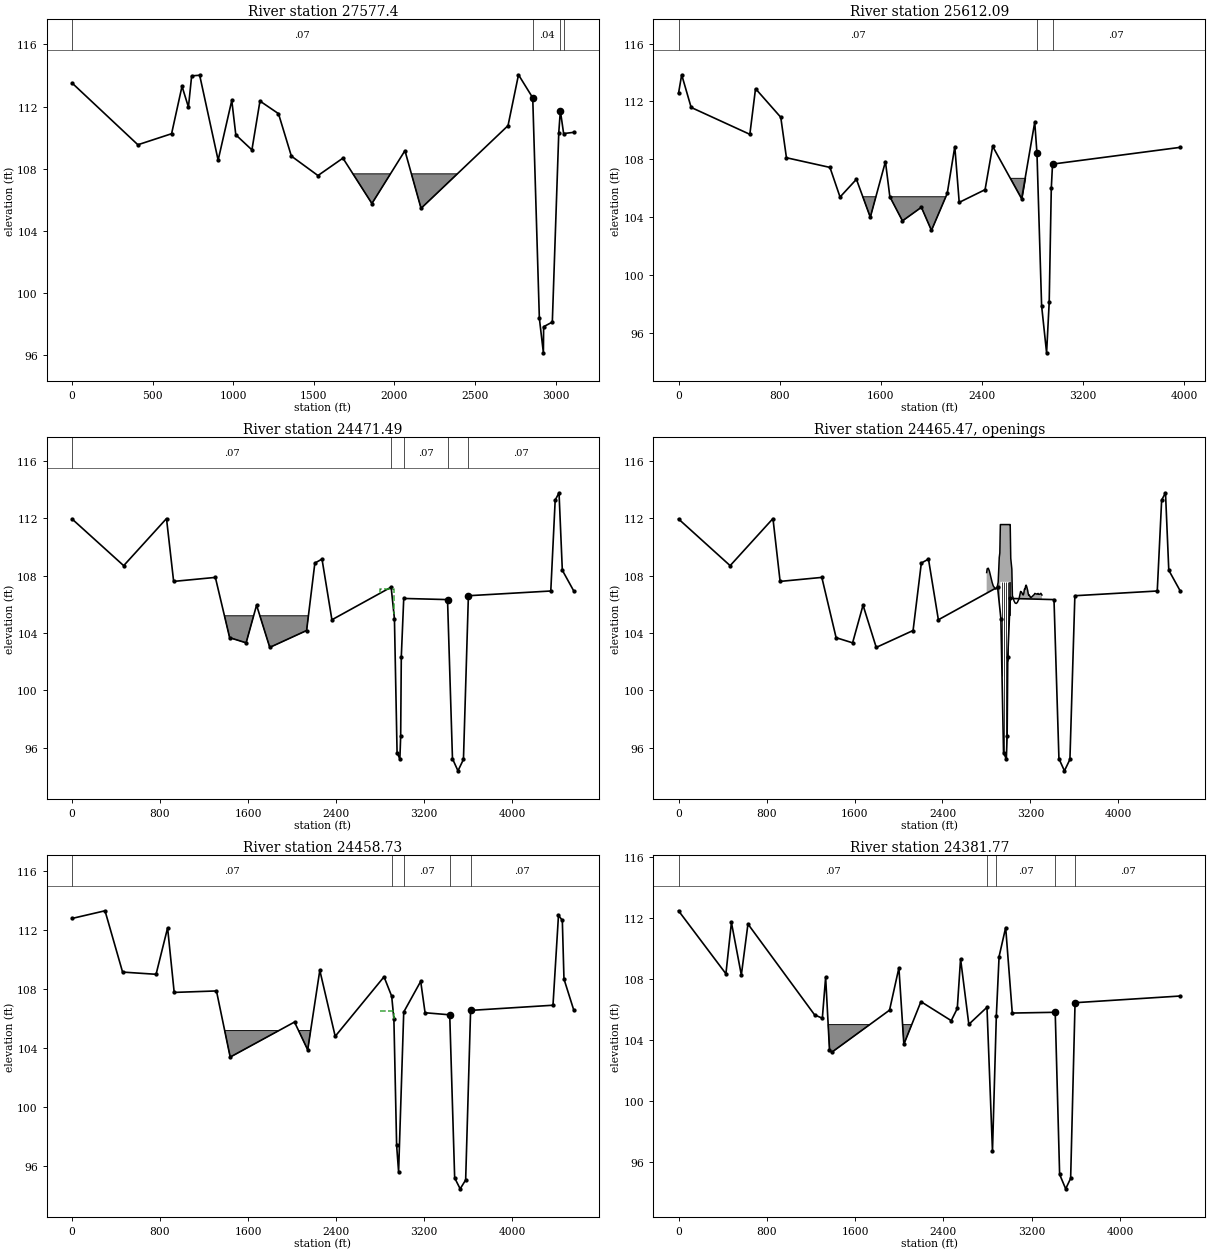
Type RM Length L Ch R = 1 ,27577.4 ,1847.02,1965.31,1958.22
Node Name=E
XS GIS Cut Line= 5
3021501.0398558713864684.36988233021170.9899910213863739.6798426
3020839.5300240213861971.91992673020839.5300240213861840.7200578
3020816.2400443613861659.9599207
#Sta/Elev= 30
       0  113.52  408.24  109.55  617.34  110.26  682.06  113.31  721.89  111.97
   741.8  113.98  791.59  114.02  906.09  108.56  990.73   112.4 1015.67  110.19
 1115.59  109.22 1165.55  112.36 1280.46  111.55  1360.4  108.82 1525.27  107.57
 1680.15  108.69    1860  105.77 2064.84  109.17 2164.76  105.46 2704.34  110.78
 2769.29  114.05 2857.58  112.57 2898.66    98.4  2923.7   96.17 2925.21   97.85
 2979.13   98.15 3019.13  110.33 3028.98  111.74 3049.28  110.27 3112.72  110.35
#Mann= 4 ,-1 , 0
       0     .07       0 2857.58     .04       0 3028.98     .07       0
 3049.28     .15       0
#Block Obstruct= 1 ,-1
 1635.18 2479.52  107.68
Bank Sta=2857.58,3028.98
XS Rating Curve= 0 ,0
Exp/Cntr=0.3,0.1

Type RM Length L Ch R = 1 ,25612.09,265.05,1140.6,1109.14
Node Name=D
XS GIS Cut Line= 6
3022223.0000261113864747.4901629 3022365.009912713863976.3801566
3022768.1101563613862011.28008423022781.2298807813861906.3199923
3022781.2298807813861788.25001843023094.6373904513860883.8532052
#Sta/Elev= 30
       0  112.56   24.97  113.84   99.88  111.58  564.34  109.72  609.28  112.88
  809.03   110.9  853.94   108.1 1198.26  107.43  1278.1  105.38 1407.84  106.61
 1517.62  103.98 1637.38  107.83 1672.32   105.4 1772.12  103.73 1921.82  104.67
 2001.66  103.07 2126.42  105.63  2186.3  108.87 2221.23  105.01 2425.82  105.89
  2485.7  108.89 2715.25  105.26 2818.95  110.56 2836.66   108.4 2873.31   97.86
 2912.77    94.6 2933.39    98.1 2949.96  105.98 2959.83  107.66 3971.11  108.82
#Mann= 3 ,-1 , 0
       0     .07       0 2836.66     .04       0 2959.83     .07       0
#Block Obstruct= 2 ,-1
 1407.84  2186.3   105.4  2485.7 2770.14  106.71
Bank Sta=2836.66,2959.83
XS Rating Curve= 0 ,0
Exp/Cntr=0.5,0.3

Type RM Length L Ch R = 1 ,24471.49,24.64,12.75,12.69
BEGIN DESCRIPTION:
Upstream Section (US GOLF CART BR)
END DESCRIPTION:
XS GIS Cut Line= 6
3022448.8539051113864764.05673093022673.2622489513863298.5140583
3023181.9679244513862323.34474883023517.1910072713862137.1328509
3023860.6827743613861946.32811433023862.20868994 13860742.742595
#Sta/Elev= 30
       0  111.96  469.25   108.7  858.62  111.99  923.52   107.6 1302.91  107.88
 1432.71  103.67 1582.61  103.31  1677.6  105.94 1797.59  102.99 2132.55  104.17
 2207.54  108.88 2272.54  109.16 2362.53  104.92 2901.23   107.2 2931.11  104.99
 2955.08   95.64 2980.38   95.19 2987.78   96.78 2993.48  102.34 3015.71  106.41
 3413.83  106.33 3458.78   95.22 3508.72   94.37 3558.66   95.17 3603.61   106.6
 4352.74  106.93 4392.69  113.28 4427.65  113.79 4457.62  108.38  4562.5  106.92
#Mann= 5 ,-1 , 0
       0     .07       0 2901.23     .06       0 3015.71     .07       0
 3413.83     .04       0 3603.61     .07       0
#XS Ineff= 2 ,-1
 2801.63 2926.13  107.08 3015.71    3200  106.06
Permanent Ineff=
       F       F
#Block Obstruct= 1 ,-1
 1302.91 2207.54   105.2
Bank Sta=3413.83,3603.61
XS Rating Curve= 0 ,0
Exp/Cntr=0.5,0.3

Type RM Length L Ch R = 4 ,24465.47,,,
BEGIN DESCRIPTION:
US GOLF CART BR
END DESCRIPTION:
Node Name=US GOLF CART BR
Bridge Culvert--1,0,-1,-1, 0
Deck Dist Width WeirC Skew NumUp NumDn MinLoCord MaxHiCord MaxSubmerge Is_Ogee
1,11,2.6,0, 60, 60, , , 0.98, 0, 0,0,,
 2801.63 2806.61 2816.57 2826.53 2851.43 2861.39 2881.31 2891.27 2896.25 2906.21
 2916.17 2921.15 2926.13 2931.11 2936.09 2941.07 2946.05 2951.03 2956.01 2975.92
 2980.89 2985.87 2990.84 2995.81 3005.76 3010.74 3015.71 3020.68 3025.66 3030.63
  3035.6 3050.53 3060.47 3070.42 3080.37 3095.29 3110.21 3120.16 3130.11 3135.08
 3140.05 3145.03    3150 3154.97 3159.95 3164.92 3174.87 3179.84 3184.82 3189.79
 3199.74 3204.71 3234.55 3239.53 3259.42 3269.37 3274.34 3284.29 3294.24 3304.19
  108.22  108.49  108.52  108.32  107.53  107.29  107.07  107.08  107.16  107.54
109.2737109.5766  111.57  111.57  111.57  111.57  111.57  111.57  111.57  111.57
  111.57  111.57  111.57  111.57  111.57  111.57  111.57 109.211108.8358108.4614
  106.61  106.24  106.09  106.06  106.13  106.37   106.9  106.84  106.67  106.66
   106.8  107.06  107.04  107.25  107.34  107.26  106.96  106.73  106.62  106.64
  106.48  106.47  106.69  106.76  106.71  106.76   106.7   106.7  106.77  106.65
       0       0       0       0       0       0       0       0       0       0
       0       0  107.57  107.57  107.57  107.57  107.57  107.57  107.57  107.57
  107.57  107.57  107.57  107.57  107.57  107.57  107.57       0       0       0
       0       0       0       0       0       0       0       0       0       0
       0       0       0       0       0       0       0       0       0       0
       0       0       0       0       0       0       0       0       0       0
 2801.63 2806.61 2816.57 2826.53 2851.43 2861.39 2881.31 2891.27 2896.25 2906.21
 2916.17 2921.15 2926.13 2931.11 2936.09 2941.07 2946.05 2951.03 2956.01 2975.92
 2980.89 2985.87 2990.84 2995.81 3005.76 3010.74 3015.71 3020.68 3025.66 3030.63
  3035.6 3050.53 3060.47 3070.42 3080.37 3095.29 3110.21 3120.16 3130.11 3135.08
 3140.05 3145.03    3150 3154.97 3159.95 3164.92 3174.87 3179.84 3184.82 3189.79
 3199.74 3204.71 3234.55 3239.53 3259.42 3269.37 3274.34 3284.29 3294.24 3304.19
  108.22  108.49  108.52  108.32  107.53  107.29  107.07  107.08  107.16  107.54
109.2737109.5766  111.57  111.57  111.57  111.57  111.57  111.57  111.57  111.57
  111.57  111.57  111.57  111.57  111.57  111.57  111.57 109.211108.8358108.4614
  106.61  106.24  106.09  106.06  106.13  106.37   106.9  106.84  106.67  106.66
   106.8  107.06  107.04  107.25  107.34  107.26  106.96  106.73  106.62  106.64
  106.48  106.47  106.69  106.76  106.71  106.76   106.7   106.7  106.77  106.65
       0       0       0       0       0       0       0       0       0       0
       0       0  107.57  107.57  107.57  107.57  107.57  107.57  107.57  107.57
  107.57  107.57  107.57  107.57  107.57  107.57  107.57       0       0       0
       0       0       0       0       0       0       0       0       0       0
       0       0       0       0       0       0       0       0       0       0
       0       0       0       0       0       0       0       0       0       0
Pier Skew, UpSta & Num, DnSta & Num=  ,2941.37, 2 ,2941.37, 2 , 0 , 0 , 0 ,,
       1       1
      95     109
       1       1
      95     109
Pier Skew, UpSta & Num, DnSta & Num=  ,2958.57, 2 ,2958.57, 2 , 0 , 0 , 0 ,,
       1       1
      95     109
       1       1
      95     109
Pier Skew, UpSta & Num, DnSta & Num=  ,2975.37, 2 ,2975.37, 2 , 0 , 0 , 0 ,,
       1       1
      95     109
       1       1
      95     109
Pier Skew, UpSta & Num, DnSta & Num=  ,2993.17, 2 ,2993.17, 2 , 0 , 0 , 0 ,,
       1       1
      95     109
       1       1
      95     109
Pier Skew, UpSta & Num, DnSta & Num=  ,3009.47, 2 ,3009.47, 2 , 0 , 0 , 0 ,,
       1       1
      95     109
       1       1
      95     109
BR Coef=-1 , 1 , 1 ,0.9, 0 ,,,0.8,-1,1.2,0,
WSPro=,,,, 1 ,,,, 0 ,,,, 0 ,,,,-1 ,-1 ,-1 , 0 , 0 , 0 , 0 , 0
BC Mult= 1 ,0,2800,0,2800
BC Mult= 3 ,2800,3200,2800,3200
BC Mult= 1 ,3200,4562.5,3200,4562.5
BC Design=,, 0 ,, 0 ,,,,,,
BC Use User HTab Curves=0
BC User HTab FreeFlow(D)= 0

Type RM Length L Ch R = 1 ,24458.73,100.47,76.97,76.2
BEGIN DESCRIPTION:
Downstream Section (US GOLF CART BR)
END DESCRIPTION:
XS GIS Cut Line= 6
3022461.5179217813864784.48976083022685.9262656113863318.9470883
3023194.6319411113862343.77777883023529.8550239513862157.5658809
3023873.3467910313861966.76114443023874.87270661 13860763.175625
#Sta/Elev= 30
       0  112.81  299.52  113.33  459.26  109.17  763.78  109.02  868.61  112.17
  928.51  107.79  1312.9  107.89  1437.7   103.4 2022.57  105.78 2142.55  103.89
 2252.54  109.29 2392.52  104.81 2836.49  108.85 2906.21  107.53 2926.13  105.98
 2951.03   97.41 2968.97   95.62 3015.71  106.46  3169.9  108.54 3209.69  106.41
 3433.81  106.27 3478.76    95.2  3528.7   94.46 3578.64   95.06 3623.59  106.57
 4372.72  106.92 4422.66  113.02 4457.62  112.68  4472.6   108.7  4562.5  106.57
#Mann= 5 ,-1 , 0
       0     .07       0 2906.21     .06       0 3015.71     .07       0
 3433.81     .04       0 3623.59     .07       0
#XS Ineff= 2 ,-1
    2800 2926.13   106.5 3015.71    3200   105.9
Permanent Ineff=
       F       F
#Block Obstruct= 1 ,-1
  1312.9 2252.54   105.2
Bank Sta=3433.81,3623.59
XS Rating Curve= 0 ,0
Exp/Cntr=0.5,0.3

Type RM Length L Ch R = 1 ,24381.77,389.1,249.22,245.84
Node Name=C
XS GIS Cut Line= 5
3022556.4714720213864741.41602813022767.9313509513863344.2711846
3023224.8352927713862422.91082263023949.8404044513862045.3039663
3023949.8404044513860756.5696671
#Sta/Elev= 30
       0  112.48  429.41  108.34  479.34  111.71  569.22  108.26  629.13  111.61
  1233.3  105.64 1303.21  105.42 1333.17  108.12 1368.12  103.36 1388.09  103.18
 1912.29  105.95 1997.17  108.73  2042.1  103.71 2196.86  106.51 2471.39  105.26
 2526.22  106.06 2556.13  109.32 2630.89  105.02 2795.38  106.14 2845.23   96.68
 2880.12  105.55 2905.04  109.47 2964.85  111.38 3024.67  105.76 3413.79  105.81
 3453.75   95.16  3508.7   94.21 3553.65    94.9 3593.61  106.44 4547.69  106.88
#Mann= 5 ,-1 , 0
       0     .07       0 2795.38     .06       0 2880.12     .07       0
 3413.79     .04       0 3593.61     .07       0
#Block Obstruct= 1 ,-1
 1333.17 2196.86     105
Bank Sta=3413.79,3593.61
XS Rating Curve= 0 ,0
Exp/Cntr=0.5,0.3

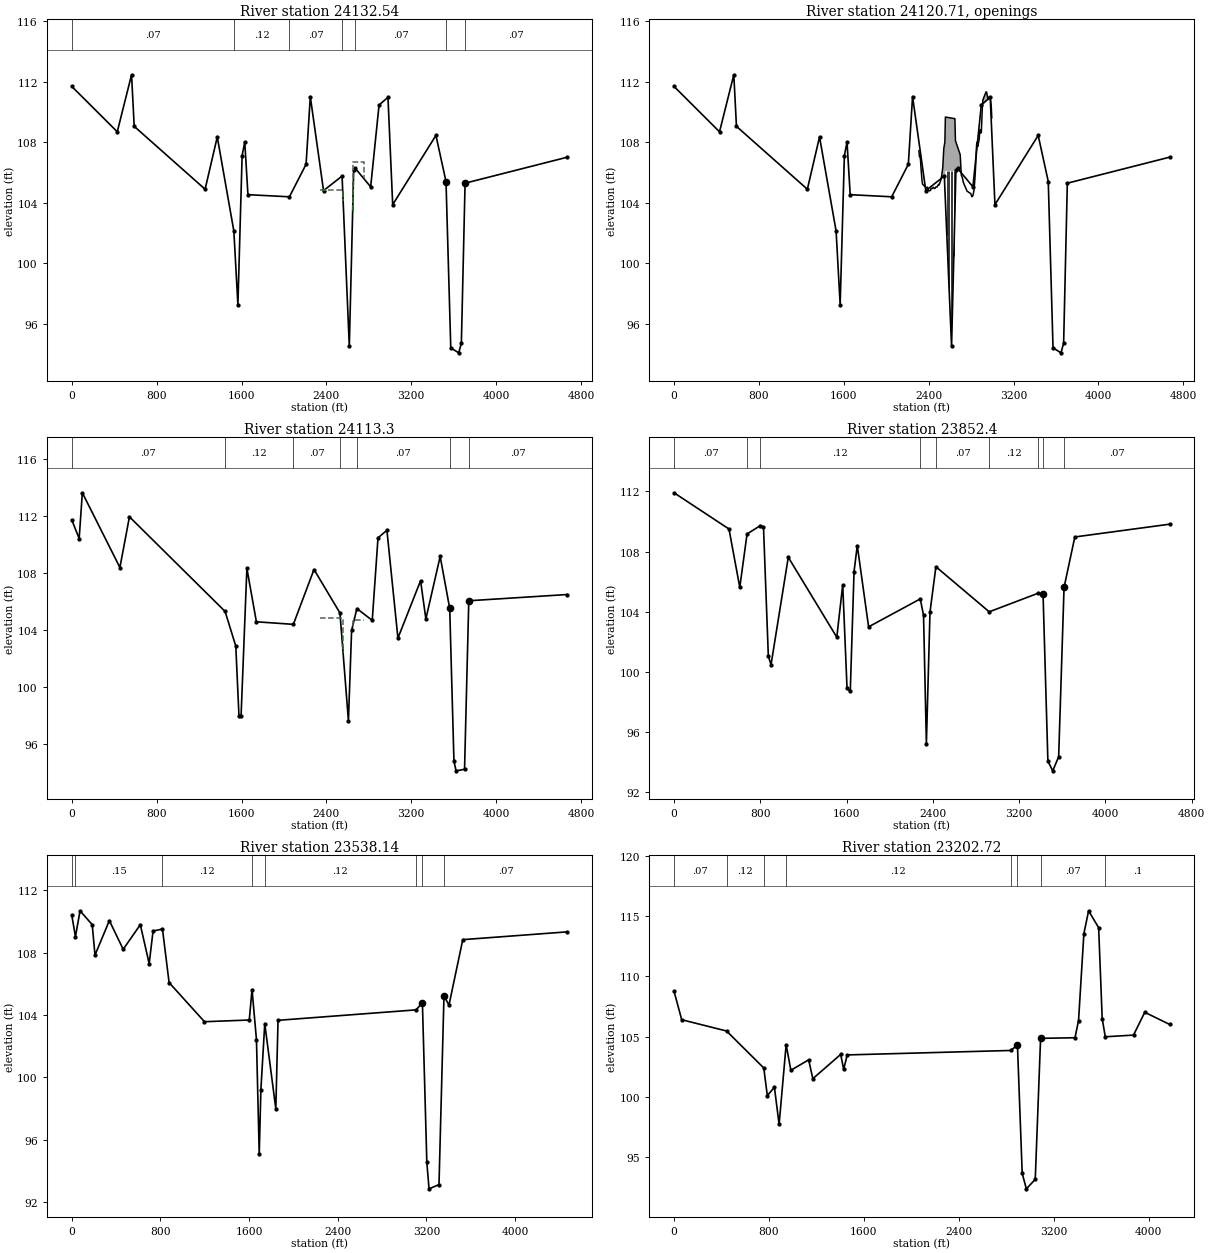
Type RM Length L Ch R = 1 ,24132.54,35.66,19.24,18.91
BEGIN DESCRIPTION:
Upstream Section (DS GOLF CART BR)
END DESCRIPTION:
XS GIS Cut Line= 6
3022812.9876912813864721.45150113023174.6772566113863254.2290419
3023462.4670353513862537.75606543023996.4157706113862550.4866829
3024195.7214743613862232.30162383024195.5164222713860754.1005119
#Sta/Elev= 30
       0  111.69  428.91  108.69  563.56  112.46   588.5  109.05 1256.79  104.89
  1371.5  108.35 1527.64  102.13 1565.94   97.26 1605.79  107.12  1630.7  108.01
 1660.58  104.53  2051.6  104.39 2208.53  106.54 2248.39  111.02  2373.1   104.8
  2547.8  105.76 2615.98    94.5 2657.19  106.14 2672.59  106.27 2817.35  105.05
 2896.39  110.46 2980.37  110.97 3024.84  103.87 3432.51  108.45 3527.39   105.4
 3572.34    94.4 3647.25   94.07 3672.22   94.71 3707.18  105.29    4671  107.01
#Mann= 7 ,-1 , 0
       0     .07       0 1527.64     .12       0  2051.6     .07       0
  2547.8     .06       0 2672.59     .07       0 3527.39     .04       0
 3707.18     .07       0
#XS Ineff= 2 ,-1
    2340 2557.79  104.83 2647.63    2750  106.72
Permanent Ineff=
       F       F
Bank Sta=3527.39,3707.18
XS Rating Curve= 0 ,0
Exp/Cntr=0.5,0.3

Type RM Length L Ch R = 4 ,24120.71,,,
BEGIN DESCRIPTION:
DS GOLF CART BR
END DESCRIPTION:
Node Name=DS GOLF CART BR
Bridge Culvert--1,0,-1,-1, 0
Deck Dist Width WeirC Skew NumUp NumDn MinLoCord MaxHiCord MaxSubmerge Is_Ogee
2,15,2.6,0, 55, 55, , , 0.98, 0, 0,0,,
 2308.21  2313.2  2318.2 2323.19 2328.18 2338.16 2343.15 2378.09 2388.08 2403.05
 2418.02 2423.02 2437.99 2442.98 2457.96 2467.94 2477.92  2492.9 2497.89 2512.86
 2522.85 2532.83 2542.81  2552.8 2557.79 2647.63 2652.62 2697.55 2707.53 2717.51
  2727.5 2762.44 2797.38 2807.36 2817.34 2827.22 2837.11 2842.05 2851.93 2856.87
 2861.81 2876.63 2881.57 2886.51 2891.45 2896.39 2906.27 2911.21 2940.85 2945.79
 2960.61 2970.49 2980.37 2990.25 2995.19
  107.43  107.05  107.12  106.83  106.27   105.4  105.22  104.98  105.03  104.78
  104.81  104.95  104.94  105.02  104.93  105.04  105.03  105.21  105.17  105.44
  105.78  106.31107.5809108.0102109.6664109.5558108.1036107.1701  105.83  105.66
  105.33  104.76   104.6  104.39  104.46  104.82  105.67  106.31  107.83  108.01
  107.71  108.19  108.76  108.83  108.61  108.63  110.34   110.8  111.33  111.32
  110.83  110.99  111.01  110.37  109.61
       0       0       0       0       0       0       0       0       0       0
       0       0       0       0       0       0       0       0       0       0
       0       0       0       0106.1003106.1095       0       0       0       0
       0       0       0       0       0       0       0       0       0       0
       0       0       0       0       0       0       0       0       0       0
       0       0       0       0       0
 2308.21  2313.2  2318.2 2323.19 2328.18 2338.16 2343.15 2378.09 2388.08 2403.05
 2418.02 2423.02 2437.99 2442.98 2457.96 2467.94 2477.92  2492.9 2497.89 2512.86
 2522.85 2532.83 2542.81  2552.8 2557.79 2647.63 2652.62 2697.55 2707.53 2717.51
  2727.5 2762.44 2797.38 2807.36 2817.34 2827.22 2837.11 2842.05 2851.93 2856.87
 2861.81 2876.63 2881.57 2886.51 2891.45 2896.39 2906.27 2911.21 2940.85 2945.79
 2960.61 2970.49 2980.37 2990.25 2995.19
  107.43  107.05  107.12  106.83  106.27   105.4  105.22  104.98  105.03  104.78
  104.81  104.95  104.94  105.02  104.93  105.04  105.03  105.21  105.17  105.44
  105.78  106.31107.5809108.0102109.6664109.5558108.1036107.1701  105.83  105.66
  105.33  104.76   104.6  104.39  104.46  104.82  105.67  106.31  107.83  108.01
  107.71  108.19  108.76  108.83  108.61  108.63  110.34   110.8  111.33  111.32
  110.83  110.99  111.01  110.37  109.61
       0       0       0       0       0       0       0       0       0       0
       0       0       0       0       0       0       0       0       0       0
       0       0       0       0106.1003106.1095       0       0       0       0
       0       0       0       0       0       0       0       0       0       0
       0       0       0       0       0       0       0       0       0       0
       0       0       0       0       0
Pier Skew, UpSta & Num, DnSta & Num=  ,2571.5, 2 ,2571.5, 2 , 0 , 0 , 0 ,,
       1       1
      90   107.5
       1       1
      90   107.5
Pier Skew, UpSta & Num, DnSta & Num=  ,2583, 2 ,2583, 2 , 0 , 0 , 0 ,,
       1       1
      90   107.5
       1       1
      90   107.5
Pier Skew, UpSta & Num, DnSta & Num=  ,2593.2, 2 ,2593.2, 2 , 0 , 0 , 0 ,,
       1       1
      90   107.5
       1       1
      90   107.5
Pier Skew, UpSta & Num, DnSta & Num=  ,2610.5, 2 ,2610.5, 2 , 0 , 0 , 0 ,,
       1       1
      90   107.5
       1       1
      90   107.5
Pier Skew, UpSta & Num, DnSta & Num=  ,2623.4, 2 ,2623.4, 2 , 0 , 0 , 0 ,,
       1       1
      90   107.5
       1       1
      90   107.5
Pier Skew, UpSta & Num, DnSta & Num=  ,2637.2, 2 ,2637.2, 2 , 0 , 0 , 0 ,,
       1       1
      90   107.5
       1       1
      90   107.5
BR Coef=-1 , 1 , 1 ,0.9, 0 ,,,0.8,-1,1.2,0,
WSPro=,,,, 1 ,,,, 0 ,,,, 0 ,,,,-1 ,-1 ,-1 , 0 , 0 , 0 , 0 , 0
BC Mult= 1 ,0,2250,0,2250
BC Mult= 3 ,2250,2750,2250,2750
BC Mult= 1 ,2750,4671,2750,4671
BC Design=,, 0 ,, 0 ,,,,,,
BC Use User HTab Curves=0
BC User HTab FreeFlow(D)= 0

Type RM Length L Ch R = 1 ,24113.3 ,238.4,260.91,239.65
BEGIN DESCRIPTION:
Downstream Section (DS GOLF CART BR)
END DESCRIPTION:
XS GIS Cut Line= 6
3022831.8971022813864753.91272233023193.58666761 13863286.690263
3023481.3764463713862570.2172865 3024015.325181613862582.9479041
3024214.6308853613862264.76284493024214.4258332713860786.5617331
#Sta/Elev= 30
       0  111.74   69.82  110.43   99.75  113.65  453.84  108.39  543.61  111.96
  1445.2   105.3 1546.01  102.86  1575.9   97.96 1595.83   97.94 1650.62  108.33
 1740.29  104.57 2088.63  104.39 2283.25  108.25 2527.84  105.19  2607.7    97.6
 2637.65  103.96 2687.57   105.5 2832.17  104.67 2886.51  110.48 2970.49  111.01
 3074.24  103.42 3287.69  107.46 3337.62  104.77 3472.46  109.17 3562.35  105.51
  3602.3   94.76 3622.28   94.08 3702.18   94.19 3742.13  106.05    4671  106.49
#Mann= 7 ,-1 , 0
       0     .07       0  1445.2     .12       0 2088.63     .07       0
 2527.84     .06       0 2687.57     .07       0 3562.35     .04       0
 3742.13     .07       0
#XS Ineff= 2 ,-1
    2340 2557.79  104.83 2647.63    2750   104.7
Permanent Ineff=
       F       F
Bank Sta=3562.35,3742.13
XS Rating Curve= 0 ,0
Exp/Cntr=0.5,0.3

Type RM Length L Ch R = 1 ,23852.4 ,610.29,314.26,293.8
XS GIS Cut Line= 5
 3022945.788278713864739.81465343023565.3159110213862818.2594413
3024060.7981877813862647.55177753024359.5859760213862382.7770446
3024600.1458623613860747.7652228
#Sta/Elev= 30
       0  111.91  509.74   109.5  609.68  105.62  677.26  109.17  801.48  109.73
  829.57  109.64  874.55  101.04  899.53  100.47 1059.45  107.62 1509.22   102.3
 1564.19  105.78 1604.17    98.9 1634.16   98.69 1669.14  106.66 1699.12   108.4
 1804.07  102.99 2283.49  104.85 2313.45  103.75  2339.9   95.21 2373.43  103.98
 2428.23  106.99 2922.54  103.99 3377.14  105.23 3421.54  105.19 3466.48   94.05
 3511.41   93.41 3566.33   94.35 3616.26  105.61 3716.11  108.97 4594.83  109.82
#Mann= 9 ,-1 , 0
       0     .07       0  677.26     .15       0  801.48     .12       0
 2283.49     .06       0 2428.23     .07       0 2922.54     .12       0
 3377.14     .07       0 3421.54     .04       0 3616.26     .07       0
Bank Sta=3421.54,3616.26
XS Rating Curve= 0 ,0
Exp/Cntr=0.3,0.1

Type RM Length L Ch R = 1 ,23538.14,1183.82,335.41,333.1
Node Name=B
XS GIS Cut Line= 4
3023330.36756203 13864738.0062583023868.2001477813863378.6493967
3024642.5601476113862593.29991753024867.9182926913860700.0372999
#Sta/Elev= 30
       0  110.41   33.26  109.02   74.84  110.68  184.61  109.79  209.55  107.84
  339.28  110.05  464.01  108.21  618.68  109.79  698.51  107.29  733.44  109.38
  818.42  109.51  878.13  106.08 1197.45  103.57 1601.63  103.68 1626.58  105.63
  1666.5  102.42 1691.46   95.08 1706.43   99.21 1741.36  103.45 1841.17   97.99
 1861.13  103.66 3106.79  104.33 3163.75  104.79 3203.68   94.57 3223.64   92.86
 3313.48   93.13  3358.4  105.24 3403.33  104.63 3528.11  108.83 4471.44  109.33
#Mann= 8 ,-1 , 0
       0     .07       0   33.26     .15       0  818.42     .12       0
 1626.58     .06       0 1741.36     .12       0 3106.79     .07       0
 3163.75     .04       0  3358.4     .07       0
Bank Sta=3163.75,3358.4
XS Rating Curve= 0 ,0
Exp/Cntr=0.3,0.1

Type RM Length L Ch R = 1 ,23202.72,1587.3,489.3,446.55
XS GIS Cut Line= 5
3024270.7833321113864763.39465873024699.0019638513864045.0555442
3024758.7652957713863925.52888043025111.94011436 13861521.430014
3025221.5087928613860751.8239417
#Sta/Elev= 30
       0  108.78   64.71   106.4  443.04  105.46  756.64  102.38  786.51  100.08
  846.19  100.78  885.78   97.69  945.18  104.32  984.92  102.19 1134.92  103.06
 1169.92  101.49 1404.91  103.51  1429.9  102.27  1459.9  103.47 2836.55  103.84
 2894.84  104.28 2934.84   93.61 2969.84   92.32 3044.84   93.11 3089.83  104.85
 3379.82   104.9 3409.79  106.33 3454.64  113.56  3494.5  115.47 3579.22  114.06
 3609.11  106.49 3635.18  104.98 3873.22  105.12  3967.9  107.02 4177.19  106.01
#Mann= 8 ,-1 , 0
       0     .07       0  443.04     .12       0  756.64     .06       0
  945.18     .12       0 2836.55     .07       0 2894.84     .04       0
 3089.83     .07       0 3635.18      .1       0
#XS Ineff= 1 ,-1
       0  945.18  104.32
Permanent Ineff=
       F
Bank Sta=2894.84,3089.83
XS Rating Curve= 0 ,0
Exp/Cntr=0.3,0.1