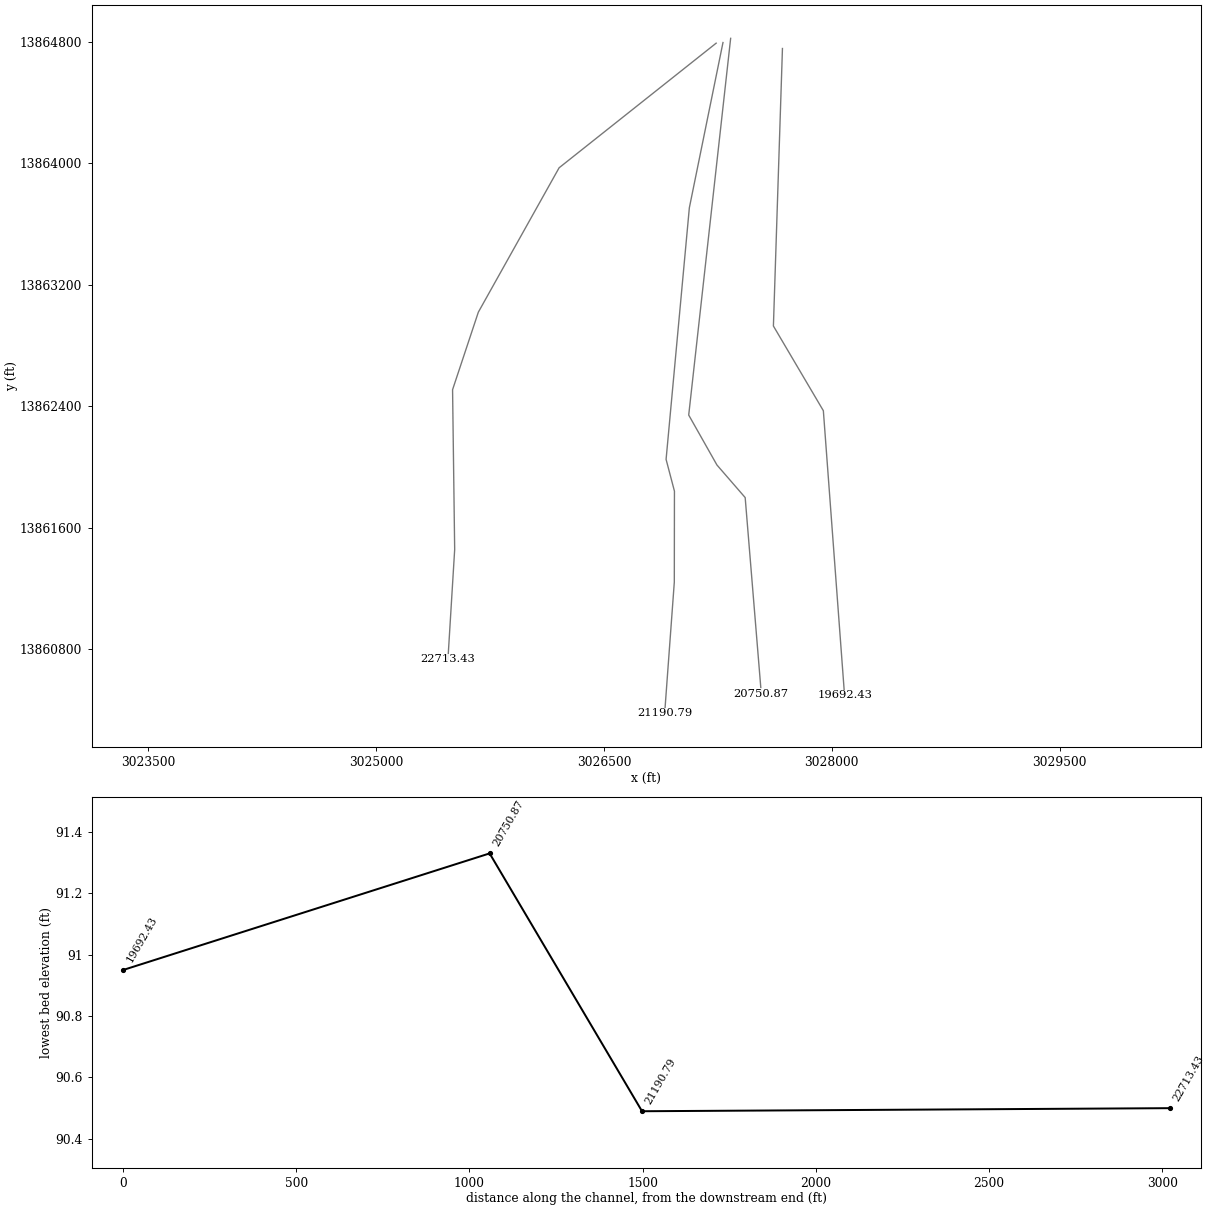
HEC-RAS study U102-00-00.prj: U102-00-00 (Update)

--- U102-00-00.g01 (geometry) --- (continued)

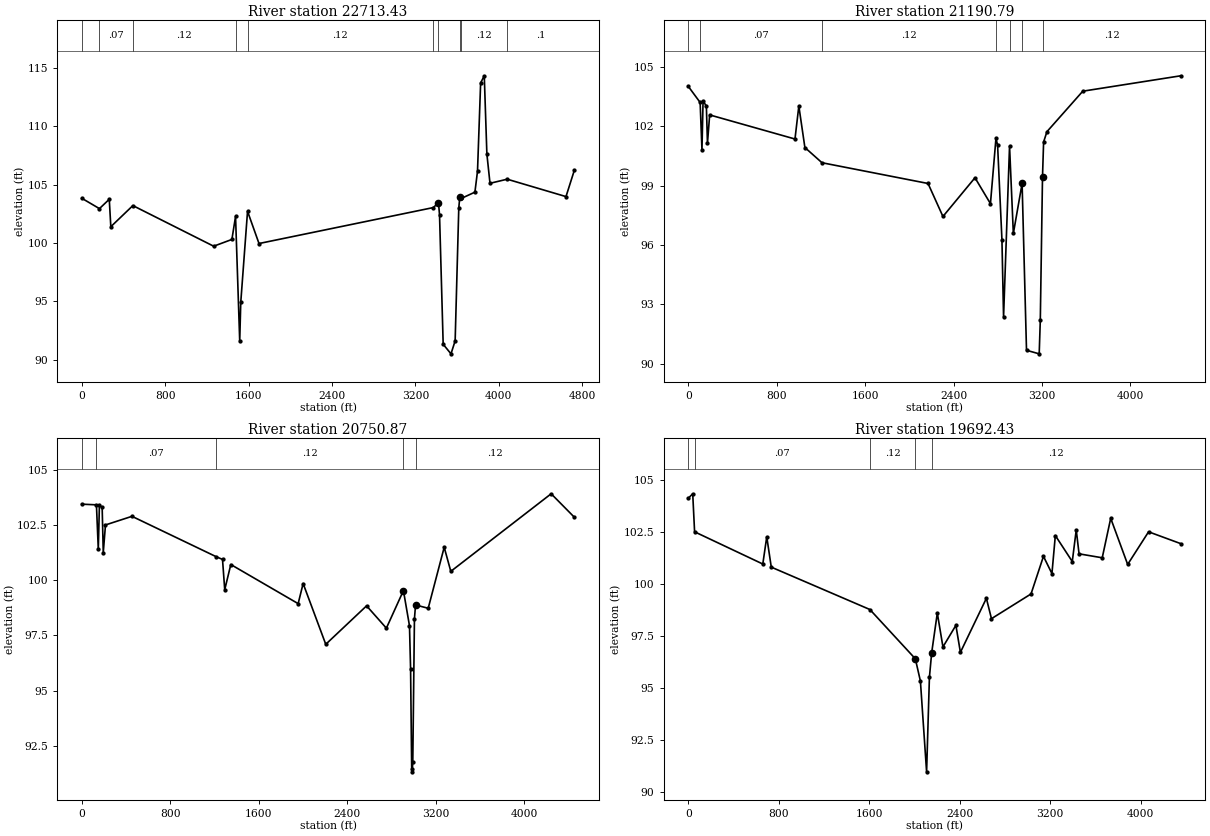
Type RM Length L Ch R = 1 ,22713.43,1508.96,1522.64,1512.72
XS GIS Cut Line= 6
3027238.3269376913864791.92905043026204.2545307713863971.4044448
3025672.3901089413863020.63994213025502.8218785213862510.4224586
3025516.6706041113861457.93473423025472.2950366913860735.5119664
#Sta/Elev= 30
       0  103.83  169.76  102.94  264.01  103.74  278.96  101.39  490.34   103.2
 1265.27   99.72    1440   100.3 1474.98  102.27 1514.96    91.6 1524.95   94.91
 1589.92  102.71 1699.86   99.95 3371.28  103.03 3421.05  103.45 3431.03  102.39
 3465.95   91.32 3540.77    90.5 3580.68   91.61  3615.6  102.99 3625.58  103.97
 3638.44  103.81 3770.24  104.35 3795.18  106.15 3825.11  113.71 3860.03  114.32
 3884.98  107.62 3914.91  105.11 4079.89  105.46 4643.63  103.97  4723.5  106.22
#Mann= 10 ,-1 , 0
       0      .1       0  169.76     .07       0  490.34     .12       0
 1474.98     .06       0 1589.92     .12       0 3371.28     .07       0
 3421.05     .04       0 3625.58     .07       0 3638.44     .12       0
 4079.89      .1       0
Bank Sta=3421.05,3625.58
XS Rating Curve= 0 ,0
Exp/Cntr=0.3,0.1

Type RM Length L Ch R = 1 ,21190.79,130.9,439.92,580.91
XS GIS Cut Line= 6
3027283.1667430313864796.06814983027061.7597055313863708.1188821
3026908.59072053 13862051.562812 3026963.622762713861842.3050284
3026962.7467801913861243.53194783026899.1645582813860379.3004085
#Sta/Elev= 30
       0  104.03     108  103.21  124.47  100.81  134.42  103.28   164.3  103.03
  174.25  101.15  194.17  102.58  965.87  101.36 1000.72  103.03 1055.48  100.93
 1210.17  100.16 2169.37   99.11 2304.26   97.44 2594.01    99.4  2733.9   98.09
  2783.7  101.39 2798.45  101.06 2837.79   96.27 2852.54   92.35 2906.64     101
 2941.06   96.58 3020.17   99.11 3060.09   90.67 3174.85   90.49 3184.83   92.19
 3204.79   99.45 3214.77  101.21 3244.71  101.73 3569.04  103.78 4455.57  104.56
#Mann= 7 ,-1 , 0
       0      .1       0     108     .07       0 1210.17     .12       0
  2783.7     .06       0 2906.64     .12       0 3020.17     .04       0
 3204.79     .12       0
Bank Sta=3020.17,3204.79
XS Rating Curve= 0 ,0
Exp/Cntr=0.3,0.1

Type RM Length L Ch R = 1 ,20750.87,582.01,1058.44,860.21
XS GIS Cut Line= 5
3027333.6846866213864823.71507613027057.5599107713862343.4398529
3027243.4299458613862014.57994643027429.2999809413861800.1099029
3027535.5100703513860508.4431949
#Sta/Elev= 30
       0  103.44  132.89  103.41  149.74   101.4  159.72  103.38  184.67   103.3
  194.66  101.25  214.62   102.5   454.2  102.89    1217  101.06 1272.75  100.94
 1292.72   99.57 1347.62  100.71 1956.55   98.94 2001.47   99.85  2206.1    97.1
 2575.12   98.84 2754.06   97.83  2908.2   99.53 2962.97   97.94 2972.93   95.98
 2982.88   91.48 2987.86   91.33 2992.84   91.79 3007.78   98.25 3017.74   98.88
 3132.25   98.73 3276.78  101.49  3336.6   100.4 4243.81  103.91 4453.16  102.85
#Mann= 5 ,-1 , 0
       0      .1       0  132.89     .07       0    1217     .12       0
  2908.2     .04       0 3017.74     .12       0
Bank Sta=2908.2,3017.74
XS Rating Curve= 0 ,0
Exp/Cntr=0.3,0.1

Type RM Length L Ch R = 1 ,19692.43,0,0,0
Node Name=A
XS GIS Cut Line= 4
3027674.7259992813864756.76409453027615.1798585213862929.6499666
 3027944.029922613862372.03001893028083.4899455313860499.2499718
#Sta/Elev= 30
       0  104.11   39.96  104.33   56.49   102.5  659.31  100.95  694.27  102.26
  734.23   100.8 1605.83   98.76 2007.35   96.39 2052.17   95.32 2106.95   90.95
 2131.84    95.5 2151.76   96.68 2201.56   98.59 2251.36   96.96 2365.89      98
 2405.73    96.7 2635.28    99.3 2680.23   98.32 3029.85   99.51 3139.73  101.32
 3214.64  100.49 3244.61  102.32 3394.45  101.07 3429.41  102.59 3454.39  101.44
 3659.16  101.25 3734.08  103.15 3883.92  100.93 4068.72   102.5 4353.41  101.93
#Mann= 5 ,-1 , 0
       0      .1       0   56.49     .07       0 1605.83     .12       0
 2007.35     .06       0 2151.76     .12       0
Bank Sta=2007.35,2151.76
XS Rating Curve= 0 ,0
Exp/Cntr=0.3,0.1

Chan Stop Cuts=-1
Use User Specified Reach Order=0
Composite Channel Slope=5